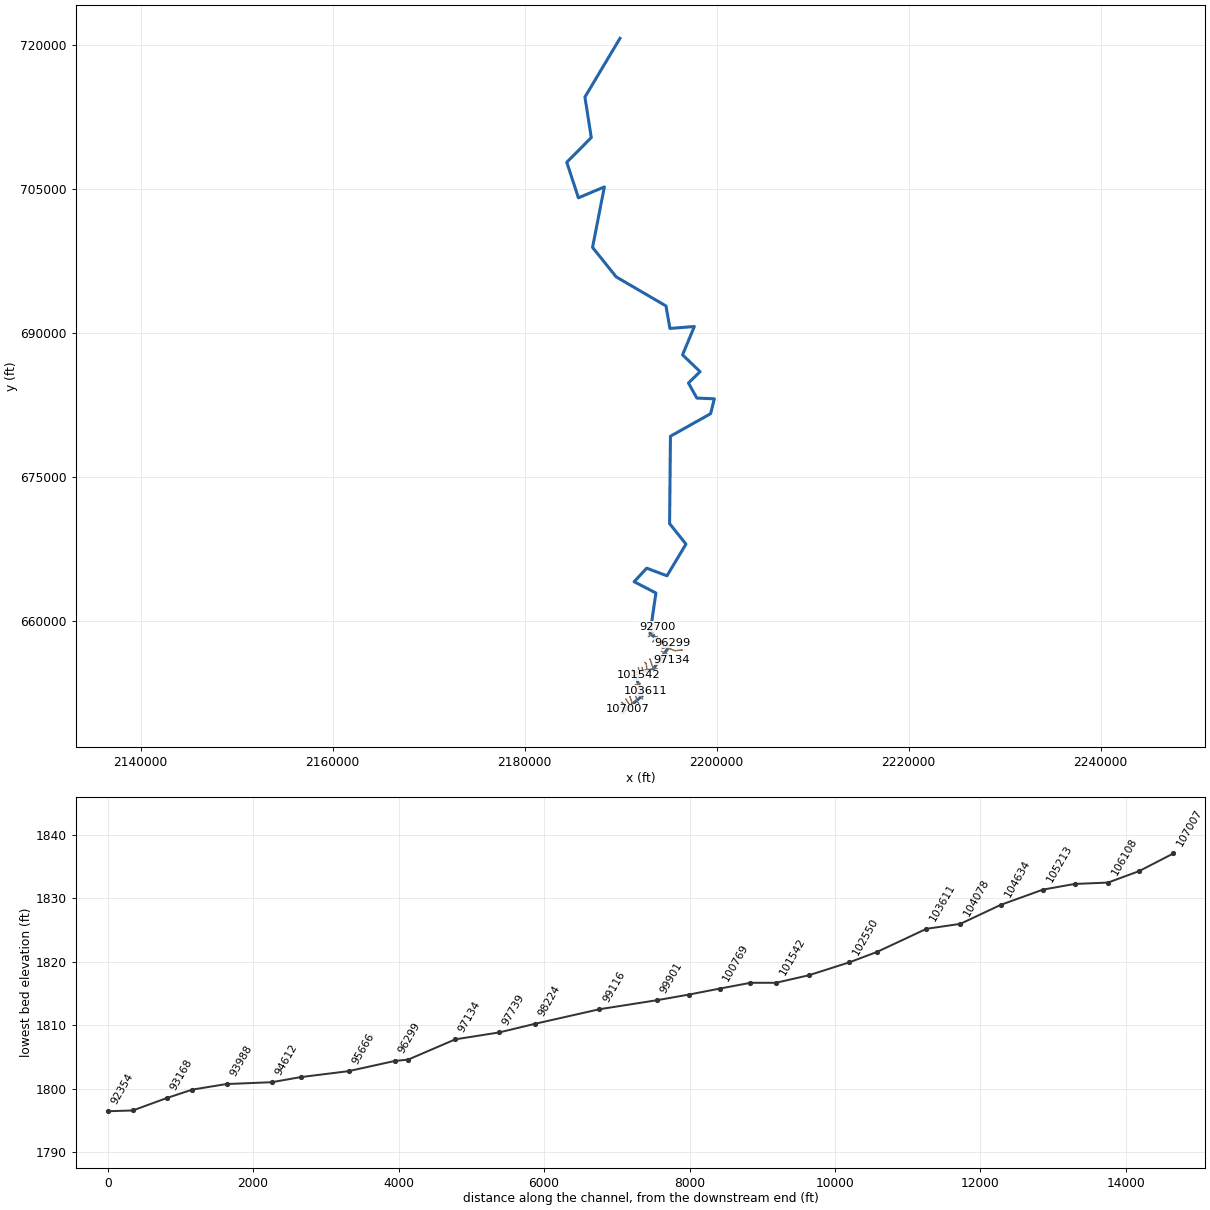
--- BUCKHANR_U.prj (project) ---

Proj Title=BUCKHANR_U
Current Plan=p01
Default Exp/Contr=0,0
English Units
Geom File=g01
Flow File=f01
Plan File=p01
BEGIN DESCRIPTION:
---------- MODELED AS PART OF WVEMD CTP PROGRAM, 2023----------
Stream Name: Buckhannon River (Upper)
Flood Zone:  AFH
Upshur County, WV
HEC-RAS Version: RAS 6.3
Vertical Datum: NAVD88
Projection: NAD 1983 StatePlane West Virginia S FIPS 4702 (US Feet)
Terrain: 1-meter LIDAR (FEMA Region III 3DEP collected 2016-2018)
Land Use: 2019 NLCD
Hydrologic Method:
Gage-Weighted WV 2010 RRE
Additional Model Notes:
None
END DESCRIPTION:
DSS Export Rating Curves= 0
DSS Export Rating Curve Sorted= 0
DSS Export Volume Flow Curves= 0
DXF OffsetX= 0
DXF OffsetY= 0
DXF ScaleX= 0
DXF ScaleY= 0

--- BUCKHANR_U.p01 (plan) ---

Plan Title=Floodplain
Program Version=6.30
Short Identifier=Floodplain
Geom File=g01
Flow File=f01
Subcritical Flow
K Sum by GR= 0
Std Step Tol= 0.01
Critical Tol= 0.01
Num of Std Step Trials= 20
Max Error Tol= 0.3
Flow Tol Ratio= 0.001
Split Flow NTrial= 30
Split Flow Tol= 0.02
Split Flow Ratio= 0.02
Log Output Level= 0
Friction Slope Method= 1
Unsteady Friction Slope Method= 2
Unsteady Bridges Friction Slope Method= 1
Parabolic Critical Depth
Global Vel Dist= 0 , 0 , 0
Global Log Level= 0
CheckData=False
Encroach Param=-1 ,0,0, 0
Mapping Interval=1HOUR
Computation Time Step Use Courant=        0
Computation Time Step Use Time Series=    0
Computation Time Step Count To Double=0
Computation Time Step Max Doubling=0
Computation Time Step Max Halving=0
Computation Time Step Residence Courant=0
Run HTab= 0
Run UNet= 0
Run Sediment= 0
Run PostProcess= 0
Run WQNet= 0
Run RASMapper=-1
UNET Theta= 0
UNET Theta Warmup= 0
UNET ZTol= 0
UNET ZSATol= 0
UNET MxIter= 0
UNET Max Iter WO Improvement= 0
UNET MaxInSteps= 0
UNET DtIC= 0
UNET DtMin= 0
UNET MaxCRTS= 0
UNET WFStab= 0
UNET SFStab= 0
UNET WFX= 1
UNET SFX= 1
UNET Gravity=32.17405
UNET 1D Methodology=Finite Difference
UNET DSS MLevel= 1
UNET Pardiso=0
UNET DZMax Abort= 0
UNET Use Existing IB Tables= 0
UNET Froude Reduction=False
UNET Froude Limit= 0
UNET Froude Power= 0
UNET D1 Cores= 0
UNET WindReference=Eulerian
UNET WindDragFormulation=Hsu (1988)
UNET D2 Coriolis=0
UNET D2 Cores= 0
UNET D2 Theta= 1
UNET D2 Theta Warmup= 1
UNET D2 Z Tol= 0.01
UNET D2 Volume Tol= 0.01
UNET D2 Max Iterations= 20
UNET D2 Equation= 0
UNET D2 RampUpFraction=0.1
UNET D2 TimeSlices= 1
UNET D2 Turbulence Formulation=Non-Conservative (original)
UNET D2 Eddy Viscosity=0.3
UNET D2 Transverse Eddy Viscosity=0.1
UNET D2 Smagorinsky Mixing=0
UNET D2 BCVolumeCheck=0
UNET D2 Cores=0
UNET D2 SolverType=PARDISO (Direct)
UNET D2 Minimum Iterations= 3
UNET D2 Maximum Iterations= 30
UNET D2 Restart Number= 10
UNET D2 Relaxation Coeff=1.3
UNET D2 SOR Precondition Iterations= 10
UNET D2 ILUT Maximum Fill= 8
UNET D2 ILUT Tolerance=1E-08
UNET D2 Convergence Tolerance=0.00001
UNET D1D2 MaxIter= 0
UNET D1D2 ZTol=0.01
UNET D1D2 QTol=0.1
UNET D1D2 MinQTol=1
Write IC File= 0
Write IC File at Fixed DateTime=0
Write IC File at Sim End=0
Echo Input=False
Echo Parameters=False
Echo Output=False
Write Detailed= 0
HDF Write Warmup=0
HDF Write Time Slices=0
HDF Flush=0
HDF Compression= 1
HDF Chunk Size= 1
HDF Spatial Parts= 1
HDF Use Max Rows=0
HDF Fixed Rows= 1
Calibration Method= 0
Calibration Iterations= 20
Calibration Max Change=0.05
Calibration Tolerance=0.2
Calibration Maximum=1.5
Calibration Minimum=0.5
Calibration Optimization Method= 1
WQ AD Non Conservative
WQ ULTIMATE=-1
WQ Max Comp Step=1HOUR
WQ Output Interval=15MIN
WQ Output Selected Increments= 0
WQ Output face flow=0
WQ Output face velocity=0
WQ Output face area=0
WQ Output face dispersion=0
WQ Output cell volume=0
WQ Output cell surface area=0
WQ Output cell continuity=0
WQ Output cumulative cell continuity=0
WQ Output face conc=0
WQ Output face dconc_dx=0
WQ Output face courant=0
WQ Output face peclet=0
WQ Output face adv mass=0
WQ Output face disp mass=0
WQ Output cell mass=0
WQ Output cell source sink temp=0
WQ Output nsm pathways=0
WQ Output nsm derived pathways=0
WQ Create Restart=0
WQ Fixed Restart=0
WQ System Summary=0
WQ Write To DSS=0
Sorting and Armoring Iterations= 10
XS Update Threshold= 0.02
Bed Roughness Predictor= 0
Hydraulics Update Threshold= 0.02
Energy Slope Method= 1
Volume Change Method= 1
Sediment Retention Method= 0
Sediment TS Multiplier= 1
Warm Up Method= 0
XS Weighting Method= 0
Number of US Weighted Cross Sections= 1
Number of DS Weighted Cross Sections= 1
Upstream XS Weight=0
Main XS Weight=1
Downstream XS Weight=0
Number of DS XS's Weighted with US Boundary= 1
Upstream Boundary Weight= 1
Weight of XSs Associated with US Boundary= 0
Number of US XS's Weighted with DS Boundary= 1
Downstream Boundary Weight= 0.5
Weight of XSs Associated with DS Boundary= 0.5
Percentile Method= 0
Sediment Output Level= 3
Mass or Volume Output= 0
Output Increment Type= 1
Profile and TS Output Increment= 1
Transport Output Increment 1
XS Output Flag= 0
XS Output Increment= 10
Read HDF5 Sediment Hotstart= 0
Sediment Hotstart Type= 0
Write Gradation File= 0
Read Gradation Hotstart= 0
Write HDF5 File= 1
Write Binary Output= 1
Write DSS Sediment File= 0
DSS Sediment Output Type= 1
SV Curve= 0
Specific Gage Flag= 0
Subcell Erosion Methods= 0
Subcell Deposition Methods= 0
Advection Scheme= 1
Matrix Solver= 0
Implicit Weighting Factor= 1
Maximum Outer Loop Convergence Iterations= 5
Convergence Maximum Absolute= 0.001
Convergence RMSE= 0.0001
Grain Fractions Max Abs Error= 0.001
Max Subgrid Regions= 1
Max Subgrid Length Scale= 3.402823E+38
Initial Layer Thickness= 3.402823E+38
Min Layer Thickness= 3.402823E+38
Max Layer Thickness= 3.402823E+38
Number of Layers= 5

--- BUCKHANR_U.f01 (steady flow) ---

Flow Title=Flows
Program Version=6.31
Number of Profiles= 1
Profile Names=01pct
River Rch & RM=BUCKHANR_U,Main,107007
   12700
Boundary for River Rch & Prof#=BUCKHANR_U,Main            , 1
Up Type= 0
Dn Type= 3
Dn Slope=0.00503
DSS Import GetInterval= 0
DSS Import GetPeak= 0
DSS Import FillOption= 0

--- BUCKHANR_U.g01 (geometry) ---

Geom Title=Geometry
Program Version=6.31

River Reach=BUCKHANR_U      ,Main
Reach XY= 30
     2190223.548      650454.868     2192285.072      652193.886
     2191466.071      654603.272     2193351.491      654909.267
     2195026.208      657248.056     2193067.874       658655.61
      2193686.36      662901.824      2191416.05      664078.387
     2192728.569      665488.059     2194839.486      664694.326
     2196814.503      667998.374     2195109.109      670134.874
     2195198.879      679244.014     2199381.679      681595.251
     2199769.174      683146.488      2197948.57      683224.324
     2197073.682      684792.016     2198286.444      685977.765
     2196459.402      687731.005     2197687.932      690686.076
     2195143.764      690480.782     2194734.635      692829.215
     2189540.847      695861.379     2187085.074      698931.116
      2188315.55      705238.111     2185613.247      704100.981
      2184398.31      707805.373     2186952.838      710379.216
     2186292.372      714607.603     2189940.818      720726.988

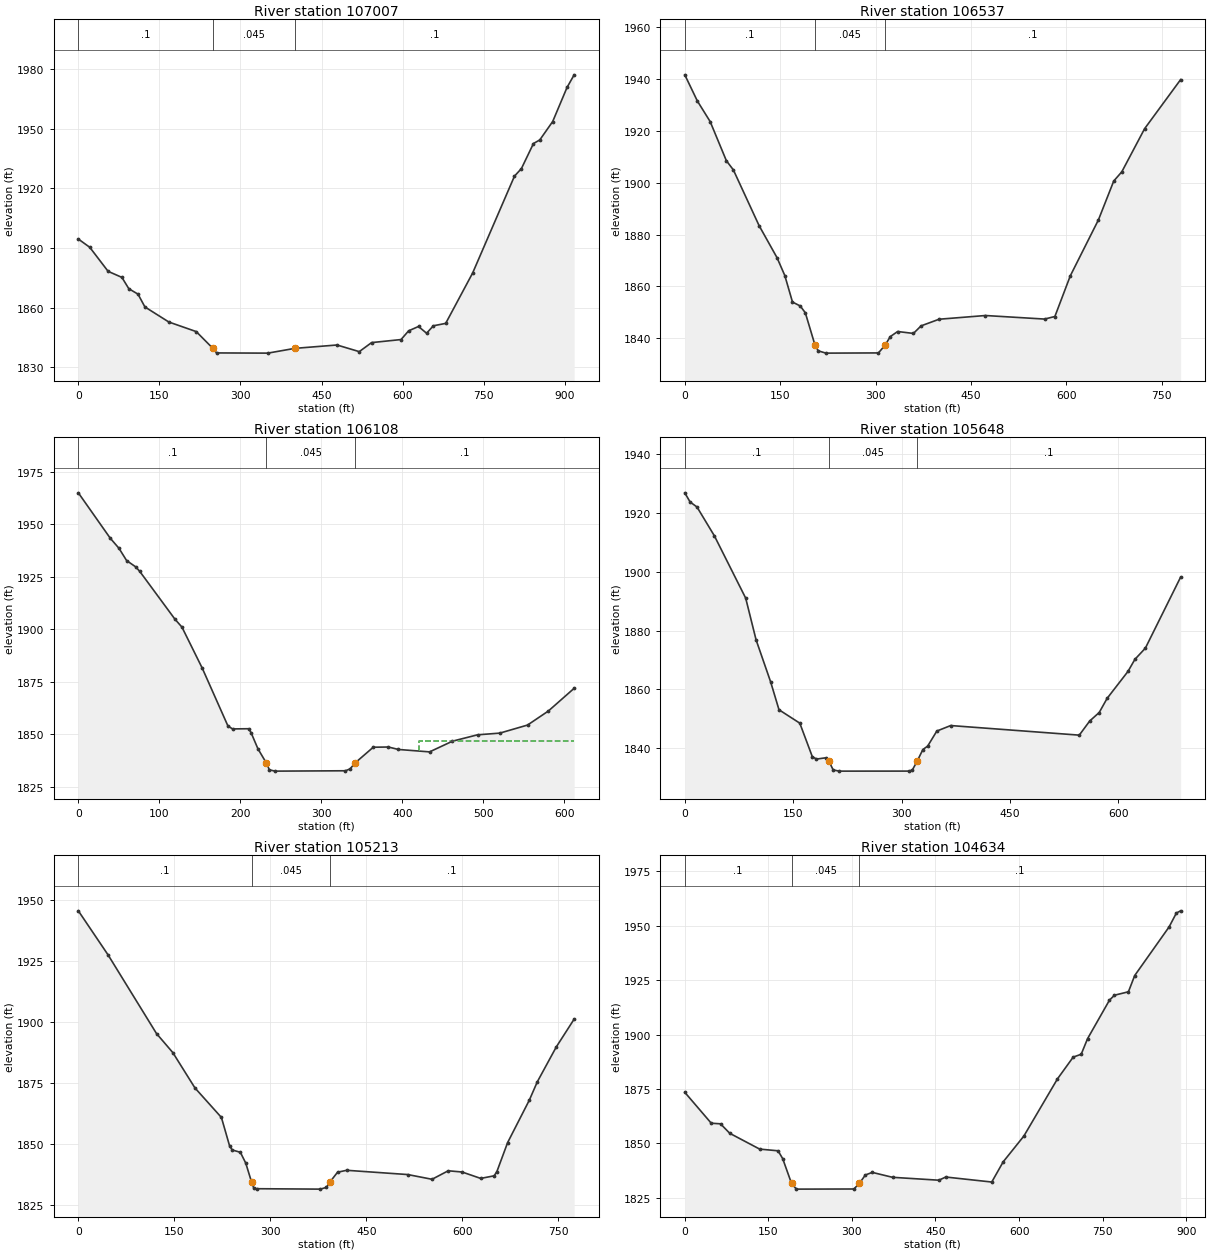
Type RM Length L Ch R = 1 ,107007  ,470,470,470
XS GIS Cut Line= 4
2189932.37007168650351.9739080442190060.25883885650398.310417888
 2190610.7365758650702.2779224672190747.89264494650769.002496643
#Sta/Elev= 30
       0 1894.47    21.1 1890.33    55.1 1878.22    80.6 1875.18    93.4 1869.48
   110.4 1866.74   123.2  1860.3   167.5 1852.71   218.2 1847.89  248.911839.467
   255.8 1837.16   350.7 1837.06   400.6 1839.46   478.6 1841.15   519.8 1837.81
   542.6 1842.36   597.1 1843.89   611.1 1848.27   629.4 1850.47   644.4 1847.06
   656.8 1850.81   679.7 1852.03   729.5 1877.34     807 1926.14   819.8 1929.93
   842.1 1942.54   853.8 1944.35   877.7 1953.62   904.3 1970.81   917.4 1977.11
#Mann= 3 ,-1,0
       0      .1       0  248.91    .045       0   400.6      .1       0
Bank Sta=248.91,400.6
XS Rating Curve= 0 ,0
Exp/Cntr(USF)=0,0
Exp/Cntr=0.3,0.1

Type RM Length L Ch R = 1 ,106537  ,464.1,429.2,395.4
XS GIS Cut Line= 3
2189908.68696665650971.0296795642190503.85369309650880.416060313
2190680.96213072650863.940856812
#Sta/Elev= 30
       0 1941.65    19.7 1931.58    39.9 1923.61    65.4 1908.51    76.4 1904.97
   116.8  1883.5   145.1 1871.09   157.3 1864.22   169.4 1853.98   181.6 1852.47
   189.6 1849.83   204.81837.365   209.9 1835.16     222 1834.28   304.6 1834.36
  315.111837.368   323.2 1840.65   334.8 1842.62   359.6 1841.88   371.7  1844.8
     400 1847.36   472.9 1848.79   565.9 1847.42   582.1 1848.41   606.4 1864.12
   650.6 1885.68   674.7 1900.68   687.4 1904.24   723.3 1920.89   779.9 1939.81
#Mann= 3 ,-1,0
       0      .1       0   204.8    .045       0  315.11      .1       0
Bank Sta=204.8,315.11
XS Rating Curve= 0 ,0
Exp/Cntr(USF)=0,0
Exp/Cntr=0.3,0.1

Type RM Length L Ch R = 1 ,106108  ,479.8,460.1,439.2
XS GIS Cut Line= 2
2190133.16161434651489.998589819 2190608.8831154651104.890708003
#Sta/Elev= 30
       0 1965.06    39.4 1943.44    50.2 1938.62    59.6 1932.79    70.8 1929.79
    75.9 1927.59   119.3 1904.84   127.9 1901.09   153.1 1881.43   184.7 1853.97
   190.4 1852.58   210.3 1852.67   213.2 1850.84   221.7 1843.13  231.921836.442
   235.9 1833.07   242.9 1832.47   329.8 1832.64   335.5 1833.55  341.891836.444
   364.1 1843.86   382.7 1843.96   395.2 1842.79   433.6 1841.64   461.9 1846.74
   492.8 1849.77   520.3 1850.58   554.5 1854.41   580.1 1861.06   612.1 1871.93
#Mann= 3 ,-1,0
       0      .1       0  231.92    .045       0  341.89      .1       0
#XS Ineff= 2 , 0
                           420.2         1846.87
Permanent Ineff=
       F       F
Bank Sta=231.92,341.89
XS Rating Curve= 0 ,0
Exp/Cntr(USF)=0,0
Exp/Cntr=0.3,0.1

Type RM Length L Ch R = 1 ,105648  ,452.2,434.3,414.5
XS GIS Cut Line= 2
2190553.37650622651831.2513121462190934.74695762651260.608118209
#Sta/Elev= 30
       0 1926.77     7.3 1923.67    16.9 1921.95      41 1912.14    84.3    1891
    98.7 1876.82   118.9 1862.51   130.4 1853.09   159.2 1848.54   176.5 1837.18
   182.3 1836.34   194.9 1836.77   199.7 1835.55   205.4 1832.65   213.8 1832.25
   310.4 1832.26     315 1832.63  321.511835.552   329.6 1839.59   336.2 1840.74
   348.9 1845.86   368.1 1847.73   546.1 1844.47   560.6 1849.29   573.7 1852.16
   584.6 1856.95   613.5 1866.11   623.1 1870.21   637.6 1874.02   686.4 1898.14
#Mann= 3 ,-1,0
       0      .1       0   199.7    .045       0  321.51      .1       0
Bank Sta=199.7,321.51
XS Rating Curve= 0 ,0
Exp/Cntr(USF)=0,0
Exp/Cntr=0.3,0.1

Type RM Length L Ch R = 1 ,105213  ,583.9,578.9,573.1
XS GIS Cut Line= 2
2190973.55268945652125.1518665262191219.32475812651390.660626806
#Sta/Elev= 30
       0 1945.59    46.4 1927.52   122.1 1895.22   147.6  1887.4   182.2 1872.88
   223.5 1860.78   236.2 1849.17   240.4 1847.43   253.1 1846.48   261.5 1842.04
   270.7 1834.19   274.1 1831.76   278.4 1831.53   378.1 1831.36   387.6 1832.08
  392.741834.195   404.9  1838.3   419.2 1839.09   514.6 1837.34   552.5  1835.4
   577.8 1838.89   599.4 1838.39   628.5 1835.76   649.5 1836.82   653.8 1838.56
   670.6 1850.48   704.4 1867.85     717 1875.44   746.6 1889.73   774.5 1901.15
#Mann= 3 ,-1,0
       0      .1       0   270.7    .045       0  392.74      .1       0
Bank Sta=270.7,392.74
XS Rating Curve= 0 ,0
Exp/Cntr(USF)=0,0
Exp/Cntr=0.3,0.1

Type RM Length L Ch R = 1 ,104634  ,523.6,556.7,570.8
XS GIS Cut Line= 4
2191572.44554645652207.0758894182191600.69520952652102.552136074
2191730.64365962651582.7583356562191897.31667171651401.960492033
#Sta/Elev= 30
       0 1873.45    47.5 1859.25    64.1 1858.98    80.7 1854.62   134.4 1847.36
   167.4 1846.58   175.7    1843  191.591831.583   200.4 1828.97   303.5 1829.03
  313.321831.582   324.1 1835.47   336.5 1836.66   372.9  1834.4     456 1833.07
   468.4 1834.53     551 1832.23   571.5 1841.51   608.6 1853.35   668.9 1879.61
   697.2 1889.64   711.5 1890.93     723 1898.12   762.3 1915.81   771.3 1918.07
   796.3 1919.64   807.6 1927.12   869.3 1949.44   882.4 1955.83     890 1956.84
#Mann= 3 ,-1,0
       0      .1       0  191.59    .045       0  313.32      .1       0
Bank Sta=191.59,313.32
XS Rating Curve= 0 ,0
Exp/Cntr(USF)=0,0
Exp/Cntr=0.3,0.1

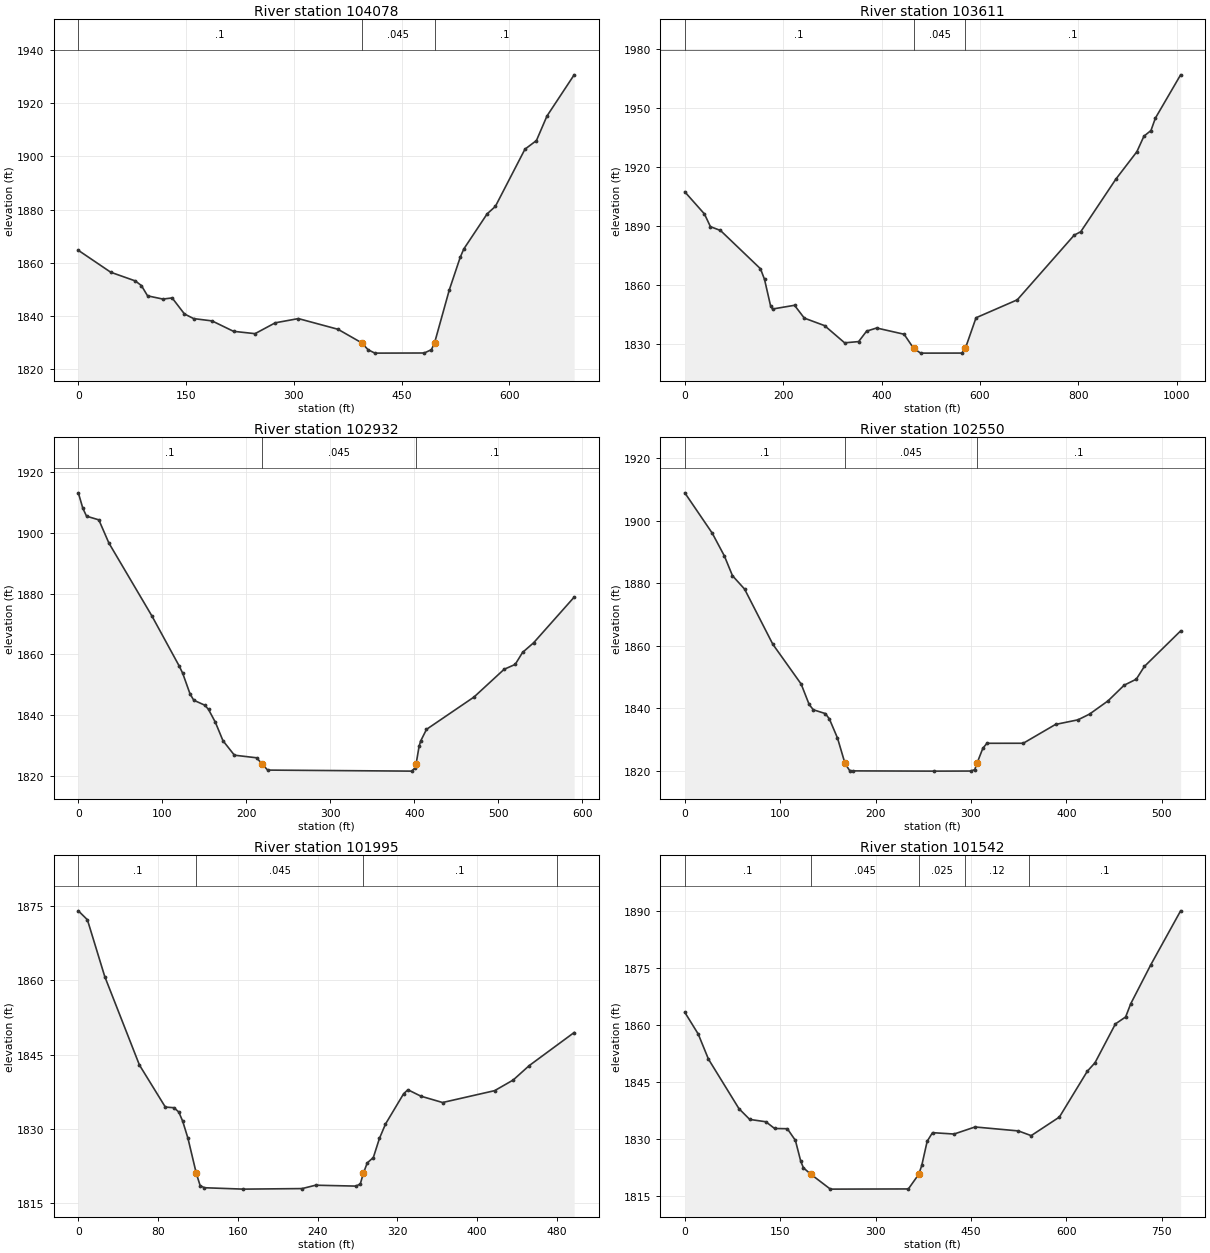
Type RM Length L Ch R = 1 ,104078  ,352.1,466.3,541
XS GIS Cut Line= 3
2191789.96795206652277.7000470842192075.28954903652170.351327432
2192306.93678617651862.430000011
#Sta/Elev= 30
       0 1864.67    45.1 1856.42    79.3 1853.15    87.8  1851.4    96.4 1847.53
   117.7 1846.32   130.6 1846.75   147.7 1840.72   160.5 1838.97   186.1  1838.1
     216 1834.18     246  1833.3   274.1 1837.38   306.3 1838.97   361.4 1834.95
  394.371829.861   403.4 1827.24   412.8 1825.97   481.5 1826.02   491.5 1827.26
  495.91 1829.86   516.5 1849.86   531.6 1862.04   536.6 1865.19   569.1 1878.41
   580.5 1881.19   621.7 1902.74   637.7 1905.99   652.3  1915.2   690.2 1930.73
#Mann= 3 ,-1,0
       0      .1       0  394.37    .045       0  495.91      .1       0
Bank Sta=394.37,495.91
XS Rating Curve= 0 ,0
Exp/Cntr(USF)=0,0
Exp/Cntr=0.3,0.1

Type RM Length L Ch R = 1 ,103611  ,697,679.7,665.8
XS GIS Cut Line= 4
2191744.96122113652478.3767133462192164.27781299652399.782562209
 2192341.9077408652518.5198185662192650.90042717652717.323431966
#Sta/Elev= 30
       0 1907.29    39.9 1896.03    52.1 1889.56    72.5 1887.62   153.8 1868.13
     162 1862.75   174.2 1849.41   178.3 1847.64     223 1849.54   242.9 1843.01
   284.1 1839.19   324.8 1830.44   353.3 1831.06   369.5 1836.38   389.9 1837.98
   445.7  1834.8  465.071827.615   479.4 1825.19   563.1 1825.22  570.171827.612
   591.9 1843.19   675.7 1852.32   791.5 1885.27   804.7 1886.97     876 1913.73
   918.8 1927.72   933.1  1935.6   947.4 1938.49   956.4  1944.8  1007.7 1966.84
#Mann= 3 ,-1,0
       0      .1       0  465.07    .045       0  570.17      .1       0
Bank Sta=465.07,570.17
XS Rating Curve= 0 ,0
Exp/Cntr(USF)=0,0
Exp/Cntr=0.3,0.1

Type RM Length L Ch R = 1 ,102932  ,393.9,381.3,371.6
XS GIS Cut Line= 2
2191575.27051276 652873.767937782192112.01411101653119.540006456
#Sta/Elev= 30
       0 1913.17     5.4 1908.05     9.8 1905.48    24.4 1904.27    36.4 1896.63
    87.7 1872.58   119.8  1856.3   124.2  1853.8     133 1846.97   137.4  1844.9
   150.6 1843.25     155 1841.85   163.2  1837.6   172.2 1831.56   185.8  1826.8
   212.2 1825.94  218.591823.981   225.4 1821.89   396.9 1821.55   401.3 1822.71
  402.171823.972   405.7 1829.73   407.6 1831.48   414.5  1835.3     471 1845.93
   506.9 1855.07   520.1 1856.68   528.9 1860.64   542.1 1863.82   590.3 1878.83
#Mann= 3 ,-1,0
       0      .1       0  218.59    .045       0  402.17      .1       0
Bank Sta=218.59,402.17
XS Rating Curve= 0 ,0
Exp/Cntr(USF)=0,0
Exp/Cntr=0.3,0.1

Type RM Length L Ch R = 1 ,102550  ,545.4,555.2,557.8
XS GIS Cut Line= 2
2191528.94394192653292.2347284182192020.11094627653462.753084645
#Sta/Elev= 30
       0 1908.97    28.8 1896.05    41.5 1888.77      50 1882.44    62.7 1878.16
    92.3 1860.51     122 1847.78   130.4 1841.24   134.7 1839.56   147.4 1838.32
   151.6 1836.61   160.1 1830.51  167.961822.393   172.8 1820.11   176.1 1819.99
   261.7 1819.91   299.8 1819.94     304 1820.38  306.341822.396   312.5 1827.21
   316.8 1828.82   354.9 1828.83   388.7 1834.85   412.3 1836.33   424.4 1838.16
   443.8  1842.4   460.7 1847.41   473.4 1849.33   481.9 1853.41   519.9 1864.78
#Mann= 3 ,-1,0
       0      .1       0  167.96    .045       0  306.34      .1       0
Bank Sta=167.96,306.34
XS Rating Curve= 0 ,0
Exp/Cntr(USF)=0,0
Exp/Cntr=0.3,0.1

Type RM Length L Ch R = 1 ,101995  ,459.6,453.5,446.4
XS GIS Cut Line= 2
2191391.78787278 653809.350178282191849.59259004654003.963519626
#Sta/Elev= 30
       0 1873.98     9.1 1872.18    26.5 1860.74    61.3  1842.9    87.3 1834.42
      96 1834.29   100.8 1833.42   104.7 1831.58     110 1828.12  118.361821.066
   122.2  1818.6   126.5 1818.16   165.6 1817.88   224.5 1817.99   238.1 1818.67
   278.6 1818.49   282.9 1818.92  285.991821.069   289.9 1823.17     296 1824.25
   302.1 1828.09   308.2    1831   326.4 1837.11   330.7 1837.91   343.8 1836.61
   365.5 1835.34   417.7 1837.73   436.3 1839.87   452.4 1842.78   497.5 1849.45
#Mann= 4 ,-1,0
       0      .1       0  118.36    .045       0  285.99      .1       0
     480     .12       0
Bank Sta=118.36,285.99
XS Rating Curve= 0 ,0
Exp/Cntr(USF)=0,0
Exp/Cntr=0.3,0.1

Type RM Length L Ch R = 1 ,101542  ,433.1,349.7,256.7
XS GIS Cut Line= 4
2191151.07181298654254.5209180052191236.64607936654250.017009248
 2191572.9379332654365.6173340072191910.43961308654336.718067723
#Sta/Elev= 30
       0 1863.23    21.1 1857.52    37.2 1850.91    85.2 1837.87   102.1 1835.04
   127.5 1834.42   141.3 1832.65   161.3 1832.59     174 1829.51   182.5 1823.97
   186.7 1822.28  198.451820.588     229 1816.69   351.7 1816.74  368.021820.588
   372.8 1822.94   381.3  1829.3   389.7 1831.55   423.6 1831.19   456.6 1833.05
   524.8 1832.01   544.9 1830.77   589.3 1835.66   633.2 1847.72   645.3 1849.95
   677.4 1860.17   693.5 1862.01   701.5 1865.48   733.1 1875.75     780 1889.94
#Mann= 5 ,-1,0
       0      .1       0  198.45    .045       0  368.02    .025       0
   441.3     .12       0   541.3      .1       0
Bank Sta=198.45,368.02
XS Rating Curve= 0 ,0
Exp/Cntr(USF)=0,0
Exp/Cntr=0.3,0.1

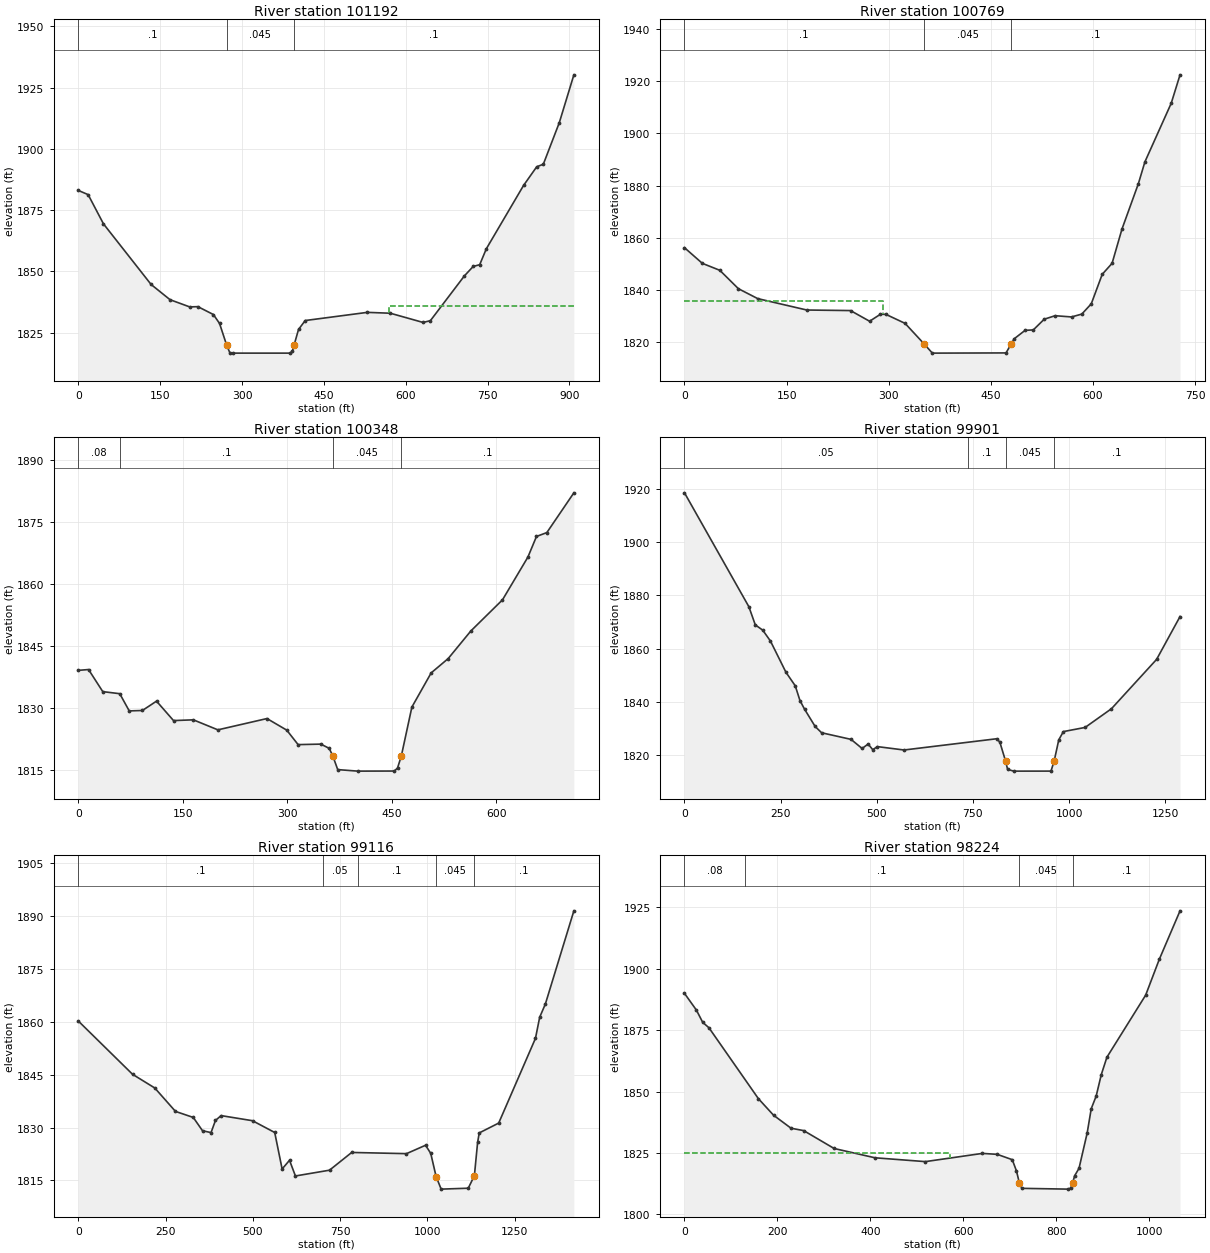
Type RM Length L Ch R = 1 ,101192  ,475.9,422.6,361.6
XS GIS Cut Line= 4
2191226.13695892654826.5173301262191359.75291871654745.446972503
2191764.72041714654400.8132888552191984.00019649654379.788528747
#Sta/Elev= 30
       0 1883.07      18 1881.35    46.1 1869.43   133.4  1844.7   168.1 1838.49
   204.1 1835.55   219.2 1835.65   247.6 1832.43   258.9 1828.78  271.651820.104
   277.6  1816.9   282.9 1816.69   387.9 1816.69   392.3 1817.36  395.651820.103
   403.6 1826.34   415.9 1829.99   529.8 1833.32   571.8 1832.97   631.9 1829.21
   645.3 1829.93   707.6 1848.19   723.7 1852.04   735.7 1852.77   747.8 1859.24
   816.1 1885.11   840.2 1892.72   852.3 1893.75   881.6 1910.72   908.3 1930.23
#Mann= 3 ,-1,0
       0      .1       0  271.65    .045       0  395.65      .1       0
#XS Ineff= 2 , 0
                           569.8         1835.99
Permanent Ineff=
       F       F
Bank Sta=271.65,395.65
XS Rating Curve= 0 ,0
Exp/Cntr(USF)=0,0
Exp/Cntr=0.3,0.1

Type RM Length L Ch R = 1 ,100769  ,414.9,421.7,428.7
XS GIS Cut Line= 4
2191865.11179547655114.9422185882191884.26028966655016.008331943
2191913.78088487654534.1045615142191994.38505881654414.364522903
#Sta/Elev= 30
       0 1856.19    26.2 1850.19    51.9 1847.52    79.2 1840.47   107.6 1836.67
   179.7  1832.3   243.9 1832.09   271.9    1828   287.9 1830.69   295.9 1830.63
     324 1827.19  351.62 1819.41   364.1 1815.78   472.3 1815.86  480.141819.409
   484.3 1821.28   500.3 1824.51   512.4 1824.68   528.4 1828.78   544.4 1830.12
   568.5 1829.65   583.6 1830.74   597.5 1834.67   613.6 1845.98   628.1 1850.21
   642.6 1863.32   666.7 1880.72   676.3 1889.09   714.9 1911.51   727.9 1922.44
#Mann= 3 ,-1,0
       0      .1       0  351.62    .045       0  480.14      .1       0
#XS Ineff= 2 , 0
          291.28 1835.83
Permanent Ineff=
       F       F
Bank Sta=351.62,480.14
XS Rating Curve= 0 ,0
Exp/Cntr(USF)=0,0
Exp/Cntr=0.3,0.1

Type RM Length L Ch R = 1 ,100348  ,451.8,446.4,442.3
XS GIS Cut Line= 3
 2192249.6773871655135.6864206262192348.61127375654591.550044081
2192314.30355499654436.766382718
#Sta/Elev= 30
       0  1839.2    14.7  1839.4    35.1 1834.06    59.5 1833.56    73.1  1829.4
      92  1829.5   112.3 1831.76   136.7 1827.06   165.2 1827.24   200.4 1824.82
   270.9 1827.55   299.3 1824.75   315.6 1821.25   348.3 1821.37   360.3 1820.34
  365.471818.485   372.5 1815.21     401 1814.84   453.8 1814.86   458.4  1815.6
   463.81818.486     479 1830.33   506.7 1838.59   531.1 1842.05   563.7 1848.73
   609.1 1856.25   645.6 1866.59   657.9 1871.57   672.8 1872.51   711.6 1882.12
#Mann= 4 ,-1,0
       0     .08       0      60      .1       0  365.47    .045       0
   463.8      .1       0
Bank Sta=365.47,463.8
XS Rating Curve= 0 ,0
Exp/Cntr(USF)=0,0
Exp/Cntr=0.3,0.1

Type RM Length L Ch R = 1 ,99901   ,721.8,785.4,830.4
XS GIS Cut Line= 4
 2192539.5355586655655.0678982812192674.28645142655525.401944808
2192793.78252619 654549.093589242192857.34426809654449.937271878
#Sta/Elev= 30
       0 1918.53   167.4 1875.73   184.1  1868.9   203.5 1866.91   223.5 1862.83
   263.8 1851.09     288    1846   300.2 1840.47   312.2 1837.21   339.7 1830.72
   356.5 1828.36   433.1 1825.87   461.8 1822.45   477.4 1824.12   489.5    1822
   501.6 1823.15   570.8 1821.88   811.9 1826.11   819.9 1824.84  834.731817.757
   840.1 1814.58   856.2 1813.94   952.9 1813.95  961.171817.761   973.1 1825.69
   985.1  1828.8  1041.6 1830.36  1110.1 1837.39  1227.5 1855.94  1288.4 1872.04
#Mann= 4 ,-1,0
       0     .05       0  737.01      .1       0  834.73    .045       0
  961.17      .1       0
Bank Sta=834.73,961.17
XS Rating Curve= 0 ,0
Exp/Cntr(USF)=0,0
Exp/Cntr=0.3,0.1

Type RM Length L Ch R = 1 ,99116   ,882.6,892.1,898
XS GIS Cut Line= 4
2193057.12874366656027.7425021782193380.97944793655107.492630374
2193532.12283495654995.9431711342193784.85472114655035.820261918
#Sta/Elev= 30
       0  1860.2   155.4 1845.09     219 1841.21   278.3 1834.57   329.2 1832.86
   355.7 1829.09   380.1 1828.56   392.8 1832.01     409 1833.38   498.9 1831.93
   562.5 1828.59   583.7 1818.24   604.9 1820.71   621.8 1816.26   719.4  1817.9
     783 1822.93   939.9 1822.59   994.5 1824.97  1009.4 1822.66  1024.7 1816.11
  1039.2 1812.53  1116.8 1812.79 1134.381816.344  1143.6 1825.78  1148.3 1828.47
    1204 1831.26  1309.3 1855.29  1321.4 1861.28  1337.6 1865.01  1419.3 1891.45
#Mann= 5 ,-1,0
       0      .1       0     700     .05       0     800      .1       0
  1024.7    .045       0 1134.38      .1       0
Bank Sta=1024.7,1134.38
XS Rating Curve= 0 ,0
Exp/Cntr(USF)=0,0
Exp/Cntr=0.3,0.1

Type RM Length L Ch R = 1 ,98224   ,483.9,484.8,484.9
XS GIS Cut Line= 3
2193479.78287287656255.8120779792193636.74478247655959.136776244
2194268.12775664655592.010837151
#Sta/Elev= 30
       0 1889.99    25.6 1883.19    39.2 1878.19    52.6 1875.98   159.1 1847.06
   191.6 1840.34   229.2 1835.04   256.4 1834.07   321.9 1826.78   409.8 1822.99
   518.1 1821.43   640.9 1824.78   672.8 1824.39   705.1 1822.22   714.1 1817.65
  720.32 1812.79   725.8 1810.54   824.9 1810.22   831.1 1810.65  835.071812.791
   839.3 1815.67   848.7  1818.7   866.2 1833.05     875 1843.01   885.6 1848.14
   896.6 1856.89   908.7 1863.97   992.1 1889.29  1021.3 1903.83    1066 1923.63
#Mann= 4 ,-1,0
       0     .08       0     130      .1       0  720.32    .045       0
  835.07      .1       0
#XS Ineff= 2 , 0
           571.1 1825.01
Permanent Ineff=
       F       F
Bank Sta=720.32,835.07
XS Rating Curve= 0 ,0
Exp/Cntr(USF)=0,0
Exp/Cntr=0.3,0.1

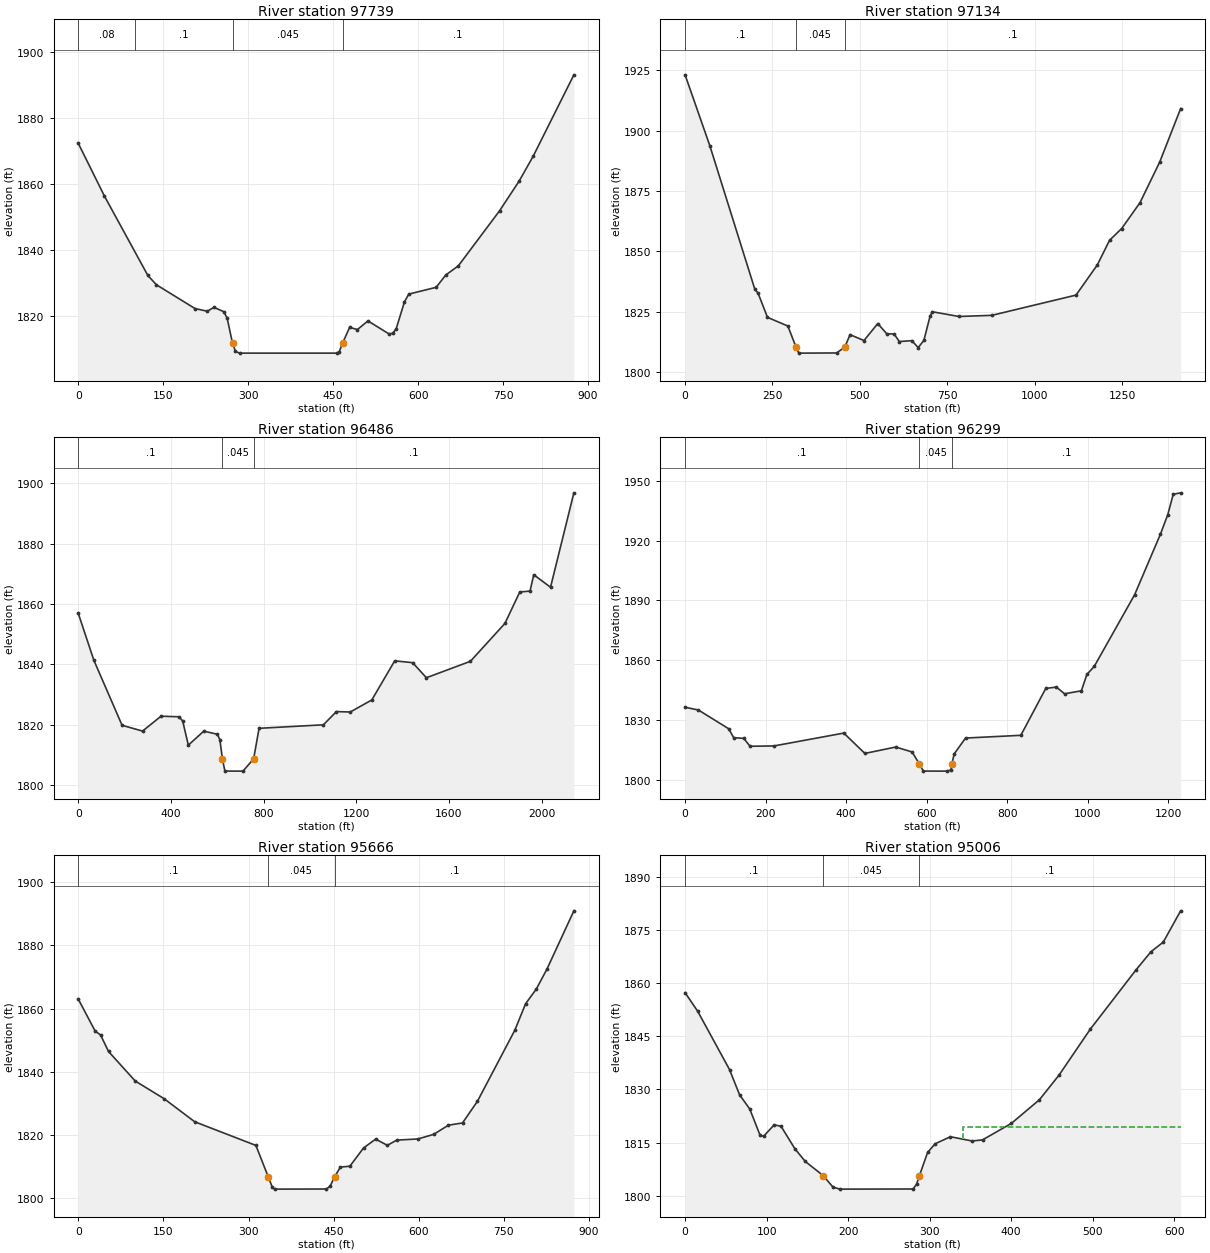
Type RM Length L Ch R = 1 ,97739   ,609.6,605,611.5
XS GIS Cut Line= 4
2193969.72063324656371.9244777192194056.83327175656271.837616455
2194522.05183059656001.2323989642194594.33678595655810.325978406
#Sta/Elev= 30
       0 1872.41    46.2 1856.43   122.8  1832.4     138 1829.58     206 1822.39
   227.8 1821.57   239.5 1822.75     257 1821.43   262.9 1819.39  272.281811.843
   277.5 1809.42   284.6 1808.88   456.2 1808.88   460.5 1809.19  466.461811.849
     479 1816.67   492.9 1816.03   511.4 1818.64   548.4 1814.71   555.4 1814.89
   561.3 1816.29   575.9 1824.44   583.5 1826.76   631.7 1828.81   649.1 1832.59
   670.9  1835.3   743.7 1851.98   778.1 1860.93   802.9 1868.45     875 1893.19
#Mann= 4 ,-1,0
       0     .08       0     100      .1       0  272.28    .045       0
  466.46      .1       0
Bank Sta=272.28,466.46
XS Rating Curve= 0 ,0
Exp/Cntr(USF)=0,0
Exp/Cntr=0.3,0.1

Type RM Length L Ch R = 1 ,97134   ,644.2,648,653.2
XS GIS Cut Line= 4
2194270.10069791656810.2185726362194366.18408473656772.685999662
2195104.63297601656396.0511118492195296.61086441655950.369328247
#Sta/Elev= 30
       0 1923.11    70.9 1893.69   199.7 1834.17   208.7 1832.66   235.6 1822.63
     294 1819.01  317.391810.253   325.4 1807.79   433.2 1807.86  456.821810.235
   471.8 1815.45   511.6    1813   551.1 1820.04   576.9 1815.82   597.9 1815.71
   612.8 1812.59   648.7 1812.96   666.7 1810.09   683.1 1813.09   700.7 1823.09
   707.1 1824.94   783.4 1822.97   877.4 1823.45  1118.2 1831.84  1179.1 1844.34
    1214 1854.53  1248.8 1859.43  1301.1 1870.11  1357.7 1887.02  1417.4 1909.13
#Mann= 3 ,-1,0
       0      .1       0  317.39    .045       0  456.82      .1       0
Bank Sta=317.39,456.82
XS Rating Curve= 0 ,0
Exp/Cntr(USF)=0,0
Exp/Cntr=0.3,0.1

Type RM Length L Ch R = 1 ,96486   ,154.7,186.7,231.3
XS GIS Cut Line= 4
2194368.43172212657124.1205816482194767.04446993657253.251385366
2195652.93747286656881.5245252852196408.41240137656959.818310465
#Sta/Elev= 30
       0 1856.84      67 1841.36   188.9 1819.79   277.2 1817.87   357.1  1822.8
   435.2 1822.61   450.6 1821.19   474.9 1813.21   541.7 1817.85   600.4 1816.82
   611.1 1815.02  621.931808.693   632.8 1804.62   710.9  1804.6   756.91808.693
   780.3 1818.79  1057.9 1819.95  1114.3 1824.34  1173.9 1824.19  1266.9 1828.18
  1365.9 1841.15  1443.3 1840.54  1502.6 1835.55  1692.6 1840.99  1841.5 1853.54
  1905.8 1863.96    1950 1864.27  1966.1 1869.68  2038.5 1865.54  2139.3 1896.83
#Mann= 3 ,-1,0
       0      .1       0  621.93    .045       0   756.9      .1       0
Bank Sta=621.93,756.9
XS Rating Curve= 0 ,0
Exp/Cntr(USF)=0,0
Exp/Cntr=0.3,0.1

Type RM Length L Ch R = 1 ,96299   ,556.4,633.2,676.7
XS GIS Cut Line= 4
 2194404.2959761 657205.046846092194737.76909037657302.287936497
2195196.36677192 657360.075616612195398.61248987657729.345007526
#Sta/Elev= 30
       0 1836.42    33.2 1835.02   108.2 1825.64   120.7 1821.16   145.7 1820.81
   161.3 1816.86   220.7 1817.01   394.1 1823.46   446.5 1813.26   523.1 1816.46
   563.6    1814  581.691808.036   591.7 1804.41   651.3 1804.38   660.2 1804.98
  662.531808.032   668.3 1813.03   696.5 1820.97   833.8 1822.34   895.7 1845.87
   922.2 1846.52   942.4 1843.16   984.1 1844.67   997.8 1852.86  1016.1 1856.92
  1116.4 1892.87  1180.3 1923.17  1198.5 1932.89  1212.2 1943.22  1230.6 1943.96
#Mann= 3 ,-1,0
       0      .1       0  581.69    .045       0  662.53      .1       0
Bank Sta=581.69,662.53
XS Rating Curve= 0 ,0
Exp/Cntr(USF)=0,0
Exp/Cntr=0.3,0.1

Type RM Length L Ch R = 1 ,95666   ,663.5,660.2,650.5
XS GIS Cut Line= 4
2194281.51841907657226.0400367782194420.36623299657376.729747484
2194545.12167507657847.9789689112194641.38934748658001.248346198
#Sta/Elev= 30
       0 1862.98    29.6 1852.89    39.3 1851.61    53.2 1846.41   100.3 1837.04
   151.3 1831.43   205.1 1824.13     313 1816.63  334.631806.711   341.9 1803.39
   346.1 1802.78   437.4 1802.82   443.9 1803.74  451.771806.711   461.9 1809.77
   478.5 1810.03   502.8 1815.84     524 1818.63   544.7 1816.66   561.2 1818.31
   598.5 1818.68   626.2 1820.13   652.3 1823.05   677.1 1823.75   703.3 1830.58
   769.4 1853.17   788.3 1861.54   807.2 1866.19   826.1 1872.57   873.4 1890.98
#Mann= 3 ,-1,0
       0      .1       0  334.63    .045       0  451.77      .1       0
Bank Sta=334.63,451.77
XS Rating Curve= 0 ,0
Exp/Cntr(USF)=0,0
Exp/Cntr=0.3,0.1

Type RM Length L Ch R = 1 ,95006   ,419.4,394.3,371.9
XS GIS Cut Line= 2
2193792.65404616657610.7487322822194002.71289078658181.202653477
#Sta/Elev= 30
       0 1857.34    15.4 1852.12    54.5 1835.62    66.9 1828.47    79.4 1824.45
    92.1 1816.99    96.4 1816.78   109.2 1819.99   117.7 1819.61   134.7 1813.24
   147.5 1809.65  169.281805.684   181.6 1802.37   190.1 1801.84   279.7 1801.88
   283.9 1803.19  287.541805.688   297.5  1812.2   306.8 1814.66   325.5 1816.64
   352.1 1815.44   364.9 1815.75   400.3 1820.42   434.6 1827.07   458.7 1834.04
     497    1847   552.9  1863.7   571.6 1868.93   586.6 1871.62   607.9 1880.46
#Mann= 3 ,-1,0
       0      .1       0  169.28    .045       0  287.54      .1       0
#XS Ineff= 2 , 0
                          340.99         1819.41
Permanent Ineff=
       F       F
Bank Sta=169.28,287.54
XS Rating Curve= 0 ,0
Exp/Cntr(USF)=0,0
Exp/Cntr=0.3,0.1

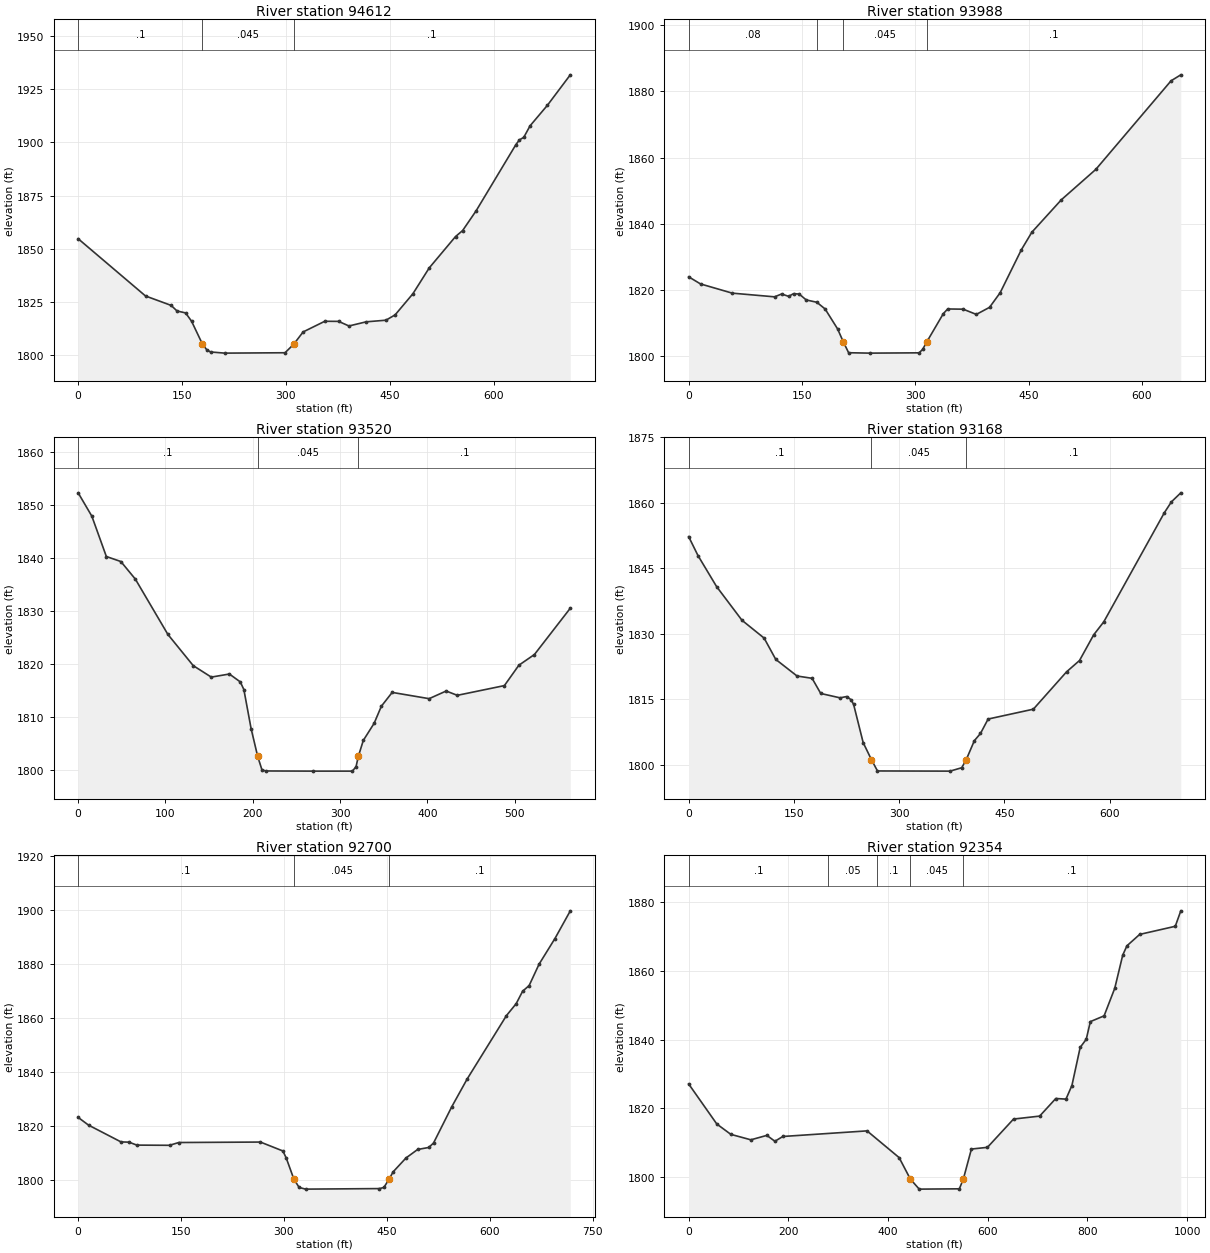
Type RM Length L Ch R = 1 ,94612   ,649.6,623.3,598.4
XS GIS Cut Line= 2
 2193368.3619286657812.172945327 2193813.2941219658366.431334686
#Sta/Elev= 30
       0 1854.73    97.3 1827.86   134.3 1823.44   142.8 1820.82   155.2 1819.91
   163.8 1816.01  179.56 1805.24   185.9 1802.56   191.2 1801.59   211.6 1801.04
   298.8 1801.22   311.41805.237   324.9 1810.98   356.2 1815.99   376.2 1815.94
   391.1 1813.78     416 1815.73   444.5 1816.49   457.8    1819   483.5 1828.92
     507 1841.01     545 1855.73   555.3 1858.57   574.8 1867.84   632.2 1898.88
   637.3  1901.1   643.6 1902.31   652.7 1907.72   677.8 1917.37   710.8 1931.64
#Mann= 3 ,-1,0
       0      .1       0  179.56    .045       0   311.4      .1       0
Bank Sta=179.56,311.4
XS Rating Curve= 0 ,0
Exp/Cntr(USF)=0,0
Exp/Cntr=0.3,0.1

Type RM Length L Ch R = 1 ,93988   ,514.5,468.8,407.3
XS GIS Cut Line= 3
2192910.71738693658356.2614559822193317.51253508658600.338544874
2193492.94294273 658577.45631779
#Sta/Elev= 30
       0 1823.87    15.7 1821.71    57.7 1818.92   113.7  1817.8     123 1818.66
   132.3 1817.95   138.8 1818.76   146.3 1818.64   155.6 1816.86   169.6 1816.16
   180.6 1814.12   197.1 1808.09  204.571804.217   211.7 1800.87   239.6 1800.75
   304.9 1800.84   309.6 1801.85  315.291804.216     337  1812.7   342.8 1814.13
   363.3 1814.06   380.7 1812.48   398.2 1814.62   412.2 1819.03   440.2 1832.02
   454.2 1837.38   493.2  1847.2   538.8  1856.4   638.4 1883.24   651.3 1885.05
#Mann= 4 ,-1,0
       0     .08       0     170      .1       0  204.57    .045       0
  315.29      .1       0
Bank Sta=204.57,315.29
XS Rating Curve= 0 ,0
Exp/Cntr(USF)=0,0
Exp/Cntr=0.3,0.1

Type RM Length L Ch R = 1 ,93520   ,371.1,351.7,327.4
XS GIS Cut Line= 2
2192836.98576633659007.1336930272193381.07427698658859.670451822
#Sta/Elev= 30
       0 1852.27    15.7 1847.87    32.3 1840.28    48.9 1839.34    65.5 1836.03
   102.8 1825.61   131.8 1819.74   152.5 1817.58   173.2 1818.16   185.7 1816.68
   189.8 1815.24   198.1 1807.88  205.641802.641   210.5 1800.14   214.7 1799.91
   268.5 1799.88   314.1 1799.88   318.3 1800.72  320.89 1802.64   326.6 1805.66
     339 1808.88   347.3  1812.1   359.7  1814.7     402 1813.52   421.5 1814.96
   434.3 1814.15   488.2 1815.98   504.8 1819.82   522.6 1821.83   563.7 1830.55
#Mann= 3 ,-1,0
       0      .1       0  205.64    .045       0  320.89      .1       0
Bank Sta=205.64,320.89
XS Rating Curve= 0 ,0
Exp/Cntr(USF)=0,0
Exp/Cntr=0.3,0.1

Type RM Length L Ch R = 1 ,93168   ,464.2,468.2,469.8
XS GIS Cut Line= 2
2193013.11399313659407.4150713872193595.33954892 659015.87474129
#Sta/Elev= 30
       0 1852.27    13.3 1847.93    39.8 1840.83      76 1833.11   107.6 1829.02
   124.2 1824.14   154.5 1820.34     176 1819.81   188.3 1816.34   215.8 1815.34
   225.4 1815.64   231.5  1814.9   235.1 1813.87   248.8 1805.08  260.581801.173
   269.2 1798.59   372.7 1798.55   389.3 1799.33  395.721801.174   407.3 1805.53
     416 1807.17   426.9 1810.48   491.4 1812.74   538.7 1821.29   557.2 1823.89
   577.4 1829.77   591.8 1832.75   678.2 1857.76   688.2 1860.23   701.6  1862.3
#Mann= 3 ,-1,0
       0      .1       0  260.58    .045       0  395.72      .1       0
Bank Sta=260.58,395.72
XS Rating Curve= 0 ,0
Exp/Cntr(USF)=0,0
Exp/Cntr=0.3,0.1

Type RM Length L Ch R = 1 ,92700   ,313.5,345.6,370.4
XS GIS Cut Line= 2
2193267.36096072659778.6156440772193875.01121328659397.245192684
#Sta/Elev= 30
       0 1823.15    15.1  1820.3    62.4 1814.08    74.2 1813.98    85.5 1812.89
   133.2 1812.82   146.7 1813.85   265.7 1814.02   298.5 1810.71   303.4 1808.05
  314.391800.344   322.1 1797.21   331.5 1796.59   439.1 1796.79   445.6  1797.2
  453.421800.342     459 1802.95   477.9 1808.13   494.9 1811.28     511 1812.01
     518 1813.65   544.5 1827.04     567 1837.35   624.3 1860.84   638.5 1865.26
   647.9 1869.88   657.4 1871.97   671.9  1879.9     695 1889.38   717.4 1899.64
#Mann= 3 ,-1,0
       0      .1       0  314.39    .045       0  453.42      .1       0
Bank Sta=314.39,453.42
XS Rating Curve= 0 ,0
Exp/Cntr(USF)=0,0
Exp/Cntr=0.3,0.1

Type RM Length L Ch R = 1 ,92354   ,374,403.3,420.3
XS GIS Cut Line= 4
2193267.92155344659916.9839365552193564.47521645659890.211730867
2193988.71170658659840.7861203672194246.13676127659892.271131305
#Sta/Elev= 30
       0 1827.08    56.5 1815.42    84.6 1812.41   124.8 1810.82   156.9 1812.11
     173  1810.4     189 1811.79   357.9 1813.42   422.3 1805.64  444.761799.401
   462.6 1796.47   543.1 1796.56  551.091799.402   567.3 1808.13   599.5 1808.63
   651.8 1816.86   704.2 1817.72   736.6 1822.84     757 1822.66   768.9 1826.61
   785.5  1837.7   797.7 1840.08   805.9 1845.21   833.5 1846.89   854.9 1854.92
   870.9 1864.57   879.3 1867.27   904.9 1870.59   976.3 1872.95   987.4 1877.45
#Mann= 5 ,-1,0
       0      .1       0     280     .05       0  377.76      .1       0
  444.76    .045       0  551.09      .1       0
Bank Sta=444.76,551.09
XS Rating Curve= 0 ,0
Exp/Cntr(USF)=0,0
Exp/Cntr=0.3,0.1