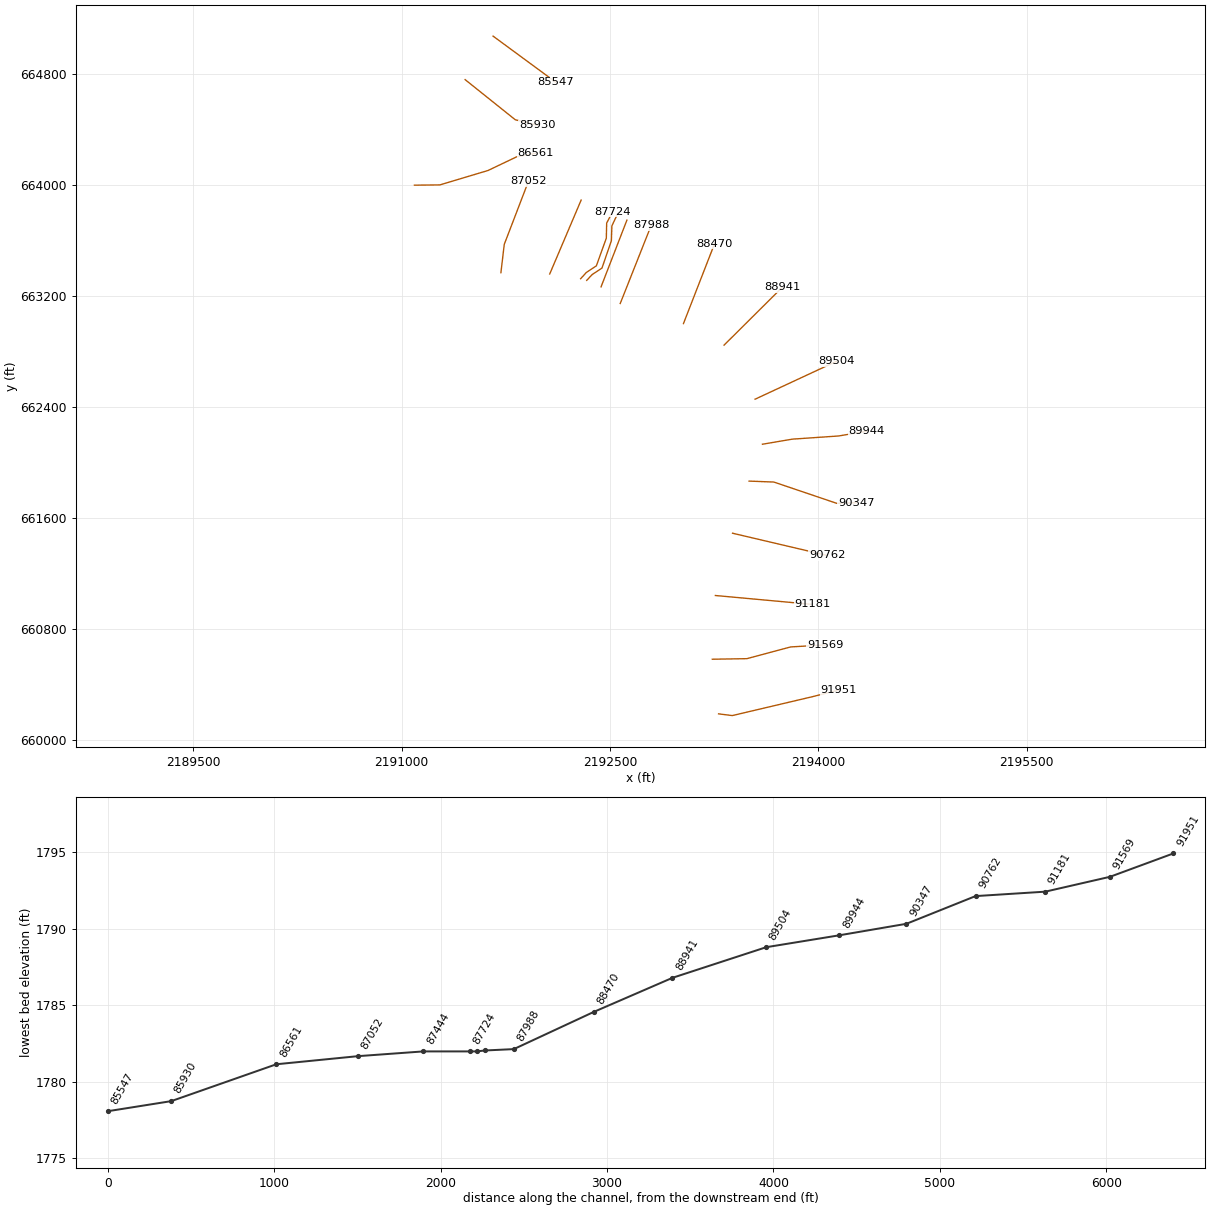
HEC-RAS study BUCKHANR_U.prj: BUCKHANR_U

--- BUCKHANR_U.g01 (geometry) --- (continued)

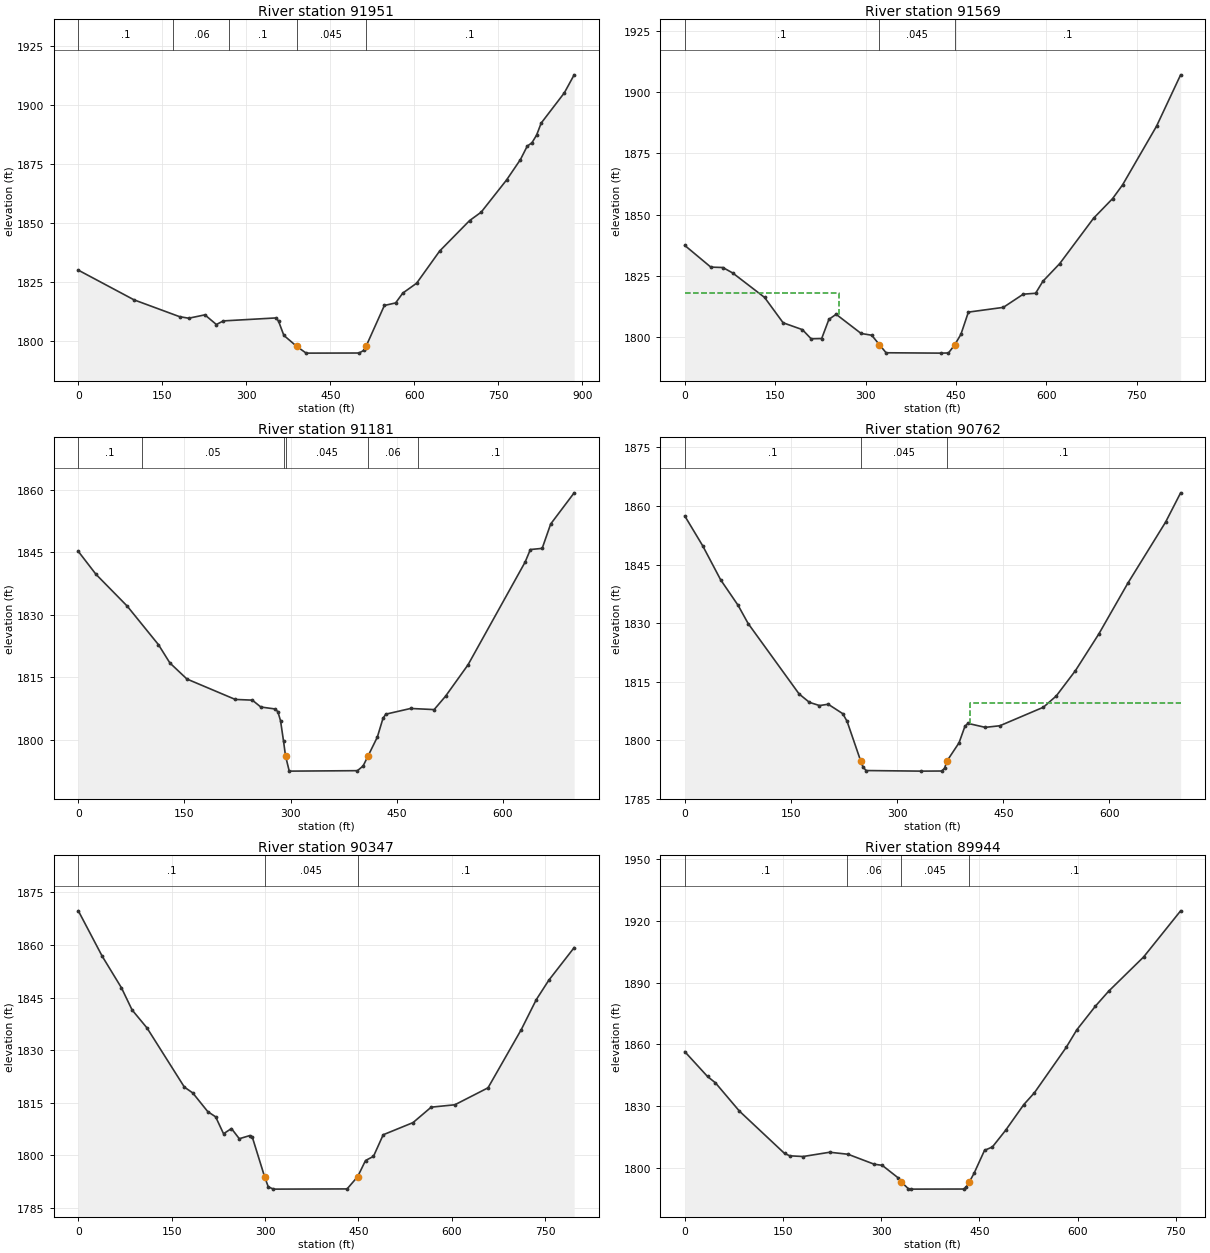
Type RM Length L Ch R = 1 ,91951   ,377.3,381.5,381.6
XS GIS Cut Line= 4
2193282.33735651660190.8841947462193381.18857751660178.527792121
2193957.82070001660314.4482209982194145.22613983660361.814431061
#Sta/Elev= 30
       0 1830.11    99.6  1817.5   180.9 1810.37   197.2 1809.72     226 1811.15
   246.5 1807.05   258.9 1808.58   353.4 1809.85   357.5 1808.48     367 1802.44
  389.851797.796   406.8 1794.91   501.3 1794.96   509.5 1796.03  513.781797.792
   546.5 1815.13   566.6 1816.21   579.4 1820.39   604.1 1824.57   645.2 1838.22
   698.6 1851.13   719.3  1854.7   764.6 1868.34   789.4 1877.01   801.6 1882.73
     810 1884.16   818.3 1887.39   826.5  1892.5   867.8 1905.32   885.4 1912.98
#Mann= 5 ,-1,0
       0      .1       0  169.62     .06       0  269.62      .1       0
  389.85    .045       0  513.78      .1       0
Bank Sta=389.85,513.78
XS Rating Curve= 0 ,0
Exp/Cntr(USF)=0,0
Exp/Cntr=0.3,0.1

Type RM Length L Ch R = 1 ,91569   ,414,388.6,363.6
XS GIS Cut Line= 4
2193237.03054688660584.2296783132193486.21799982660588.348479189
2193801.30626676660672.7838971272194048.43431927 660687.19970019
#Sta/Elev= 30
       0  1837.4    43.2 1828.53    63.2 1828.37    79.5 1826.14   132.4 1816.15
   163.2 1805.78   195.2 1802.98   209.7 1799.24   227.2 1799.34   239.2 1807.19
   251.2 1809.25   292.7 1801.41   310.3 1800.69  323.061796.821   334.1 1793.53
   424.6 1793.38   437.7 1793.45  448.16 1796.82   458.3 1801.06   470.7 1810.14
   528.7 1812.08   561.8 1817.47   582.3 1817.85   594.3 1822.72   622.4 1829.99
   678.5 1848.51     710 1856.51   726.6 1862.13     783 1886.12     823 1907.12
#Mann= 3 ,-1,0
       0      .1       0  323.06    .045       0  448.16      .1       0
#XS Ineff= 2 , 0
          256.04 1817.99
Permanent Ineff=
       F       F
Bank Sta=323.06,448.16
XS Rating Curve= 0 ,0
Exp/Cntr(USF)=0,0
Exp/Cntr=0.3,0.1

Type RM Length L Ch R = 1 ,91181   ,427.9,418.8,408.8
XS GIS Cut Line= 2
2193259.35155895661043.040024291  2193957.259485660978.969788457
#Sta/Elev= 30
       0 1845.18    24.9 1839.69    69.1 1832.04   113.3 1822.77   129.4 1818.39
   153.5 1814.53   221.8 1809.63   245.9 1809.46   257.9 1807.81     278 1807.34
     282 1806.69   285.8 1804.51     290 1799.65  292.85 1796.06   298.1 1792.41
   394.5 1792.52   402.5 1793.65  409.511796.056   422.6 1800.58   430.6 1805.09
   434.6 1806.09   469.7 1807.46   502.9 1807.19     519  1810.4   550.7 1817.92
   631.5 1842.62   638.9 1845.63   655.6 1845.91   667.6 1851.76   700.8 1859.25
#Mann= 6 ,-1,0
       0      .1       0      90     .05       0     290     .06       0
  292.85    .045       0  409.51     .06       0     480      .1       0
Bank Sta=292.85,409.51
XS Rating Curve= 0 ,0
Exp/Cntr(USF)=0,0
Exp/Cntr=0.3,0.1

Type RM Length L Ch R = 1 ,90762   ,423.6,415.3,414.2
XS GIS Cut Line= 2
 2193382.9155852 661491.531675132194064.80595229661331.356085545
#Sta/Elev= 30
       0 1857.46    25.4 1849.79    50.6 1841.13    75.3 1834.58    89.5 1829.92
   161.5 1811.88     176 1809.74   190.3 1808.91   202.6 1809.25   223.2 1806.83
   229.3 1804.86  248.58 1794.68   251.9  1793.1   256.3 1792.27   334.1 1792.12
   362.9 1792.15     367 1792.86  370.281794.679   387.5 1799.39   395.7 1803.57
   399.9 1804.35   424.5 1803.33   445.1 1803.74   506.7 1808.49   524.8 1811.37
   551.9 1817.86   584.8 1827.21   625.8 1840.21   679.3  1855.9   700.5 1863.39
#Mann= 3 ,-1,0
       0      .1       0  248.58    .045       0  370.28      .1       0
#XS Ineff= 2 , 0
                          403.22         1809.55
Permanent Ineff=
       F       F
Bank Sta=248.58,370.28
XS Rating Curve= 0 ,0
Exp/Cntr(USF)=0,0
Exp/Cntr=0.3,0.1

Type RM Length L Ch R = 1 ,90347   ,379.1,402.3,428.9
XS GIS Cut Line= 4
2193501.90316604661866.8001993012193680.38453729661859.935531176
2194133.45263354661706.6246097162194273.03421875661711.201055133
#Sta/Elev= 30
       0 1869.76    38.3 1856.82    69.3 1847.78    86.3 1841.48   110.4 1836.31
   170.4 1819.43   183.8 1817.78     208 1812.43   220.6 1810.95   233.3 1806.12
     246 1807.61   258.6  1804.7   275.3 1805.59   279.7 1805.05  299.171793.899
   305.1 1790.98   313.5 1790.31   431.8 1790.37  448.87  1793.9   461.4 1798.48
   474.2 1799.67   489.8 1805.83   537.7  1809.3   566.9 1813.71   604.9 1814.39
   658.2 1819.23   711.7 1835.88   735.7 1844.39   755.7 1849.91   796.6 1859.26
#Mann= 3 ,-1,0
       0      .1       0  299.17    .045       0  448.87      .1       0
Bank Sta=299.17,448.87
XS Rating Curve= 0 ,0
Exp/Cntr(USF)=0,0
Exp/Cntr=0.3,0.1

Type RM Length L Ch R = 1 ,89944   ,416.3,440.1,463
XS GIS Cut Line= 4
2193598.00851979662132.2340334712193813.10145437662168.845596805
2194147.18196979662191.7278238892194348.54556813662226.051164514
#Sta/Elev= 30
       0 1856.45    34.7 1844.37    46.8 1841.29    83.3 1827.56   152.3 1806.94
   160.4 1805.77   180.7 1805.43   221.3 1807.51   249.3 1806.53   289.4 1801.67
   301.5 1801.15   325.5 1795.14  330.551793.076   341.5 1789.75   345.6 1789.56
   425.7 1789.61   429.8 1790.45   434.61793.075   441.8 1797.26   457.8 1808.43
   469.8 1810.08   489.9 1818.15   517.8 1830.71     534 1836.46   582.5 1858.51
   598.7 1867.06   627.1 1878.58   647.4 1885.88   700.8 1902.54   757.3 1924.98
#Mann= 4 ,-1,0
       0      .1       0  248.19     .06       0  330.55    .045       0
   434.6      .1       0
Bank Sta=330.55,434.6
XS Rating Curve= 0 ,0
Exp/Cntr(USF)=0,0
Exp/Cntr=0.3,0.1

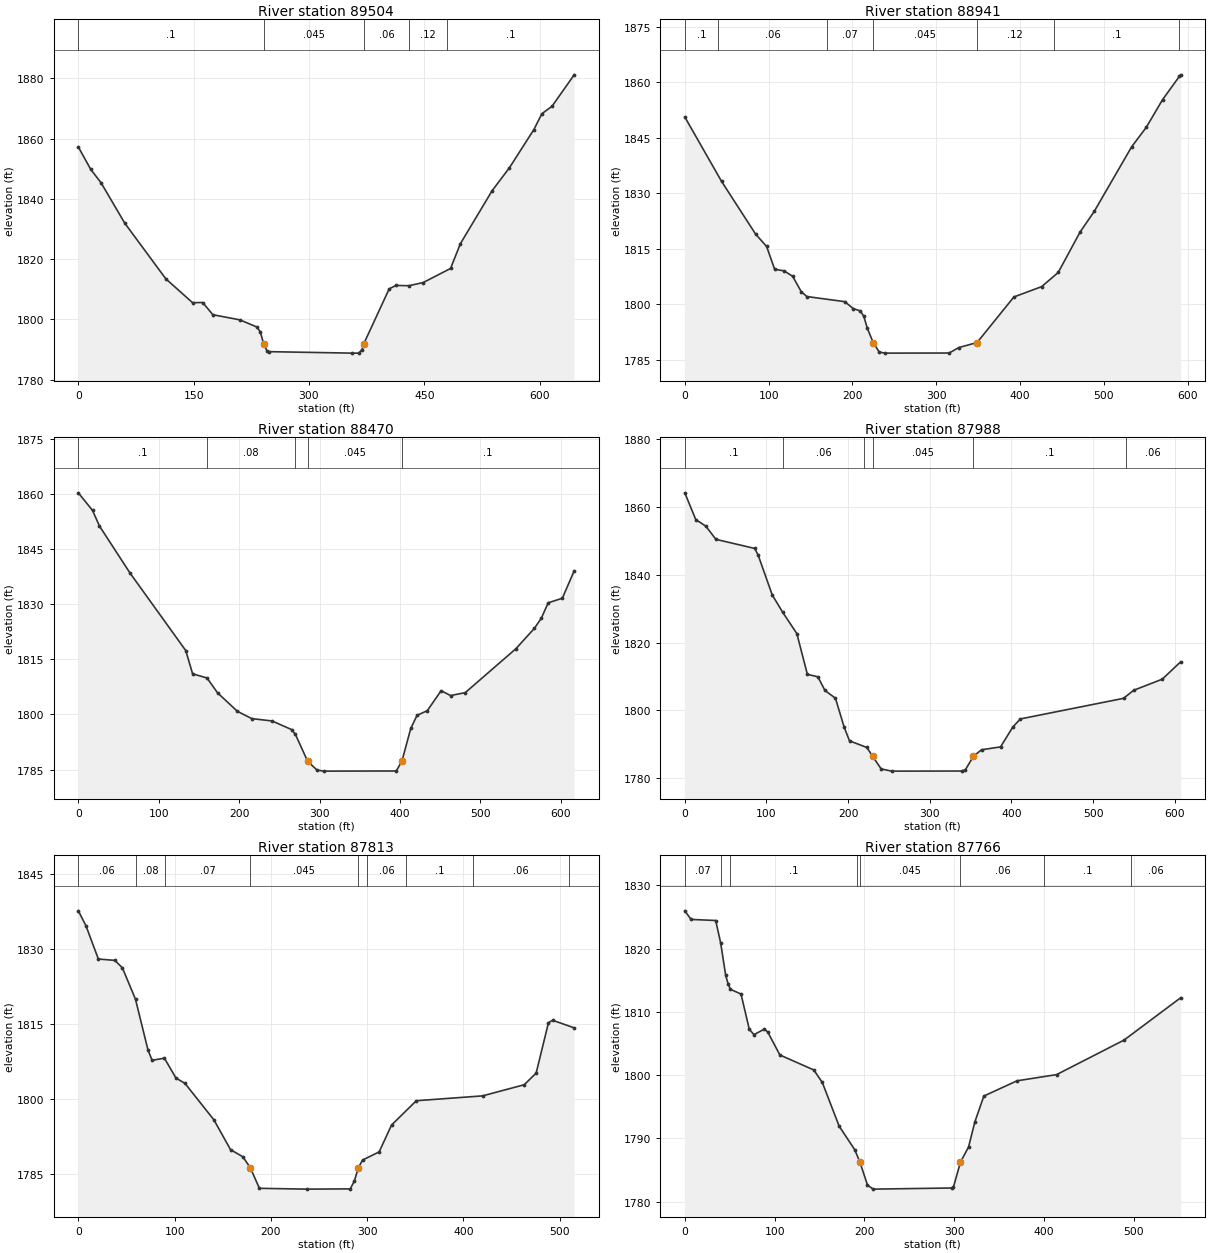
Type RM Length L Ch R = 1 ,89504   ,530.9,563,582.5
XS GIS Cut Line= 2
2193545.47653636662456.6388070242194130.24456183662728.683062351
#Sta/Elev= 30
       0  1857.2    16.2 1849.73    29.5 1845.34    60.3 1831.95   113.8 1813.44
   148.6 1805.52   161.8 1805.58     175 1801.53   210.3 1799.81   232.4 1797.43
   236.8 1795.77  241.071791.874   245.6 1789.43   247.8 1789.27   355.9 1788.78
   364.7 1788.78   369.1 1789.96  371.311791.876   404.4 1810.12   413.3 1811.25
     430 1811.15   448.6  1812.2   484.2 1816.88   497.1 1825.15   538.4 1842.73
   560.8  1850.3   592.6 1862.97     603 1868.24   616.2  1870.7     645 1881.14
#Mann= 5 ,-1,0
       0      .1       0  241.07    .045       0  371.31     .06       0
     430     .12       0     480      .1       0
Bank Sta=241.07,371.31
XS Rating Curve= 0 ,0
Exp/Cntr(USF)=0,0
Exp/Cntr=0.3,0.1

Type RM Length L Ch R = 1 ,88941   ,440.7,471.1,498.9
XS GIS Cut Line= 2
2193321.73920488662845.6366674452193741.24670141663262.601694302
#Sta/Elev= 30
       0  1850.6    43.8 1833.21    84.5 1818.94    97.6  1815.6   107.2 1809.45
   118.5 1809.01   128.7 1807.54   138.8 1803.43   145.6 1802.07   190.9 1800.69
   200.8 1798.83   209.3  1798.2   213.5 1796.76   217.7 1793.53  224.711789.649
     232 1787.07     239 1786.78   315.4 1786.81   326.7 1788.27  348.681789.649
   392.6 1801.96   425.7 1804.75   445.5 1808.58   471.5 1819.48   488.5  1825.1
   533.1 1842.55   550.5 1847.79   569.9 1855.26     590 1861.57   591.5 1861.99
#Mann= 7 ,-1,0
       0      .1       0      40     .06       0     170     .07       0
  224.71    .045       0  348.68     .12       0     440      .1       0
     590     .06       0
Bank Sta=224.71,348.68
XS Rating Curve= 0 ,0
Exp/Cntr(USF)=0,0
Exp/Cntr=0.3,0.1

Type RM Length L Ch R = 1 ,88470   ,484.3,482.3,482.4
XS GIS Cut Line= 2
2193029.35519214663000.7273176792193253.09252362663575.325464445
#Sta/Elev= 30
       0 1860.28    17.7 1855.48    26.2 1851.27    64.3 1838.45   133.6 1817.36
   142.1 1811.05   160.1 1809.89   173.1 1805.87   197.9 1800.82   215.7 1798.85
   240.9 1798.21   265.1 1795.88     270 1794.54  285.141787.257   296.7 1784.87
   305.1 1784.56   395.4  1784.6  402.381787.259   413.4 1796.17   421.2 1799.73
     434 1801.02   451.2 1806.45   462.9 1805.12   481.2 1805.92   544.2 1817.88
   567.1  1823.4   575.7 1826.14   584.3 1830.35   601.9 1831.61   616.6 1839.03
#Mann= 5 ,-1,0
       0      .1       0     160     .08       0     270      .1       0
  285.14    .045       0  402.38      .1       0
Bank Sta=285.14,402.38
XS Rating Curve= 0 ,0
Exp/Cntr(USF)=0,0
Exp/Cntr=0.3,0.1

Type RM Length L Ch R = 1 ,87988   ,174.4,174.7,175.1
XS GIS Cut Line= 2
2192574.25312014663145.6480892082192797.99045163663710.076357271
#Sta/Elev= 30
       0 1864.09    13.4 1856.23    25.8 1854.26    38.1 1850.39    85.6 1847.71
    89.9  1845.7   107.1    1834     120 1828.86   137.2 1822.64   150.1 1810.63
     163  1809.9   171.6 1805.89   184.5 1803.58   195.2 1795.05   201.7 1791.04
     223 1789.08  229.961786.505   240.5 1782.76   253.4 1782.12   339.4 1782.15
   343.7 1782.56  353.511786.504   363.4 1788.41   386.7 1789.26   401.7 1795.11
   410.9 1797.49   537.3 1803.56   549.6 1805.92   584.7  1809.2   607.2 1814.31
#Mann= 6 ,-1,0
       0      .1       0     120     .06       0     220      .1       0
  229.96    .045       0  353.51      .1       0     540     .06       0
Bank Sta=229.96,353.51
XS Rating Curve= 0 ,0
Exp/Cntr(USF)=0,0
Exp/Cntr=0.3,0.1

Type RM Length L Ch R = 1 ,87813   ,44.4,46.7,49.5
XS GIS Cut Line= 2
2192436.32887705663265.783030912 2192622.3853478663746.124899832
#Sta/Elev= 30
       0 1837.57     7.9  1834.6    20.8 1827.95      38 1827.68    45.8 1826.18
    59.4 1819.91    72.3 1809.85    76.6 1807.73    89.4 1808.17   101.4 1804.21
   110.9 1803.11   140.9 1795.84   158.1 1789.91   170.9 1788.49  178.691786.294
   188.1 1782.19   237.3 1782.03   282.5 1782.08   286.8 1783.66  290.861786.291
   295.3 1787.84   312.5 1789.46   325.4 1794.82   351.1 1799.67   419.9 1800.64
   463.2 1802.86   475.6 1805.18   488.4 1815.23   492.7 1815.73   515.1 1814.22
#Mann= 9 ,-1,0
       0     .06       0      60     .08       0      90     .07       0
  178.69    .045       0  290.86     .07       0     300     .06       0
     340      .1       0     410     .06       0     510      .1       0
Bank Sta=178.69,290.86
XS Rating Curve= 0 ,0
Exp/Cntr(USF)=0,0
Exp/Cntr=0.3,0.1

Type RM Length L Ch R = 1 ,87766   ,42.9,42,41.1
XS GIS Cut Line= 6
2192332.97079469663312.0379285262192372.20474633663354.017547284
2192442.67791649663400.4449963682192510.50825428663597.766145381
2192514.02203907663704.3692499192192554.72756148663790.165031957
#Sta/Elev= 30
       0 1825.98       7 1824.62    34.4 1824.45    39.9 1820.93    45.5  1815.8
    48.4 1814.35    50.8 1813.57    62.6 1812.82    71.8 1807.26      77  1806.4
    88.6 1807.27    92.3 1806.83   105.9 1803.18   143.6 1800.82   153.1 1798.84
   171.9 1791.92   189.2 1788.21  195.041786.232   203.4 1782.62   209.7 1781.97
   297.8 1782.15   299.1 1782.28  306.931786.227     316 1788.65     323 1792.61
     333 1796.69   369.9  1799.1     414 1800.08   489.1 1805.54   552.1 1812.23
#Mann= 8 ,-1,0
       0     .07       0      40     .06       0      50      .1       0
  191.85     .07       0  195.04    .045       0  306.93     .06       0
  400.51      .1       0  497.17     .06       0
Bank Sta=195.04,306.93
XS Rating Curve= 0 ,0
Exp/Cntr(USF)=0,0
Exp/Cntr=0.3,0.1

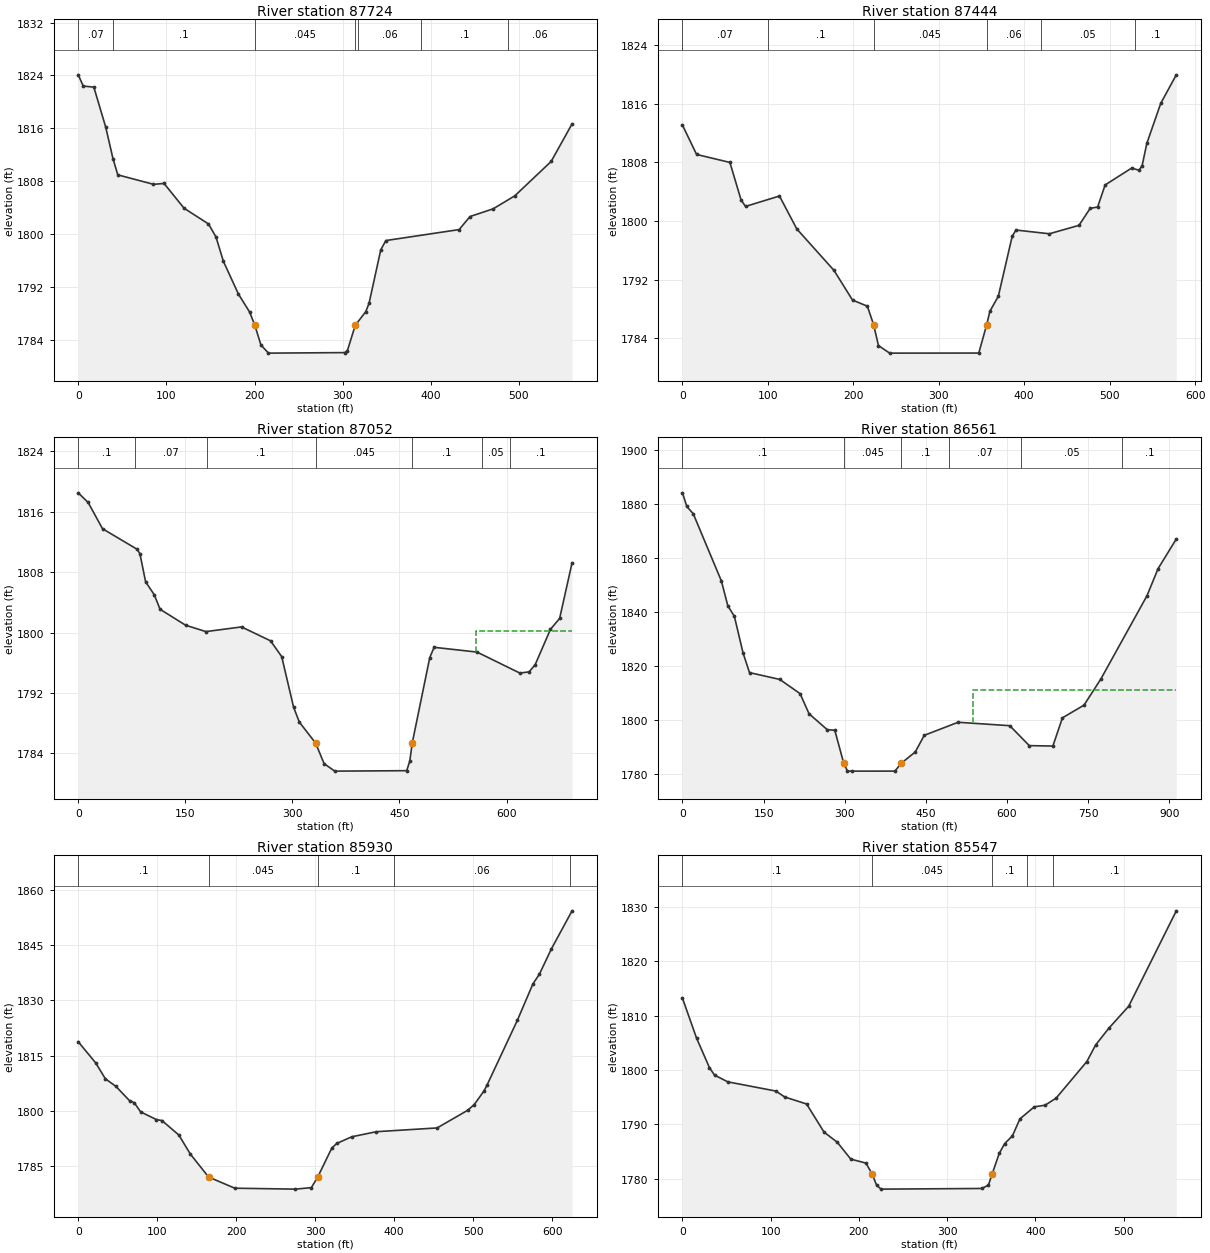
Type RM Length L Ch R = 1 ,87724   ,284,280.2,276.1
XS GIS Cut Line= 6
2192289.18617796663324.1536884012192330.53206035663369.147736882
2192402.27932685663416.5738960922192474.02659335663616.006975846
2192476.45870407663724.2359032742192519.02064183 663806.92766805
#Sta/Elev= 30
       0 1824.09     5.7 1822.39    17.7 1822.23    31.2 1816.17    39.4 1811.42
    44.9 1808.95    85.4 1807.52    97.4 1807.65     120 1803.91   147.8 1801.52
   156.3 1799.55   164.7 1795.87   181.8  1790.9   194.5 1788.18  200.381786.175
   207.3 1783.21   215.8 1781.97   302.3 1782.05   305.4 1782.34   314.31786.173
   326.3 1788.26     330 1789.53   343.3 1797.62   349.1 1799.01   432.2 1800.67
   444.5 1802.64   470.8 1803.81   495.4 1805.78   536.6 1810.98   560.3 1816.66
#Mann= 7 ,-1,0
       0     .07       0      40      .1       0  200.38    .045       0
   314.3      .1       0  317.11     .06       0  389.06      .1       0
  487.31     .06       0
Bank Sta=200.38,314.3
XS Rating Curve= 0 ,0
Exp/Cntr(USF)=0,0
Exp/Cntr=0.3,0.1

Type RM Length L Ch R = 1 ,87444   ,390,392.3,395.3
XS GIS Cut Line= 2
2192066.52516186663358.024194329 2192292.6473299663889.967327342
#Sta/Elev= 30
       0 1813.07    16.5 1809.07    55.5 1807.98    68.6 1802.85    73.8 1801.98
   113.5  1803.4   133.8 1798.91   177.3 1793.26     199 1789.21   216.4 1788.37
  223.671785.863   229.4    1783   242.5 1781.97   346.8 1781.98  356.11 1785.86
   359.8 1787.68   369.7 1789.73   385.9  1797.9   390.3 1798.76   429.4 1798.25
   464.1  1799.4   477.2 1801.72   485.9  1801.9   494.7 1804.91   525.7 1807.21
   534.3 1806.92     538 1807.54   543.5 1810.58   559.8 1816.04     578 1819.93
#Mann= 6 ,-1,0
       0     .07       0     100      .1       0  223.67    .045       0
  356.11     .06       0     420     .05       0     530      .1       0
Bank Sta=223.67,356.11
XS Rating Curve= 0 ,0
Exp/Cntr(USF)=0,0
Exp/Cntr=0.3,0.1

Type RM Length L Ch R = 1 ,87052   ,548.1,490.7,424
XS GIS Cut Line= 3
2191715.05213414663367.4043081692191739.14711926663571.284951484
2191913.37239628664025.382747959
#Sta/Elev= 30
       0  1818.5    13.9 1817.22      34 1813.75    82.3 1811.04    86.4 1810.45
    94.4 1806.71   106.5 1805.01   114.6 1803.09   150.3 1800.98   178.9 1800.13
   228.7 1800.75   269.4 1798.91     285 1796.82   301.6 1790.14   309.7 1788.15
  332.511785.371   344.4 1782.65   359.3 1781.66   460.1 1781.72   464.4 1782.98
  467.841785.374   492.4 1796.69   498.5 1798.05   558.6 1797.42   618.6 1794.64
   631.5  1794.8     640 1795.74   661.5 1800.44   674.3 1801.87   691.7 1809.23
#Mann= 7 ,-1,0
       0      .1       0      80     .07       0     180      .1       0
  332.51    .045       0  467.84      .1       0   565.3     .05       0
   605.3      .1       0
#XS Ineff= 2 , 0
                          556.84         1800.27
Permanent Ineff=
       F       F
Bank Sta=332.51,467.84
XS Rating Curve= 0 ,0
Exp/Cntr(USF)=0,0
Exp/Cntr=0.3,0.1

Type RM Length L Ch R = 1 ,86561   ,686.8,631.6,553.2
XS GIS Cut Line= 5
2191092.28944184663997.5808420522191275.78202082663999.434302446
2191622.37911445664103.2280844972191828.11321816664201.461485367
 2191965.2692873 664227.40993088
#Sta/Elev= 30
       0 1884.17     7.9 1879.16    19.9 1876.42    71.9 1851.55    83.9 1842.28
    95.9 1838.47   111.9 1824.93   123.9 1817.61   179.9 1815.08   217.4 1809.82
     234 1802.36   267.4 1796.52   281.6 1796.24  298.041784.082     305 1781.17
   312.6 1781.13   392.7 1781.14  404.711784.079   430.3 1788.22     447 1794.39
   509.6 1799.22   605.1 1797.95   641.1 1790.57   684.7 1790.42   702.4 1800.86
   742.3 1805.57   773.4 1815.23   858.7 1846.06   879.2  1856.1   912.9 1867.08
#Mann= 6 ,-1,0
       0      .1       0  298.04    .045       0  404.71      .1       0
   493.5     .07       0  625.31     .05       0  813.29      .1       0
#XS Ineff= 2 , 0
                          537.84         1811.12
Permanent Ineff=
       F       F
Bank Sta=298.04,404.71
XS Rating Curve= 0 ,0
Exp/Cntr(USF)=0,0
Exp/Cntr=0.3,0.1

Type RM Length L Ch R = 1 ,85930   ,379.4,382,385.6
XS GIS Cut Line= 3
2191457.42113941  664757.49960352191818.84591619664468.359782071
2191976.39004967664429.437113802
#Sta/Elev= 30
       0 1818.77    22.1 1813.03    34.3 1808.72    47.7 1806.64      65 1802.75
    70.9 1802.21      79 1799.71    98.9 1797.63     106 1797.35   127.4 1793.42
   141.8 1788.29  165.011782.008   198.2 1778.97     275 1778.72   295.1 1779.13
  303.191782.011   320.9 1789.85   327.1 1791.12   346.3 1792.95   377.5 1794.33
   454.3 1795.35   493.1 1800.16   501.3 1801.71   513.7 1805.41   517.8 1807.14
   555.8 1824.56   575.6 1834.51   583.7  1837.1   598.7  1843.9   625.1 1854.35
#Mann= 5 ,-1,0
       0      .1       0  165.01    .045       0  303.19      .1       0
     400     .06       0  622.85      .1       0
Bank Sta=165.01,303.19
XS Rating Curve= 0 ,0
Exp/Cntr(USF)=0,0
Exp/Cntr=0.3,0.1

Type RM Length L Ch R = 1 ,85547   ,491.5,451.5,428.1
XS GIS Cut Line= 2
2191658.84568378665070.587372295 2192109.8543796664739.023901853
#Sta/Elev= 30
       0 1813.18    15.9 1805.86    30.6  1800.4    36.3 1799.04    51.3  1797.8
   105.9  1796.1   115.8 1795.02   140.7 1793.72   160.5 1788.54   175.4  1786.7
   190.8 1783.58     208 1782.85  214.691780.929   220.1 1778.78   225.1 1778.06
   339.2 1778.18   346.8 1778.79   351.21780.929   359.1 1784.64   365.3 1786.45
     374 1787.85   382.5 1790.98   398.8  1793.2   411.1  1793.5   423.6 1794.81
   458.4 1801.53   468.3 1804.57   483.2 1807.64   505.8  1811.7   559.8 1829.26
#Mann= 5 ,-1,0
       0      .1       0  214.69    .045       0   351.2      .1       0
     390    .025       0     420      .1       0
Bank Sta=214.69,351.2
XS Rating Curve= 0 ,0
Exp/Cntr(USF)=0,0
Exp/Cntr=0.3,0.1