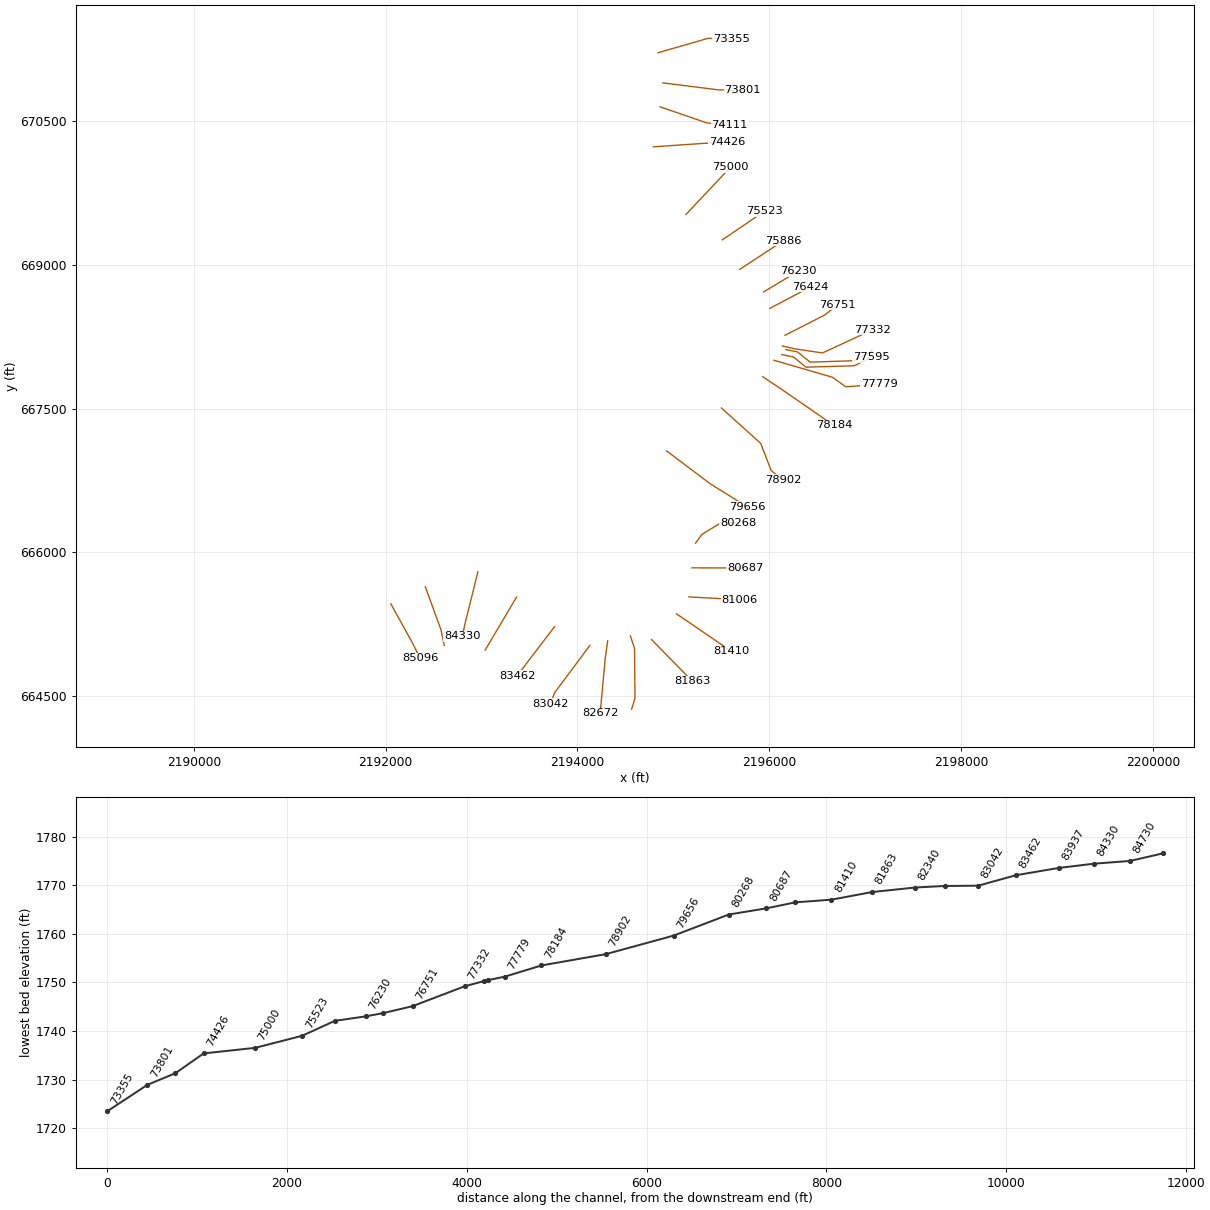
HEC-RAS study BUCKHANR_U.prj: BUCKHANR_U

--- BUCKHANR_U.g01 (geometry) --- (continued)

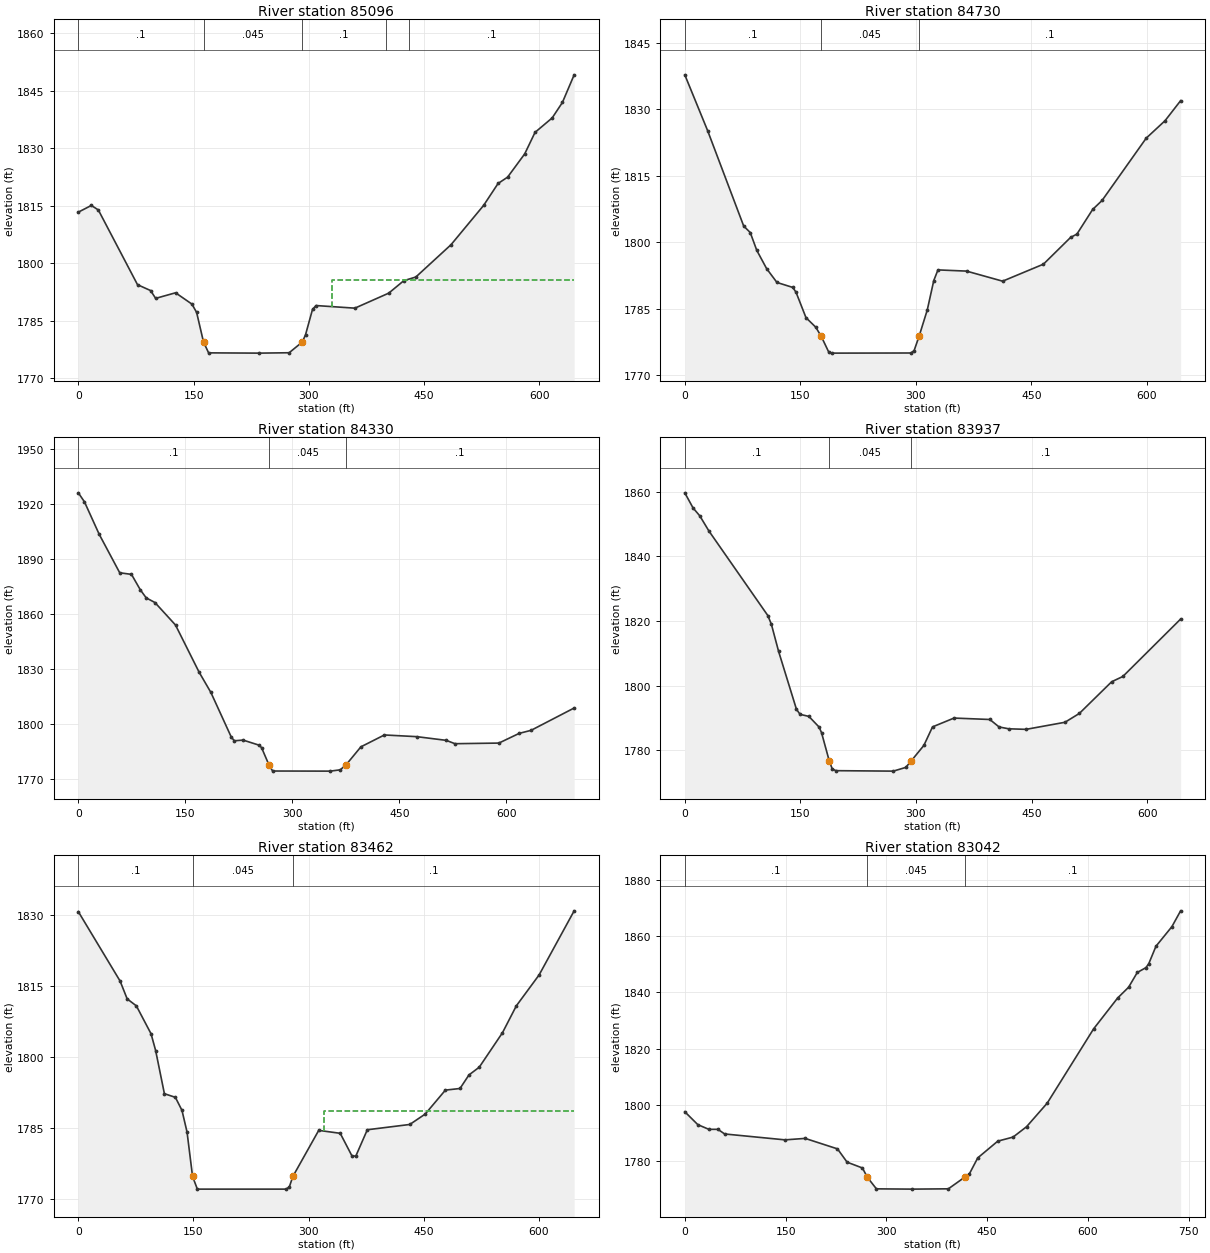
Type RM Length L Ch R = 1 ,85096   ,377.7,365.8,354.8
XS GIS Cut Line= 3
2192054.25056778665463.9328558622192282.84401635 665049.99336792
2192359.04183254664895.538335105
#Sta/Elev= 30
       0 1813.36    16.9 1815.11      26 1813.94      77 1794.44      94 1792.91
   100.6 1790.87   126.5 1792.33   147.7 1789.39   153.9 1787.22  162.851779.495
   169.5 1776.66   235.7 1776.59   274.3 1776.69  291.441779.496   295.6 1781.39
   304.7 1788.01   309.3    1789   359.8 1788.32   403.8 1792.23   423.5 1795.49
   439.1 1796.44   484.9 1804.87   527.3 1815.12   546.1 1820.84   558.5 1822.49
   580.8 1828.57   594.2 1834.17   616.5 1837.94   629.8 1841.97   645.1 1849.18
#Mann= 5 ,-1,0
       0      .1       0  162.85    .045       0  291.44      .1       0
     400     .05       0     430      .1       0
#XS Ineff= 2 , 0
                          330.51         1795.64
Permanent Ineff=
       F       F
Bank Sta=162.85,291.44
XS Rating Curve= 0 ,0
Exp/Cntr(USF)=0,0
Exp/Cntr=0.3,0.1

Type RM Length L Ch R = 1 ,84730   ,439.4,400,360.5
XS GIS Cut Line= 3
2192414.64564435 665641.041293492192577.33827891665194.151398547
2192612.34808635665029.399363544
#Sta/Elev= 30
       0 1837.73    29.7 1825.13    76.5 1803.66      85  1802.2    93.5 1798.18
   106.3 1794.06   119.7 1790.95   140.3 1789.83   144.6  1788.7   157.4 1783.02
   170.1 1780.87   177.21778.816   187.2 1775.18   191.3 1775.03   293.6 1775.06
   297.8 1775.58  304.281778.813   314.9 1784.73   323.4 1791.39   328.8 1793.78
   365.9 1793.51   412.8 1791.24   465.8 1795.07   501.1  1801.1   509.3 1801.85
   529.7 1807.39     542 1809.43   599.3 1823.46   623.8  1827.4     644 1831.91
#Mann= 3 ,-1,0
       0      .1       0   177.2    .045       0  304.28      .1       0
Bank Sta=177.2,304.28
XS Rating Curve= 0 ,0
Exp/Cntr(USF)=0,0
Exp/Cntr=0.3,0.1

Type RM Length L Ch R = 1 ,84330   ,412.3,393.5,375.6
XS GIS Cut Line= 4
2192962.44616073665797.5557267422192925.37695286665645.160094365
2192832.70393317 665274.468015612192799.75352617665122.072383233
#Sta/Elev= 30
       0 1926.08     8.6 1921.16    29.2 1903.52      58 1882.53    74.5 1881.65
    86.8 1873.29    95.1 1868.86   107.4 1866.31   136.2 1854.06   169.2 1828.42
   185.7 1817.39   214.5  1792.9   218.7 1791.01     231 1791.37   253.5 1788.59
   256.8 1787.26  266.961778.035   272.3 1774.53   353.1 1774.47   367.1 1775.18
  375.531778.041     396  1787.7   428.9 1794.17   474.3 1793.25   515.5 1791.24
   527.9 1789.41   589.4 1789.75     618 1795.06   634.4 1796.67   694.9 1808.86
#Mann= 3 ,-1,0
       0      .1       0  266.96    .045       0  375.53      .1       0
Bank Sta=266.96,375.53
XS Rating Curve= 0 ,0
Exp/Cntr(USF)=0,0
Exp/Cntr=0.3,0.1

Type RM Length L Ch R = 1 ,83937   ,483,474.8,467.5
XS GIS Cut Line= 2
2193366.08864649665533.9524707382193038.64397692664979.973753044
#Sta/Elev= 30
       0 1859.66    10.7 1854.99    19.5 1852.53    31.2 1847.89   107.8 1821.69
   112.4 1818.98   121.7 1810.65   144.9 1792.73   149.6 1791.15     161 1790.52
   174.3 1787.22   177.5 1785.46  187.561776.676   191.4 1774.26   196.1 1773.73
   270.6 1773.59   286.8 1774.74  293.591776.677   310.3 1781.55   321.5 1787.27
   349.4    1790   395.9 1789.56   407.9 1787.25   420.4 1786.68   442.9 1786.51
   493.4  1788.7     512 1791.42     554 1801.23   568.5 1802.86   643.5 1820.62
#Mann= 3 ,-1,0
       0      .1       0  187.56    .045       0  293.59      .1       0
Bank Sta=187.56,293.59
XS Rating Curve= 0 ,0
Exp/Cntr(USF)=0,0
Exp/Cntr=0.3,0.1

Type RM Length L Ch R = 1 ,83462   ,419,419.5,423
XS GIS Cut Line= 2
2193762.02770579665224.4724536012193370.48737569664710.893579058
#Sta/Elev= 30
       0 1830.79    54.4 1816.11    63.6 1812.34    75.6 1810.86    94.7 1804.96
   100.7 1801.41   112.1 1792.28   126.4 1791.51     135 1788.75   141.6 1784.16
  148.781774.783     155 1772.09   270.7 1772.09   274.8 1772.56  279.461774.783
   313.1 1784.52   341.1  1783.9   356.2 1779.18   361.3 1779.04   376.4 1784.65
   431.7 1785.77   451.8 1787.97   478.1 1793.04   497.1 1793.38   508.8 1796.25
   522.2 1797.89   552.4 1805.17   570.5 1810.87   600.2 1817.42   645.8 1830.97
#Mann= 3 ,-1,0
       0      .1       0  148.78    .045       0  279.46      .1       0
#XS Ineff= 2 , 0
                          319.65         1788.54
Permanent Ineff=
       F       F
Bank Sta=148.78,279.46
XS Rating Curve= 0 ,0
Exp/Cntr(USF)=0,0
Exp/Cntr=0.3,0.1

Type RM Length L Ch R = 1 ,83042   ,331,370.2,416.4
XS GIS Cut Line= 3
 2194130.6858088665028.7022885532193764.57017547664538.005641092
 2193718.8057213664421.052035998
#Sta/Elev= 30
       0 1797.49    19.4 1792.89    35.8 1791.23    49.3 1791.23    59.3 1789.58
   149.1 1787.48   179.1    1788   227.2 1784.27   241.5 1779.54   264.4 1777.46
  271.34 1774.26   285.1 1770.04   338.6 1769.94   392.2 1770.05  416.94 1774.26
   423.6 1775.44   435.9 1781.06   465.7 1787.02   488.5 1788.47   508.5 1792.15
   539.3 1800.56   608.3 1826.99     644 1837.96   660.4 1841.82   673.3 1847.07
   686.1 1848.78   690.4  1850.2   701.1 1856.41   724.8 1863.38   737.8 1869.02
#Mann= 3 ,-1,0
       0      .1       0  271.34    .045       0  416.94      .1       0
Bank Sta=271.34,416.94
XS Rating Curve= 0 ,0
Exp/Cntr(USF)=0,0
Exp/Cntr=0.3,0.1

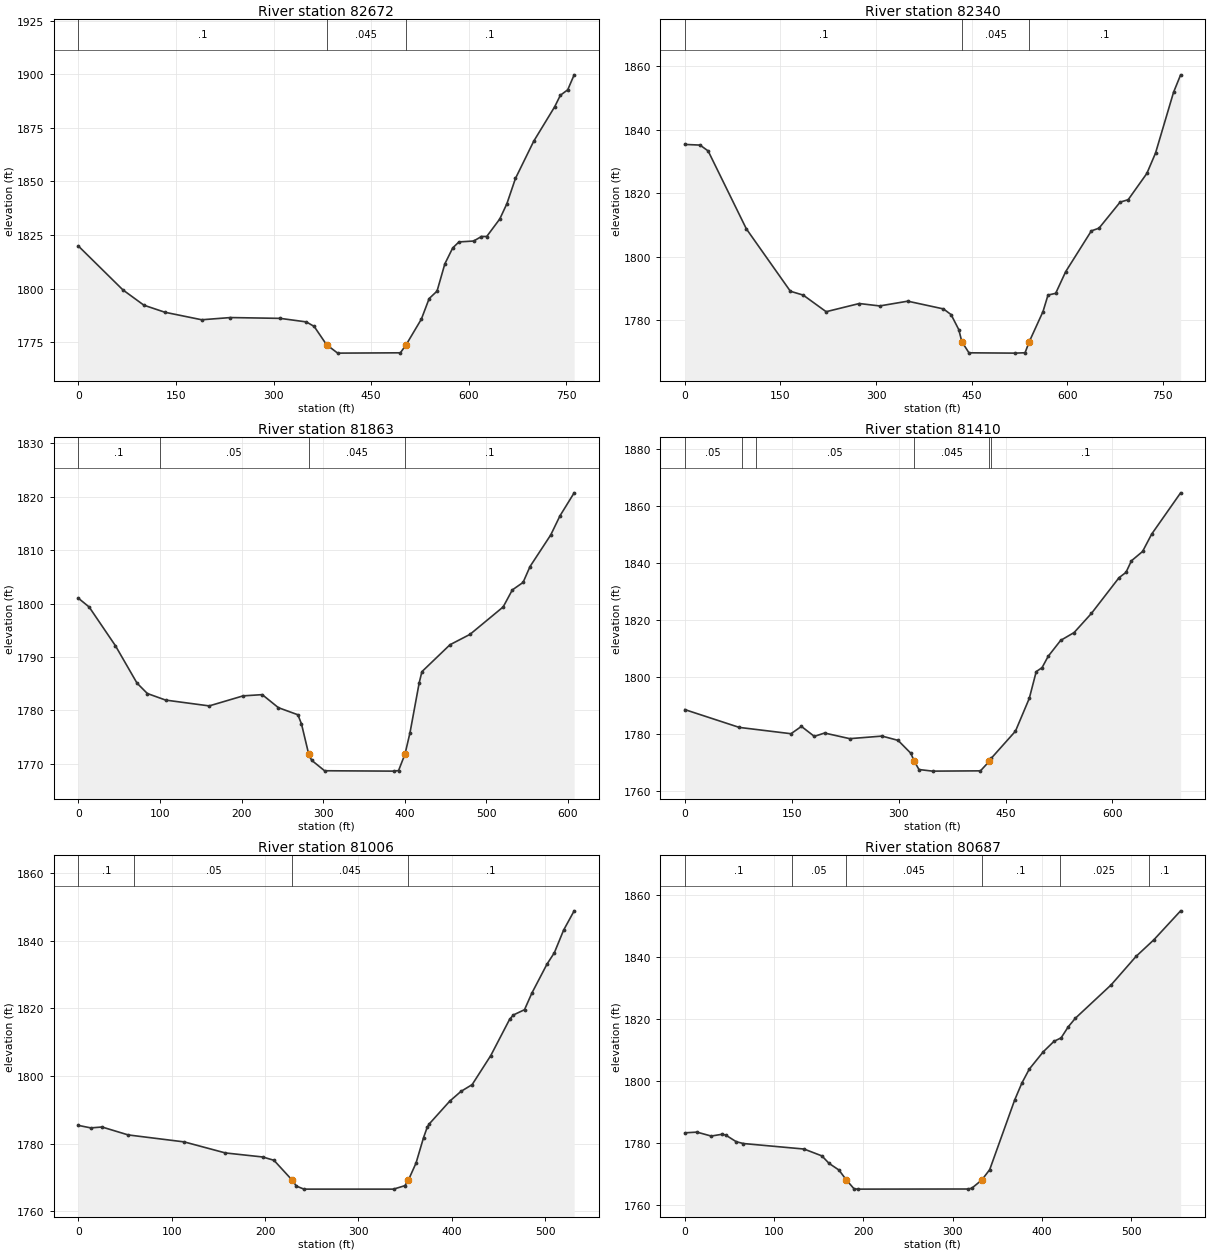
Type RM Length L Ch R = 1 ,82672   ,325.6,332.7,340.5
XS GIS Cut Line= 3
2194316.28609515665077.0092123962194290.86139839664896.493865403
 2194237.4695352 664319.35324896
#Sta/Elev= 30
       0 1819.85    68.5 1799.37   100.8 1792.23   133.1 1788.94   189.6 1785.44
   233.8 1786.47   310.2 1786.09   350.3 1784.44   362.4 1782.34  381.381773.828
   398.5 1769.88   494.9 1770.03  503.781773.827   527.1 1785.73   539.1 1795.34
   551.2  1798.8   563.2 1811.52   575.3 1818.95   584.9 1821.75   607.4 1822.16
   619.5 1824.27   627.5 1824.26   647.6 1832.45   658.5 1839.54   671.7 1851.36
   699.8 1868.74     732  1884.8   740.7 1890.15     752 1892.69   761.9 1899.68
#Mann= 3 ,-1,0
       0      .1       0  381.38    .045       0  503.78      .1       0
Bank Sta=381.38,503.78
XS Rating Curve= 0 ,0
Exp/Cntr(USF)=0,0
Exp/Cntr=0.3,0.1

Type RM Length L Ch R = 1 ,82340   ,423.1,476.7,523
XS GIS Cut Line= 4
2194552.73577501665127.8586059152194595.95775951664998.192652441
2194601.04269886664476.9863688692194565.44812339664362.575233451
#Sta/Elev= 30
       0 1835.36    23.9 1835.16    36.6 1833.31    96.5 1808.76   165.6 1789.07
   185.7 1787.86   221.7 1782.62   273.7  1785.2   305.7 1784.44   349.7 1785.94
   405.7  1783.5   417.7  1781.7   429.7 1776.99  434.571773.151   445.7 1769.66
   518.2 1769.56   533.7 1769.68  540.251773.152   561.8 1782.65   569.7 1787.88
   581.7 1788.41   597.4 1795.24   637.7 1808.11   649.7 1808.96   682.8 1817.17
   695.4 1817.93   724.7 1826.21   738.3 1832.62   766.6  1851.8   777.7 1857.31
#Mann= 3 ,-1,0
       0      .1       0  434.57    .045       0  540.25      .1       0
Bank Sta=434.57,540.25
XS Rating Curve= 0 ,0
Exp/Cntr(USF)=0,0
Exp/Cntr=0.3,0.1

Type RM Length L Ch R = 1 ,81863   ,435.9,452.7,460.3
XS GIS Cut Line= 2
2194773.93063682665089.7215607762195198.52307271664654.959246187
#Sta/Elev= 30
       0 1801.01    13.3 1799.35    45.5  1792.1    71.9 1785.11    84.6 1783.16
     107 1781.93   160.4 1780.84     202 1782.72   225.4 1782.95   245.2 1780.51
   269.1 1779.18   273.5 1777.47  282.291771.849   285.9 1770.67   301.8  1768.7
   386.5 1768.63   392.5 1768.74  400.411771.847   406.5 1775.82   417.8 1785.18
   421.1 1787.25   455.5 1792.29     480 1794.23   520.7 1799.37   531.9 1802.55
   545.1 1803.96   553.6 1806.93     579 1812.85   590.3 1816.42   607.7 1820.73
#Mann= 4 ,-1,0
       0      .1       0     100     .05       0  282.29    .045       0
  400.41      .1       0
Bank Sta=282.29,400.41
XS Rating Curve= 0 ,0
Exp/Cntr(USF)=0,0
Exp/Cntr=0.3,0.1

Type RM Length L Ch R = 1 ,81410   ,359.6,404.4,432.6
XS GIS Cut Line= 2
2195033.11758009665358.6169590052195607.52739577 664966.26052753
#Sta/Elev= 30
       0 1788.61    76.4 1782.37     149 1780.16   163.6 1782.72   181.7 1779.23
   196.1  1780.4   231.4 1778.43   276.7 1779.33   299.2 1777.83     317 1773.34
  321.941770.562   328.5 1767.62   347.6 1767.06   414.8 1767.16  427.391770.562
     430 1771.58   463.9 1781.06   483.3 1792.55     493  1801.9   501.2  1803.3
   509.8 1807.27   527.3 1812.84   546.2 1815.59   570.5  1822.3   609.2  1834.8
   618.9 1836.64   626.6 1840.71   642.2 1843.97     655 1850.06   695.6 1864.51
#Mann= 6 ,-1,0
       0     .05       0      80      .1       0     100     .05       0
  321.94    .045       0  427.39     .05       0     430      .1       0
Bank Sta=321.94,427.39
XS Rating Curve= 0 ,0
Exp/Cntr(USF)=0,0
Exp/Cntr=0.3,0.1

Type RM Length L Ch R = 1 ,81006   ,315.3,318.9,322.2
XS GIS Cut Line= 2
2195162.86046054665535.0615107182195693.32082524665506.703566693
#Sta/Elev= 30
       0 1785.36    13.3 1784.62    25.4 1784.88    53.4 1782.54   113.5 1780.47
   157.5 1777.21   197.6 1776.01   209.6 1775.03  229.221769.119   233.6  1767.4
   241.7  1766.5   337.7  1766.5   349.8 1767.52  353.521769.118   361.8 1774.22
   369.8  1781.7   373.8 1784.82     376 1785.81   397.9 1792.53   409.9 1795.41
   421.9 1797.42   441.9 1806.04     462 1816.72     466 1818.02     478 1819.59
   485.9 1824.51     502 1833.03     510 1836.46   519.9 1843.14   531.2 1848.85
#Mann= 4 ,-1,0
       0      .1       0      60     .05       0  229.22    .045       0
  353.52      .1       0
Bank Sta=229.22,353.52
XS Rating Curve= 0 ,0
Exp/Cntr(USF)=0,0
Exp/Cntr=0.3,0.1

Type RM Length L Ch R = 1 ,80687   ,373.6,418.3,457.8
XS GIS Cut Line= 2
2195194.55463327665838.6583232182195750.03671329665836.990208864
#Sta/Elev= 30
       0 1783.43    13.6 1783.66    29.6 1782.39    41.6 1782.96    45.6 1782.75
    57.6 1780.57    65.6 1779.98   133.6  1778.2   153.6 1775.99   161.6 1773.58
   172.7 1771.43  181.051768.216   189.6 1765.38   193.6 1765.27   317.6 1765.31
   321.6 1765.58  332.741768.215   341.6 1771.56   369.6 1794.04   377.6 1799.46
   385.9 1803.97   401.6 1809.57   413.6 1812.94   421.6 1814.06   429.6 1817.63
   437.6  1820.4   477.7 1831.17   505.6 1840.35   525.5 1845.69   555.5 1855.04
#Mann= 6 ,-1,0
       0      .1       0     120     .05       0  181.05    .045       0
  332.74      .1       0     420    .025       0     520      .1       0
Bank Sta=181.05,332.74
XS Rating Curve= 0 ,0
Exp/Cntr(USF)=0,0
Exp/Cntr=0.3,0.1

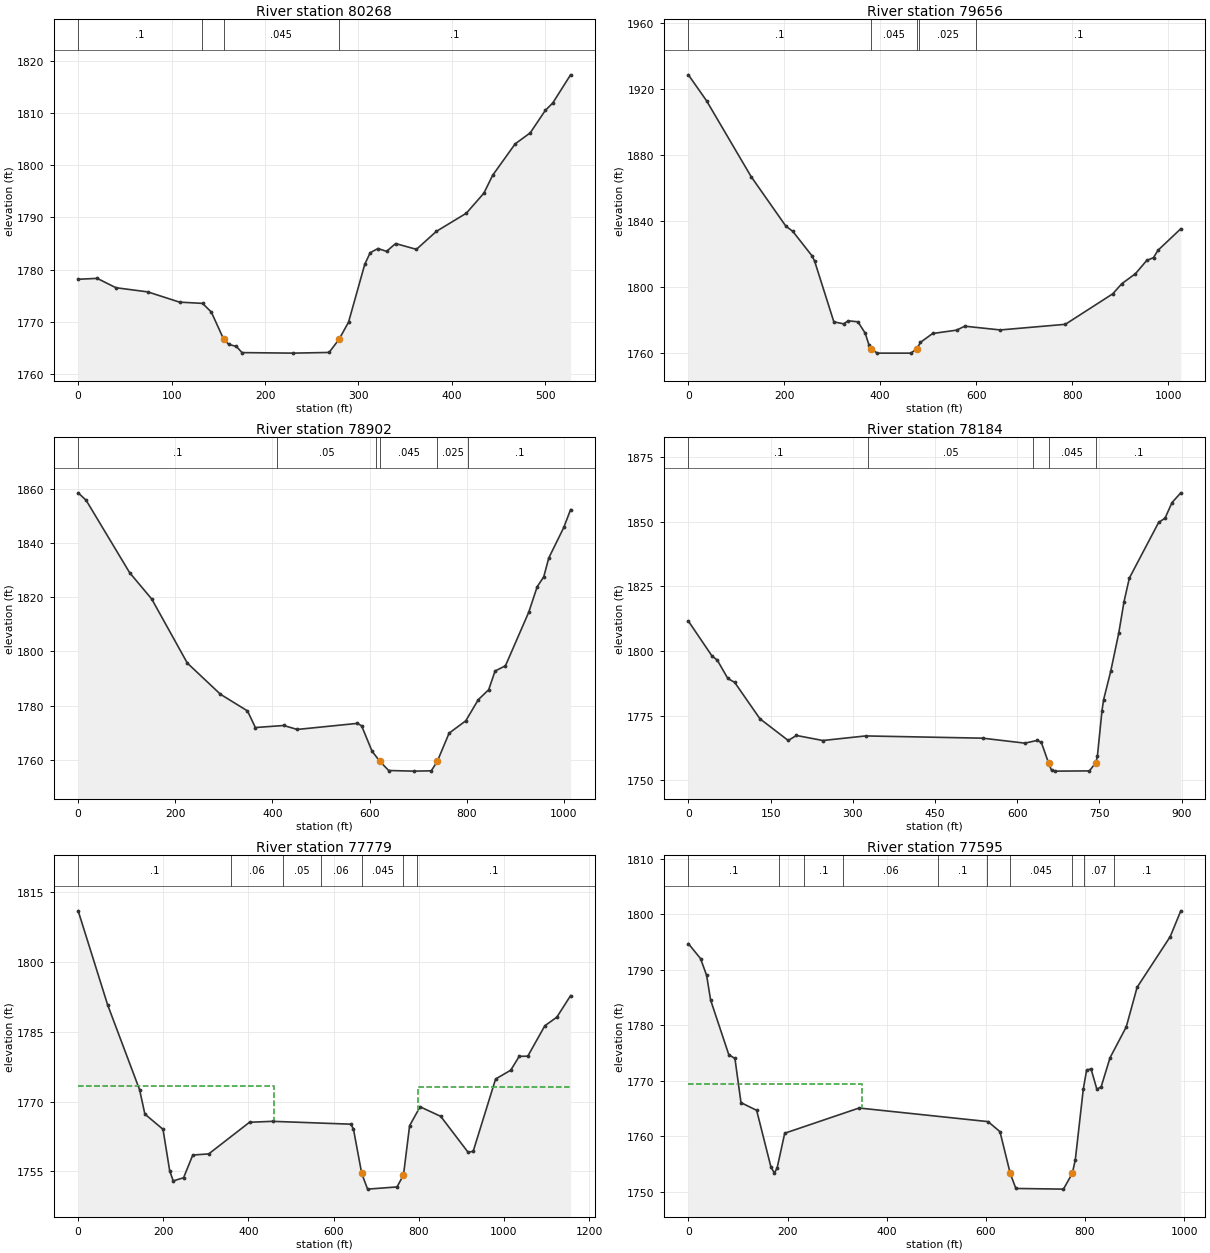
Type RM Length L Ch R = 1 ,80268   ,680,612.5,532.1
XS GIS Cut Line= 4
 2195232.3446313666096.515852001 2195298.2454453666187.129471252
 2195512.4230908666318.9310992542195675.11572537666302.455895754
#Sta/Elev= 30
       0 1778.15    20.4 1778.32    40.4 1776.53    74.5 1775.73   108.5 1773.77
   133.1 1773.53   142.5 1771.88  155.781766.656   161.3 1765.67   169.4 1765.28
   175.4  1764.1   230.4    1764   268.6 1764.13  279.291766.656   289.4 1769.92
   306.8 1781.02   312.6 1783.24     321 1784.04   330.1 1783.49   339.8 1784.99
   362.1 1783.88   383.4 1787.32   415.5  1790.8   434.3 1794.64   443.7 1798.07
   467.8 1804.09   483.9 1806.19     500 1810.48     508 1811.91   527.1 1817.31
#Mann= 4 ,-1,0
       0      .1       0  132.04    .025       0  155.78    .045       0
  279.29      .1       0
Bank Sta=155.78,279.29
XS Rating Curve= 0 ,0
Exp/Cntr(USF)=0,0
Exp/Cntr=0.3,0.1

Type RM Length L Ch R = 1 ,79656   ,778.9,754.1,719.6
XS GIS Cut Line= 3
 2194929.9808509667059.8894249372195385.25649379  666716.3540549
2195772.46758112666475.076610847
#Sta/Elev= 30
       0 1928.47    37.8 1912.77   130.7 1866.78   203.2  1836.7   217.7 1833.52
   258.3 1818.47   263.3 1815.34   303.3 1778.63   323.5 1777.44   333.5 1779.26
   353.5 1778.65   368.6 1771.79   376.4 1764.71  381.321762.264   393.6 1759.66
   463.8 1759.66  476.371762.266   483.8 1766.18   509.2 1771.57     559 1773.59
   576.3    1776   650.3 1773.72   785.9 1777.14   884.8 1795.65   903.7  1801.8
     932 1807.82   955.5 1815.85   969.7 1817.59   979.1 1822.06  1026.6  1835.1
#Mann= 5 ,-1,0
       0      .1       0  381.32    .045       0  476.37      .1       0
     480    .025       0  600.34      .1       0
Bank Sta=381.32,476.37
XS Rating Curve= 0 ,0
Exp/Cntr(USF)=0,0
Exp/Cntr=0.3,0.1

Type RM Length L Ch R = 1 ,78902   ,676.6,718.1,749.3
XS GIS Cut Line= 4
2195501.39735288667508.1831551722195912.07612499667137.527123528
2196021.29901674666853.9394413782196143.07136461666755.520694469
#Sta/Elev= 30
       0 1858.55    16.4 1855.81   106.1 1829.05   151.4 1819.37   224.7 1795.72
     293  1784.2   348.6 1778.06   364.8 1771.93   423.2 1772.68     451 1771.22
     575 1773.47   583.6 1772.54     605 1763.19  621.131759.428   639.3 1756.07
   690.8 1755.84   726.9 1755.95  739.271759.427   763.6 1769.85     798 1774.42
   823.6 1782.18   845.1 1785.89   858.3  1792.8   879.6 1794.71   927.7 1814.55
     945 1823.91   958.5 1827.56   968.8 1834.51   999.7 1845.76  1013.7 1852.37
#Mann= 6 ,-1,0
       0      .1       0     410     .05       0  613.21      .1       0
  621.13    .045       0  739.27    .025       0  803.21      .1       0
Bank Sta=621.13,739.27
XS Rating Curve= 0 ,0
Exp/Cntr(USF)=0,0
Exp/Cntr=0.3,0.1

Type RM Length L Ch R = 1 ,78184   ,406.5,404.9,403.6
XS GIS Cut Line= 3
2195932.32140891 667834.382835722196130.29021079667702.101890452
2196673.37865518667326.311236078
#Sta/Elev= 30
       0  1811.6    43.1 1798.09    52.7  1796.5      72 1789.37    84.4 1787.89
   130.5 1773.79   182.2 1765.37   197.1 1767.31   245.3 1765.36   323.5 1767.13
   537.1 1766.26   613.9 1764.34   636.9  1765.4   644.1 1764.59  657.131756.722
   662.7 1753.75   668.2  1753.5   731.7 1753.59  743.341756.723   746.3 1759.23
   754.7 1776.91   757.6 1781.11   770.6 1792.14   785.2 1806.85   794.9 1819.11
   804.6 1828.25   858.1 1849.82   869.7 1851.44   882.5 1857.52   898.5 1861.27
#Mann= 5 ,-1,0
       0      .1       0   328.1     .05       0   628.1      .1       0
  657.13    .045       0  743.34      .1       0
Bank Sta=657.13,743.34
XS Rating Curve= 0 ,0
Exp/Cntr(USF)=0,0
Exp/Cntr=0.3,0.1

Type RM Length L Ch R = 1 ,77779   ,138.5,184.1,227.1
XS GIS Cut Line= 4
2196049.72798069668005.7309985012196661.43862521667827.726204238
2196797.64518495667729.4658366052197148.42962994667754.189315719
#Sta/Elev= 30
       0 1810.94    69.2 1790.77   144.4 1772.51   156.7 1767.32   199.3 1764.05
     215 1755.15   223.3 1752.97   247.7 1753.66   269.2 1758.53   306.7 1758.77
   402.5 1765.56   456.6 1765.76   640.5 1765.15   646.6 1764.14  666.051754.581
   679.9 1751.21     749 1751.68   764.21754.237   778.6 1764.83   803.2 1768.88
   851.7 1766.83   915.8 1759.14   927.9 1759.32   980.6 1774.85  1016.1 1776.73
  1036.1 1779.71  1056.2 1779.75  1096.3 1786.28  1124.4 1788.11  1156.7 1792.74
#Mann= 7 ,-1,0
       0      .1       0     360     .06       0     480     .05       0
     570     .06       0  666.05    .045       0   764.2     .05       0
  797.08      .1       0
#XS Ineff= 2 , 0
           459.9  1773.4  798.07         1773.19
Permanent Ineff=
       F       F
Bank Sta=666.05,764.2
XS Rating Curve= 0 ,0
Exp/Cntr(USF)=0,0
Exp/Cntr=0.3,0.1

Type RM Length L Ch R = 1 ,77595   ,54.6,54.6,52.7
XS GIS Cut Line= 5
2196132.14259157668064.759390394 2196253.0372971668040.424138426
2196384.47887615667933.7091930612196889.50118228 667948.43283543
 2197061.8683073668040.311326557
#Sta/Elev= 30
       0 1794.69    24.5    1792    36.8 1788.97    44.9 1784.51    81.6 1774.68
    93.9 1774.02   106.1 1766.07   137.7 1764.68   166.5 1754.48   173.4 1753.39
   178.9 1754.27   194.3 1760.56   344.3  1765.1   604.5 1762.65   628.5 1760.84
  649.171753.335   660.5 1750.62   756.5  1750.5  774.391753.337   780.5 1755.82
   796.5 1768.47   803.3 1771.96   812.2 1772.12     824 1768.46   832.6 1768.93
   850.5 1774.15   883.2  1779.7   905.1 1786.83   971.9 1795.95   993.2 1800.59
#Mann= 10 ,-1,0
       0      .1       0  183.32     .06       0  233.32      .1       0
  312.63     .06       0  502.63      .1       0  602.63     .07       0
  649.17    .045       0  774.39     .06       0  797.86     .07       0
  857.86      .1       0
#XS Ineff= 2 , 0
          351.05 1769.43
Permanent Ineff=
       F       F
Bank Sta=649.17,774.39
XS Rating Curve= 0 ,0
Exp/Cntr(USF)=0,0
Exp/Cntr=0.3,0.1

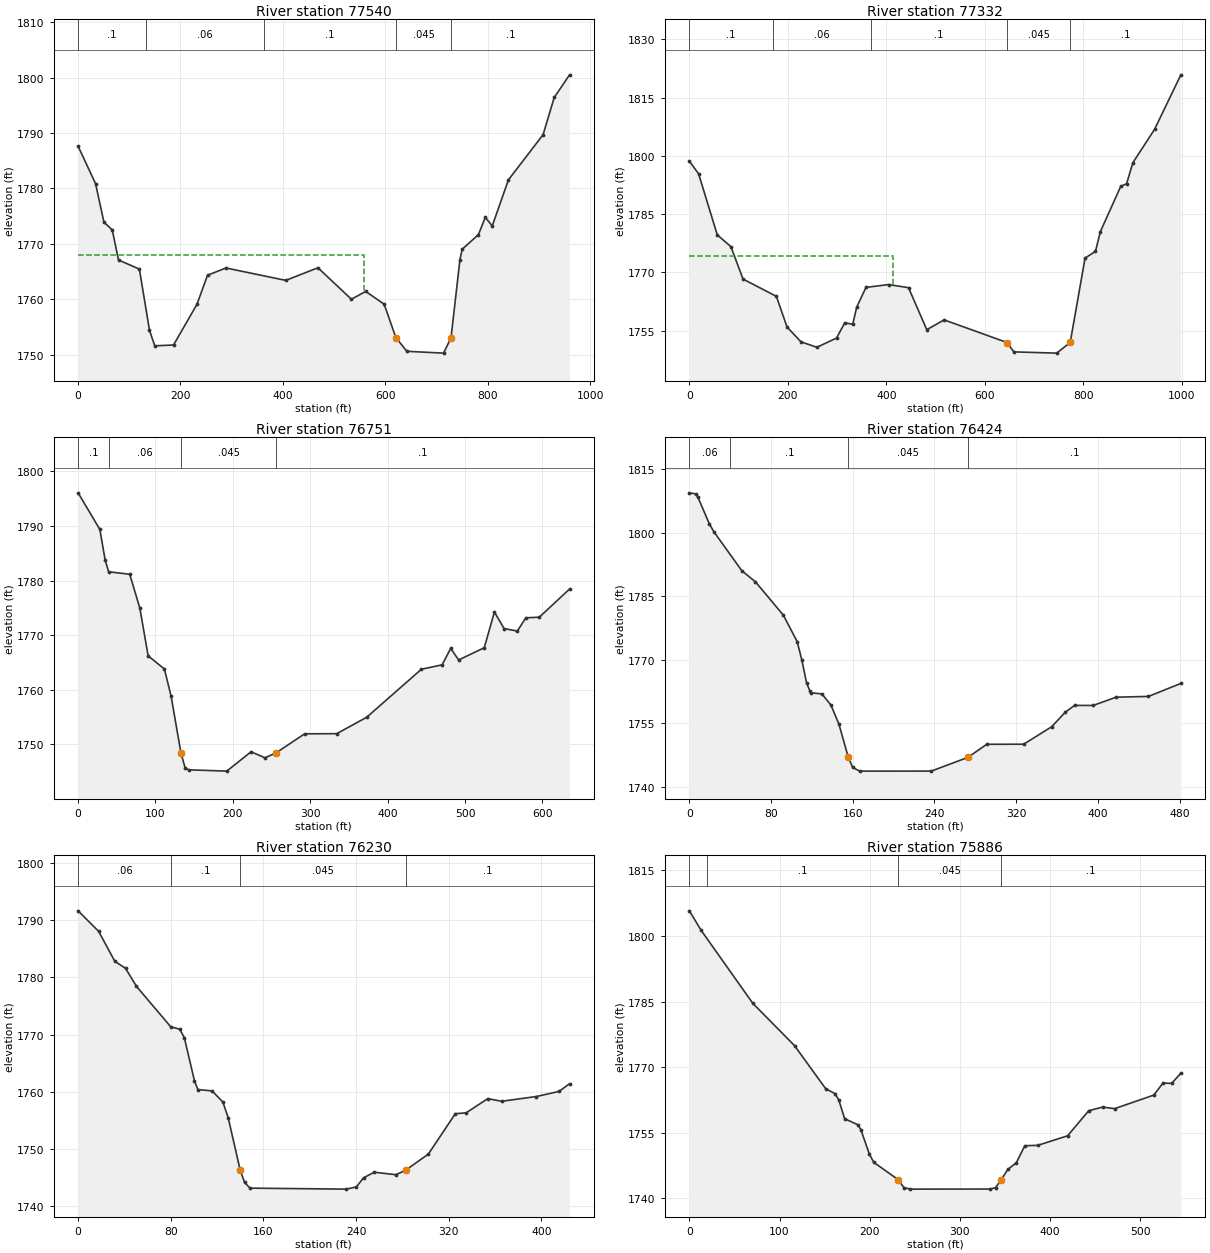
Type RM Length L Ch R = 1 ,77540   ,176.7,208.6,235.2
XS GIS Cut Line= 5
2196174.78586498668117.2704713332196295.68057051668092.935219365
2196427.12214956   667986.2202742196881.38978656668000.943916369
2197069.94241911668099.676122356
#Sta/Elev= 30
       0 1787.63    34.1 1780.87    50.4 1773.92    66.7 1772.52    78.9 1767.08
   119.7 1765.44   139.4  1754.4   149.7 1751.58   186.4 1751.73   232.2 1759.08
   252.8 1764.33   288.8 1765.64   405.7  1763.4   468.5 1765.68   533.8    1760
   561.8  1761.4   597.8 1759.11  620.721753.068   642.2 1750.59   713.9 1750.26
  728.511753.043   745.9 1767.17   750.3 1769.03     782 1771.66   795.4 1774.79
     809 1773.23   840.6 1781.56   908.3 1789.72   930.1 1796.44     960 1800.53
#Mann= 5 ,-1,0
       0      .1       0  133.32     .06       0  362.63      .1       0
  620.72    .045       0  728.51      .1       0
#XS Ineff= 2 , 0
          558.33    1768
Permanent Ineff=
       F       F
Bank Sta=620.72,728.51
XS Rating Curve= 0 ,0
Exp/Cntr(USF)=0,0
Exp/Cntr=0.3,0.1

Type RM Length L Ch R = 1 ,77332   ,538.4,580.6,538.8
XS GIS Cut Line= 4
2196137.93476834668154.5867885812196273.55674038668124.168861911
2196555.59887585668082.1244461792197076.58778653668322.977591743
#Sta/Elev= 30
       0 1798.64    18.7 1795.37    56.6 1779.66    84.3 1776.63   108.9 1768.28
   176.6 1763.84   198.3 1755.94   226.6 1752.13   258.9 1750.72   298.8  1753.1
   315.5 1757.02   331.7 1756.64   339.8 1761.06   358.6 1766.14   404.5 1766.87
     445 1766.07   482.1 1755.25   517.3 1757.78   645.1 1751.95   658.9 1749.54
     746 1749.22   773.41751.966   803.6 1773.69   824.7 1775.41   834.6 1780.48
   875.9 1792.12     888 1792.85   900.7 1798.24   944.8 1806.84   998.1 1820.86
#Mann= 5 ,-1,0
       0      .1       0  168.99     .06       0  368.99      .1       0
   645.1    .045       0   773.4      .1       0
#XS Ineff= 2 , 0
          413.85 1774.27
Permanent Ineff=
       F       F
Bank Sta=645.1,773.4
XS Rating Curve= 0 ,0
Exp/Cntr(USF)=0,0
Exp/Cntr=0.3,0.1

Type RM Length L Ch R = 1 ,76751   ,325.4,327.2,327.2
XS GIS Cut Line= 3
2196165.10148278 668266.507721592196579.79471128668478.191433163
2196711.74255671668584.617128973
#Sta/Elev= 30
       0 1796.08    28.1 1789.37    34.9 1783.81    39.4 1781.62    66.7 1781.17
    79.8 1774.95    90.5 1766.23   111.5 1763.82   120.2 1758.82   132.9 1748.45
   138.2 1745.77   142.7 1745.36   192.1 1745.12   223.5 1748.66   241.5 1747.56
  255.671748.448   292.7 1751.95   334.3 1751.98     373 1754.99   443.6 1763.77
   470.4 1764.58   481.5 1767.59   491.8 1765.47   524.9 1767.72     538 1774.26
   550.5 1771.22   567.6 1770.77   578.7  1773.2     596  1773.3   635.1 1778.47
#Mann= 4 ,-1,0
       0      .1       0      40     .06       0   132.9    .045       0
  255.67      .1       0
Bank Sta=132.9,255.67
XS Rating Curve= 0 ,0
Exp/Cntr(USF)=0,0
Exp/Cntr=0.3,0.1

Type RM Length L Ch R = 1 ,76424   ,189.6,193.6,201
XS GIS Cut Line= 2
 2196006.8169262668547.1447133752196432.18608657668772.340151218
#Sta/Elev= 30
       0 1809.44     6.1 1809.19     8.4 1808.37    19.6 1802.06    24.2 1800.16
    51.3 1791.05    64.7 1788.41    92.1 1780.51   105.6 1774.25   110.2 1769.85
   114.7 1764.57   117.9 1762.68   119.2  1762.2   129.8 1761.92   138.6  1759.3
   146.4 1754.82  155.611746.948   159.9 1744.56   166.8 1743.69   236.9  1743.7
  272.861746.949   291.2 1750.03   327.4 1750.05   354.7 1754.16   368.1  1757.6
   377.2 1759.22   395.3  1759.2   417.9 1761.16   449.6 1761.34   481.3 1764.41
#Mann= 4 ,-1,0
       0     .06       0      40      .1       0  155.61    .045       0
  272.86      .1       0
Bank Sta=155.61,272.86
XS Rating Curve= 0 ,0
Exp/Cntr(USF)=0,0
Exp/Cntr=0.3,0.1

Type RM Length L Ch R = 1 ,76230   ,341.6,344.6,348.2
XS GIS Cut Line= 2
2195941.01384096668718.5376109292196304.66277022668937.060591356
#Sta/Elev= 30
       0 1791.61    17.7 1788.03    31.7  1782.8      41 1781.56    50.4 1778.42
      80 1771.36    87.7 1770.95    91.7 1769.47   100.4 1761.98   103.3 1760.41
   115.7 1760.17     125 1758.22   129.6 1755.47  139.961746.313   143.7  1744.2
   148.4 1743.19   231.6 1743.02   240.3 1743.41   246.4 1744.99   255.7 1745.97
   274.4 1745.54  282.711746.312   302.4 1749.14   325.7 1756.19     335 1756.34
   353.7 1758.82   365.7 1758.36   395.7 1759.19   415.2 1760.08   424.3 1761.42
#Mann= 4 ,-1,0
       0     .06       0      80      .1       0  139.96    .045       0
  282.71      .1       0
Bank Sta=139.96,282.71
XS Rating Curve= 0 ,0
Exp/Cntr(USF)=0,0
Exp/Cntr=0.3,0.1

Type RM Length L Ch R = 1 ,75886   ,361.2,362.4,363.2
XS GIS Cut Line= 2
2195693.33559861668954.4771616432196148.69191758669254.234336439
#Sta/Elev= 30
       0 1805.77      13 1801.31    70.4 1784.59   116.6 1774.93   151.3 1765.04
   161.4 1763.96   165.7  1762.5   172.2 1758.21   186.8 1756.82   190.2  1755.7
   199.7 1750.07   204.5 1748.23  231.38 1744.29   237.9 1742.45     245 1742.09
   333.8 1742.11   339.6 1742.43  346.041744.291   353.4 1746.63   362.6  1748.1
   372.1 1752.02   386.5 1752.11   419.6  1754.3     443 1760.03   458.3 1760.86
   471.8 1760.51   515.2 1763.61   525.4 1766.37     535 1766.28   545.2 1768.62
#Mann= 4 ,-1,0
       0     .06       0      20      .1       0  231.38    .045       0
  346.04      .1       0
Bank Sta=231.38,346.04
XS Rating Curve= 0 ,0
Exp/Cntr(USF)=0,0
Exp/Cntr=0.3,0.1

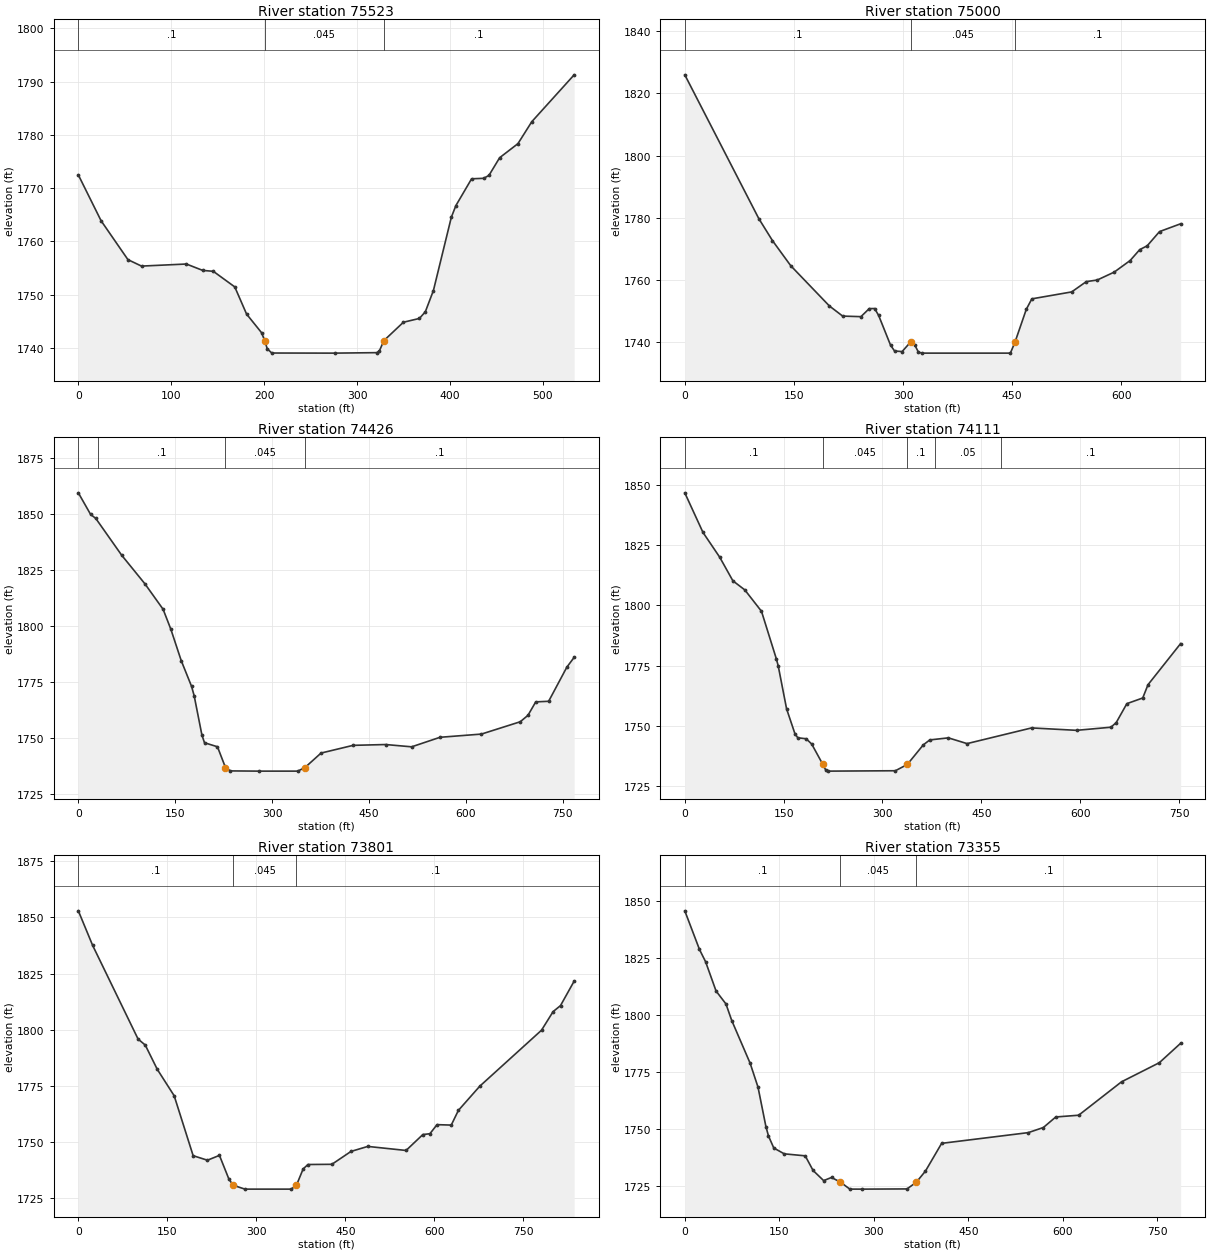
Type RM Length L Ch R = 1 ,75523   ,504.3,523.6,538.5
XS GIS Cut Line= 2
 2195511.9502288669263.4455208422195953.57721152669563.202695638
#Sta/Elev= 30
       0 1772.48    24.5 1763.87    53.4 1756.57      68 1755.36   116.3 1755.75
   133.9 1754.55   145.3 1754.38   168.4 1751.45   181.1 1746.35   197.2 1742.86
  200.661741.363   203.3 1739.85   208.2 1739.04   275.8 1739.02   321.1 1739.11
   323.9 1739.38  328.871741.364   349.9 1744.82   367.1 1745.53   373.5 1746.78
   382.2 1750.77   401.5 1764.54   406.4 1766.72   423.3 1771.75   436.3 1771.84
     442 1772.39   453.5 1775.71   473.2 1778.35   488.1 1782.47   533.7 1791.27
#Mann= 3 ,-1,0
       0      .1       0  200.66    .045       0  328.87      .1       0
Bank Sta=200.66,328.87
XS Rating Curve= 0 ,0
Exp/Cntr(USF)=0,0
Exp/Cntr=0.3,0.1

Type RM Length L Ch R = 1 ,75000   ,636.1,573.4,526.4
XS GIS Cut Line= 2
 2195132.0318356669527.0589410892195598.70857594 670023.76484879
#Sta/Elev= 30
       0 1825.95   101.7 1779.76   120.5 1772.68   145.6 1764.62   198.8 1751.67
     217 1748.43   242.1 1748.25   253.5 1750.83   260.9 1750.86   266.4 1748.66
   282.8 1739.09   288.3 1737.22   298.7 1737.03   310.3 1740.09   315.8 1739.27
   321.2 1736.81   326.7 1736.53   447.5 1736.53  453.781740.011   469.4 1750.62
     477 1753.97   531.8  1756.2   551.8  1759.5   566.9 1760.02   590.2 1762.56
   612.1 1766.28   625.3 1769.79   635.5    1771   652.5 1775.58   681.5 1778.09
#Mann= 3 ,-1,0
       0      .1       0   310.3    .045       0  453.78      .1       0
Bank Sta=310.3,453.78
XS Rating Curve= 0 ,0
Exp/Cntr(USF)=0,0
Exp/Cntr=0.3,0.1

Type RM Length L Ch R = 1 ,74426   ,341.9,314.7,283.5
XS GIS Cut Line= 3
2194793.20941634670234.239878396  2195292.670004670268.685436166
2195559.62307672 670281.60252033
#Sta/Elev= 30
       0  1859.4      19 1849.78      27    1848    67.1 1831.61   103.1 1818.86
   131.3  1807.5   143.3  1798.6   159.3 1784.66   175.4 1773.13   179.4 1768.97
   191.4 1751.45   195.4 1748.03   215.5 1746.23  227.911736.957   235.5 1735.48
   279.6 1735.38   339.8 1735.38  350.911736.959   375.9 1743.43   425.6 1746.87
   476.1 1747.23   516.2 1746.21   560.2 1750.46   624.3 1751.89   684.4 1757.38
   696.4 1760.26   708.4 1766.24   728.4 1766.51   756.6 1781.72   767.9 1786.08
#Mann= 4 ,-1,0
       0     .06       0      30      .1       0  227.91    .045       0
  350.91      .1       0
Bank Sta=227.91,350.91
XS Rating Curve= 0 ,0
Exp/Cntr(USF)=0,0
Exp/Cntr=0.3,0.1

Type RM Length L Ch R = 1 ,74111   ,298.3,310.6,325.3
XS GIS Cut Line= 3
2194862.10053188670651.8922663612195348.64403538670483.970172231
2195585.45724505670462.441698624
#Sta/Elev= 30
       0 1846.58    27.6 1830.17      53 1819.91      73 1810.12    91.1 1806.36
   116.4  1797.5     139 1777.75   141.8 1774.86   154.5 1757.07   167.2 1746.74
   171.5  1745.1   184.2  1744.7   192.6 1742.51  209.541734.046   213.8  1731.8
     218 1731.29   319.6 1731.45  337.681734.046   361.9 1742.15   371.8 1744.22
     400 1745.07   428.4 1742.69   526.3 1749.19   594.6 1748.19   646.8 1749.48
   654.8 1751.42   670.9 1759.24     695 1761.59     703 1767.09   752.5 1784.13
#Mann= 5 ,-1,0
       0      .1       0  209.54    .045       0  337.68      .1       0
     380     .05       0     480      .1       0
Bank Sta=209.54,337.68
XS Rating Curve= 0 ,0
Exp/Cntr(USF)=0,0
Exp/Cntr=0.3,0.1

Type RM Length L Ch R = 1 ,73801   ,421,445.8,473.8
XS GIS Cut Line= 3
2194892.24039492670901.622560196 2195473.5091823670828.425749934
2195723.23947613670824.120055213
#Sta/Elev= 30
       0 1852.93    24.1 1837.53   100.7 1795.78   112.8 1793.11     133 1782.31
   161.5 1770.53   193.5 1743.81   217.6 1741.79   237.8 1743.95   253.9 1733.29
  261.011730.634   280.8 1728.91   358.7 1728.91  367.561730.633   378.9 1737.92
     387 1739.88   427.3 1739.97   459.5 1745.71   487.8 1747.94   552.3 1746.14
   580.6 1753.23   592.5  1753.6   604.5 1757.64   628.5 1757.45   640.5    1764
   676.5 1774.77   780.6 1799.73   800.1 1808.01   812.6  1810.7   835.6 1821.61
#Mann= 3 ,-1,0
       0      .1       0  261.01    .045       0  367.56      .1       0
Bank Sta=261.01,367.56
XS Rating Curve= 0 ,0
Exp/Cntr(USF)=0,0
Exp/Cntr=0.3,0.1

Type RM Length L Ch R = 1 ,73355   ,440.5,418.8,379.7
XS GIS Cut Line= 3
2194840.57205827 671215.938274852195361.56111955671366.637590096
2195605.88289963671360.231838721
#Sta/Elev= 30
       0 1845.78    23.3 1828.79      33  1823.4    49.6 1810.54    65.3 1804.86
    74.5 1797.57   103.7 1778.78   116.2 1768.27   128.7 1750.98   132.8 1746.83
   141.2 1741.55   157.8 1738.98   191.1  1738.1   203.6 1731.66   220.3 1727.22
   232.8 1728.59  247.051726.528   261.9 1723.48   281.7 1723.47   352.7 1723.56
  367.441726.528   381.8 1731.37   407.6 1743.59     545  1748.3     569 1750.55
   588.7 1755.18     625 1755.95     693 1770.63     753 1779.03   786.8 1787.56
#Mann= 3 ,-1,0
       0      .1       0  247.05    .045       0  367.44      .1       0
Bank Sta=247.05,367.44
XS Rating Curve= 0 ,0
Exp/Cntr(USF)=0,0
Exp/Cntr=0.3,0.1