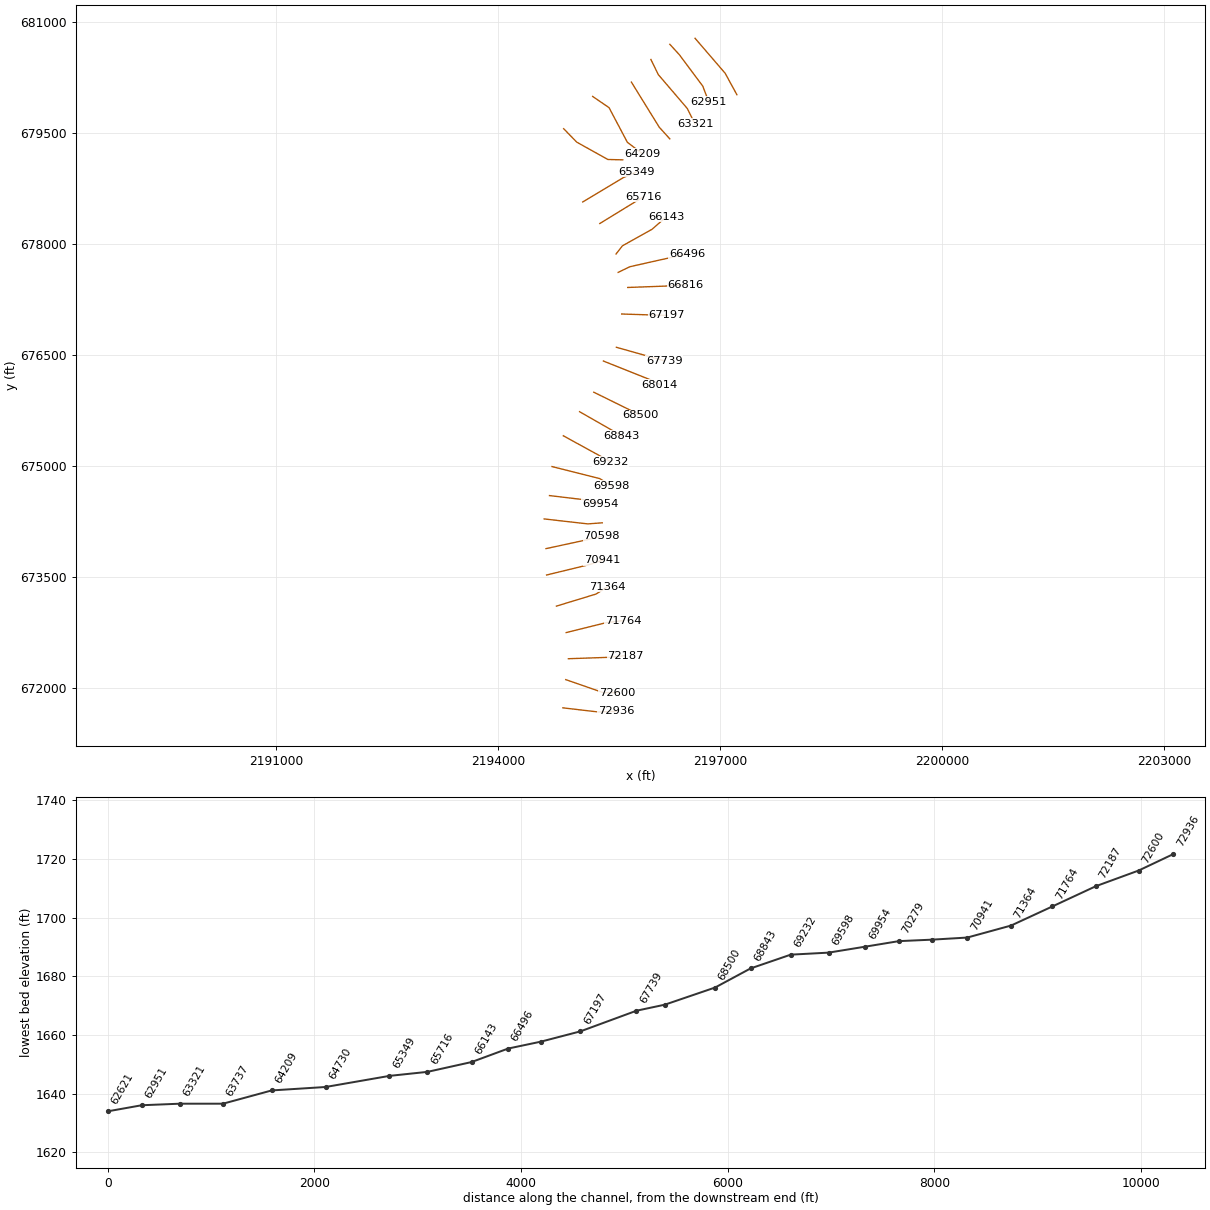
HEC-RAS study BUCKHANR_U.prj: BUCKHANR_U

--- BUCKHANR_U.g01 (geometry) --- (continued)

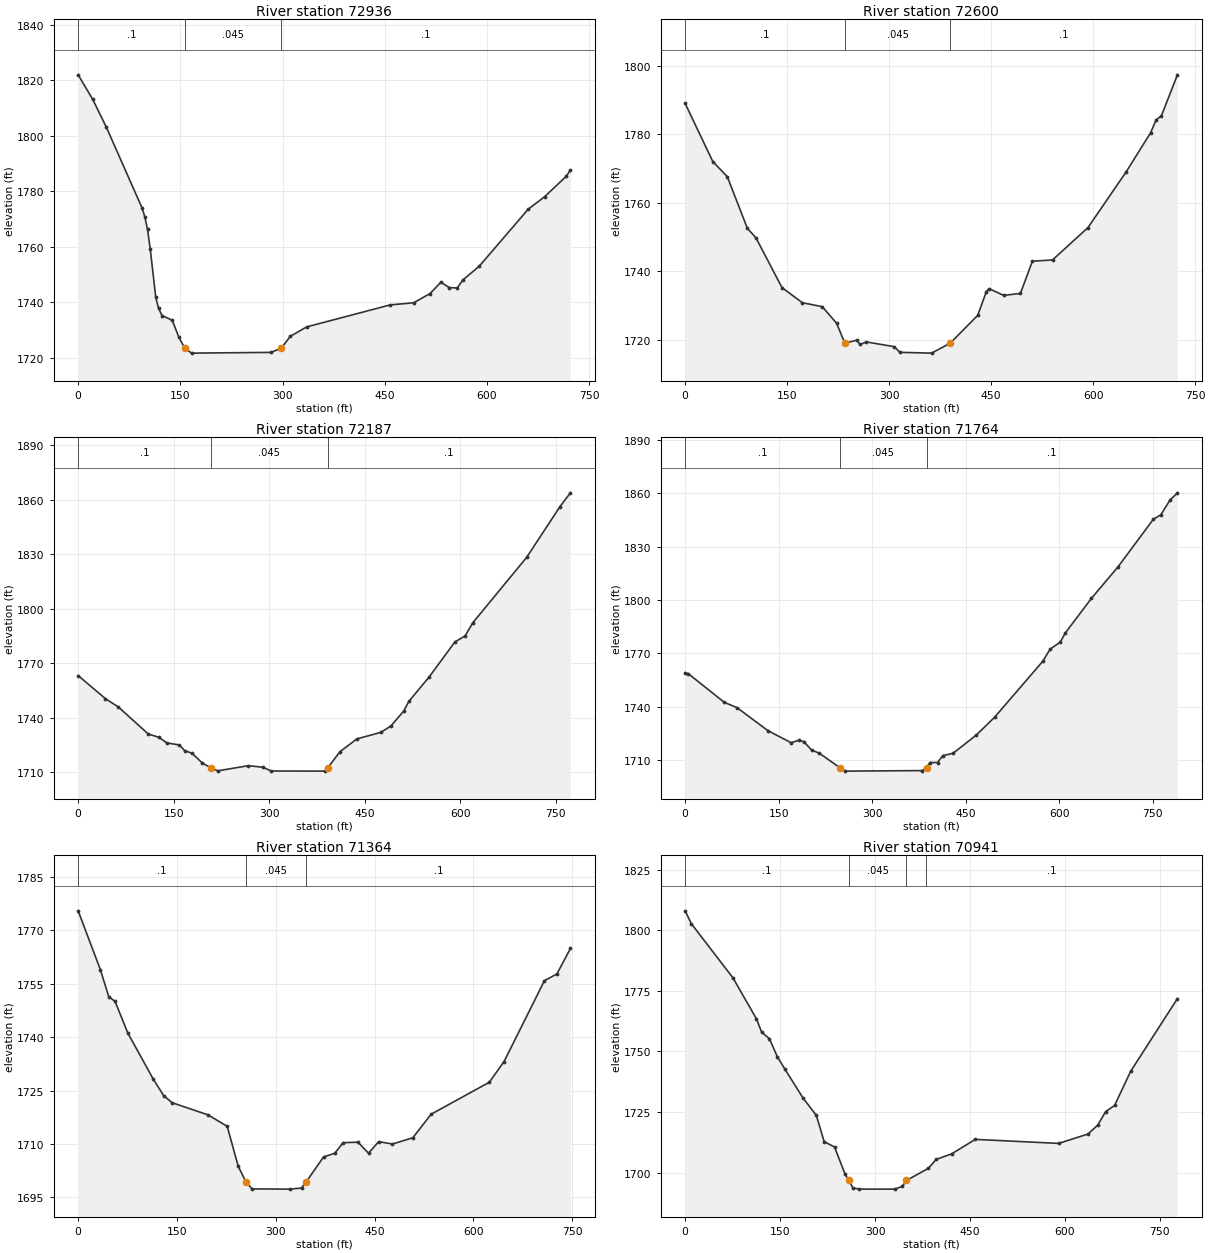
Type RM Length L Ch R = 1 ,72936   ,342.5,336.4,307.4
XS GIS Cut Line= 3
2194875.01761604671732.621641406 2195352.9497301671676.647610029
 2195594.0686345671685.258999471
#Sta/Elev= 30
       0 1822.02    21.3  1813.2    41.4 1803.13    93.8 1774.01    97.8 1770.85
   101.8 1766.26   105.9 1759.03   113.9 1741.75     118 1737.82   123.1 1735.21
   138.1 1733.52   147.9 1727.34  156.451723.463   166.4 1721.66   283.1 1721.93
  298.291723.464   311.3  1727.7   335.4 1731.12   458.1 1739.06   492.4 1739.81
   516.4 1743.13   532.5 1747.25   544.5  1745.3   556.5 1745.16   564.5 1748.02
   588.5 1752.95   660.5 1773.55   684.6 1778.06   716.6 1785.47   722.5 1787.69
#Mann= 3 ,-1,0
       0      .1       0  156.45    .045       0  298.29      .1       0
Bank Sta=156.45,298.29
XS Rating Curve= 0 ,0
Exp/Cntr(USF)=0,0
Exp/Cntr=0.3,0.1

Type RM Length L Ch R = 1 ,72600   ,369.5,412.8,437.6
XS GIS Cut Line= 3
2194913.68275464672114.110620612 2195426.3618251671936.242371676
2195607.71768676  671939.7299844
#Sta/Elev= 30
       0 1788.96    40.7 1771.97    61.9  1767.6    91.5 1752.49   104.3 1749.66
   142.4 1735.18   172.4 1730.76   201.6 1729.61   222.8 1724.75  234.881718.938
   252.4 1719.82   257.3 1718.56   266.7 1719.31   307.5 1717.92   315.9 1716.27
   362.5 1716.04  389.791718.937   430.3 1727.07     443    1734   447.2 1734.86
   468.4 1732.91   493.1 1733.46   510.7 1742.88   540.3 1743.25   592.5 1752.71
   648.5 1768.93   684.5 1780.36   692.5 1784.08   700.5 1785.36     724 1797.31
#Mann= 3 ,-1,0
       0      .1       0  234.88    .045       0  389.79      .1       0
Bank Sta=234.88,389.79
XS Rating Curve= 0 ,0
Exp/Cntr(USF)=0,0
Exp/Cntr=0.3,0.1

Type RM Length L Ch R = 1 ,72187   ,404.7,423.4,438.5
XS GIS Cut Line= 3
2194949.27466958672396.5499897572195511.16783071672415.925616002
2195720.42459417672439.176367497
#Sta/Elev= 30
       0  1763.3    42.9 1750.57    62.9 1746.07   110.1 1731.14   126.7 1729.35
   139.1 1726.24     159 1725.13     167 1722.06     179  1720.5     195 1715.15
  208.591712.497     219 1710.86   267.1 1713.72   289.7 1712.87   303.1 1710.79
   387.1 1710.72  391.721712.497   411.1 1721.42   437.6 1728.45   475.2 1732.05
   491.2 1735.61   511.2 1743.83   519.2 1749.11   551.2 1762.62   591.4 1781.78
   607.5 1785.13   619.6 1792.37   704.1 1828.33   756.2 1856.15   772.8 1863.85
#Mann= 3 ,-1,0
       0      .1       0  208.59    .045       0  391.72      .1       0
Bank Sta=208.59,391.72
XS Rating Curve= 0 ,0
Exp/Cntr(USF)=0,0
Exp/Cntr=0.3,0.1

Type RM Length L Ch R = 1 ,71764   ,393.4,399.1,406.7
XS GIS Cut Line= 3
2194919.34242881672749.7098286742195450.23458795672881.464087146
 2195690.4923534672912.465089139
#Sta/Elev= 30
       0 1758.96       5 1758.61    62.7 1742.47    83.3 1739.45   132.7 1726.54
   169.8 1719.78   182.2 1721.12   190.4 1720.36   202.8 1715.59   215.2 1713.84
  247.751705.799   256.4 1703.78     380 1704.09  387.37  1705.8   392.4 1708.62
   404.7 1708.61     413 1712.47   429.5 1713.81   466.6    1724     496 1734.04
   573.2 1765.49   585.3 1772.44   601.4 1776.32   609.5  1781.5   651.4 1800.96
   694.1 1818.71   750.6 1845.41   762.6 1847.92   777.1 1856.07   789.2 1860.29
#Mann= 3 ,-1,0
       0      .1       0  247.75    .045       0  387.37      .1       0
Bank Sta=247.75,387.37
XS Rating Curve= 0 ,0
Exp/Cntr(USF)=0,0
Exp/Cntr=0.3,0.1

Type RM Length L Ch R = 1 ,71364   ,427,423.8,420.7
XS GIS Cut Line= 3
2194787.82081089 673107.631872312195322.58809527673270.387132775
2195481.46823049673371.140389253
#Sta/Elev= 30
       0  1775.5    33.8 1758.93    46.4 1751.38      56 1750.04    75.6 1741.06
   113.7 1728.29   129.7 1723.58   142.6 1721.57   196.9 1718.17   226.2 1714.93
   242.9 1703.71  254.411699.407   263.8 1697.35   321.3 1697.28     339 1697.58
  346.381699.406   372.5 1706.33   389.4 1707.36   402.2 1710.34   424.7 1710.47
   440.7 1707.38   456.1 1710.63     477 1709.95     508 1711.73   535.6 1718.32
     624 1727.32   646.4 1733.14   707.7 1755.87   726.6 1757.76   747.1 1764.92
#Mann= 3 ,-1,0
       0      .1       0  254.41    .045       0  346.38      .1       0
Bank Sta=254.41,346.38
XS Rating Curve= 0 ,0
Exp/Cntr(USF)=0,0
Exp/Cntr=0.3,0.1

Type RM Length L Ch R = 1 ,70941   ,344.1,342.7,342.9
XS GIS Cut Line= 3
2194654.76515065673528.0865625122195228.28368752673667.591071482
2195406.53944899673725.717950219
#Sta/Elev= 30
       0 1808.01     9.7 1802.73    75.6 1780.32   112.6 1763.47   120.8 1757.98
   133.2 1755.22   145.5 1747.89   157.9 1742.55   186.7 1730.61   207.3  1723.6
   219.6 1712.79   236.1 1710.53   252.6 1699.41  258.681696.753   264.9  1693.7
   275.4 1693.19   330.8 1693.19   343.1 1694.31  349.591696.752   384.3 1701.78
   396.6 1705.45   421.3 1707.77   458.4 1713.72   590.1 1712.05   636.4 1715.93
   651.7 1719.55   664.4 1725.19   678.5 1727.72   703.7 1741.74   777.7 1771.79
#Mann= 4 ,-1,0
       0      .1       0  258.68    .045       0  349.59    .025       0
     380      .1       0
Bank Sta=258.68,349.59
XS Rating Curve= 0 ,0
Exp/Cntr(USF)=0,0
Exp/Cntr=0.3,0.1

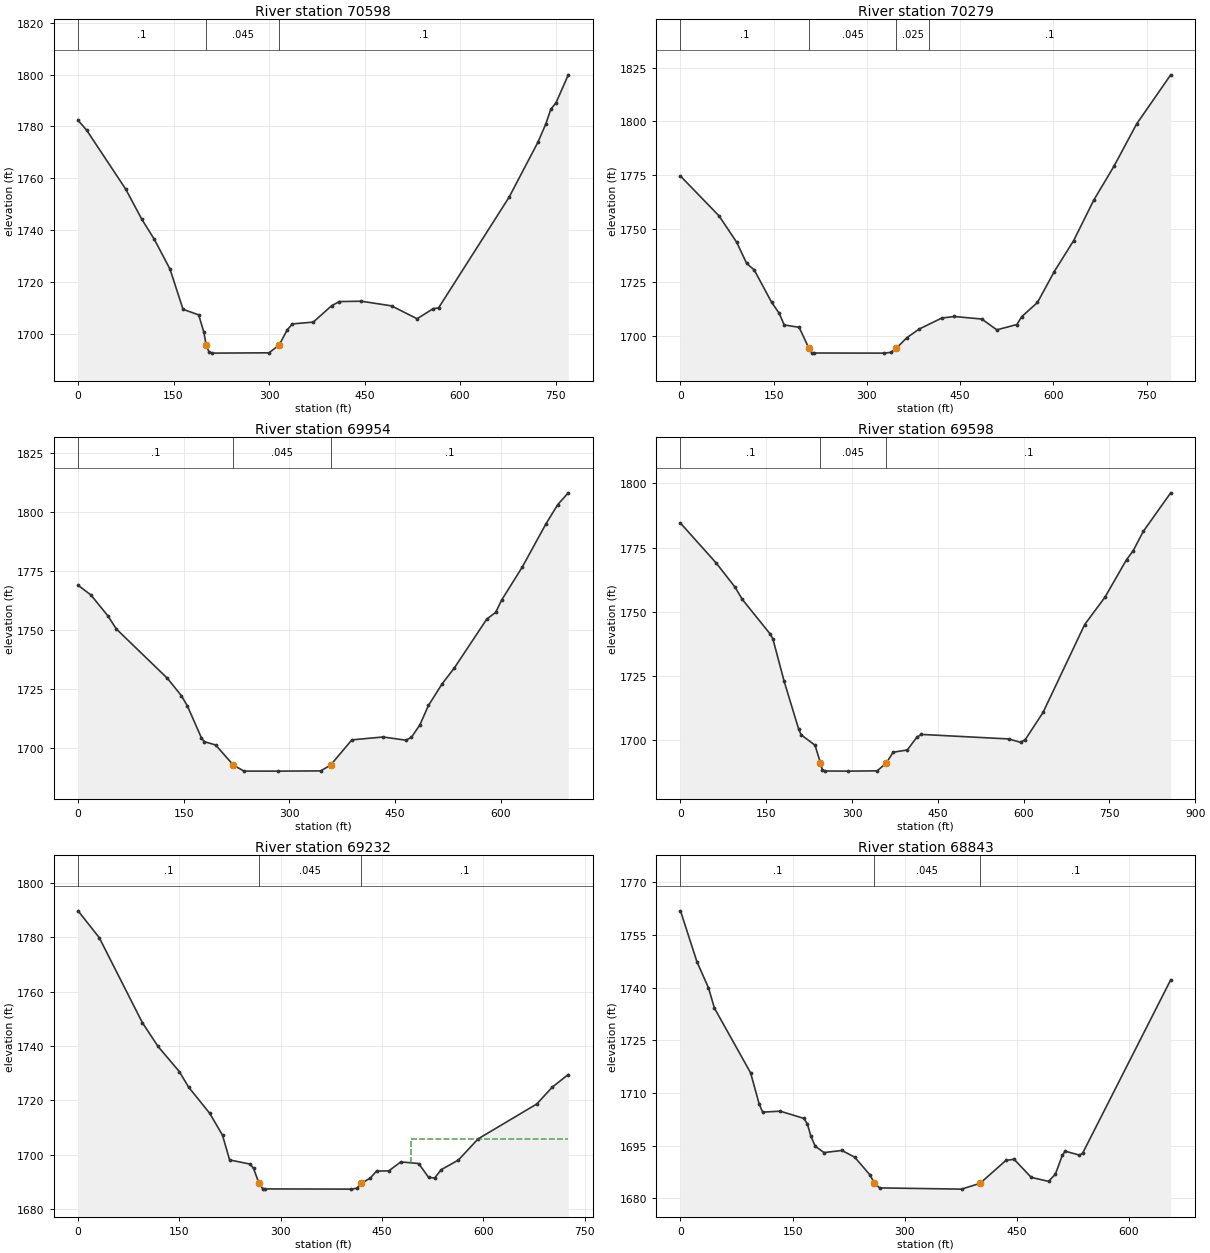
Type RM Length L Ch R = 1 ,70598   ,340.1,319.3,292.9
XS GIS Cut Line= 3
2194647.01490015673884.5980854352195112.02993005673985.351341913
2195398.78919849674051.228471149
#Sta/Elev= 30
       0 1782.37    13.5 1778.55    74.9 1755.77     100 1744.22   119.9 1736.38
   144.4 1724.92   164.9  1709.4   189.5 1707.23   197.6 1700.53  201.281695.656
   205.8 1692.79   209.9 1692.47     300 1692.59  316.051695.659   328.6 1701.48
   336.8 1703.76   369.5 1704.44   398.4  1710.8   410.5 1712.38   444.9 1712.51
   492.4 1710.72   532.5 1705.75     558 1709.66   566.2  1709.9   677.1 1752.69
   722.2 1773.83   734.5  1780.8   742.7 1786.68   750.9 1789.18     770 1799.92
#Mann= 3 ,-1,0
       0      .1       0  201.28    .045       0  316.05      .1       0
Bank Sta=201.28,316.05
XS Rating Curve= 0 ,0
Exp/Cntr(USF)=0,0
Exp/Cntr=0.3,0.1

Type RM Length L Ch R = 1 ,70279   ,324.8,324.5,323.4
XS GIS Cut Line= 3
2194622.35128094674286.1441725572195210.79622619674219.166699114
2195406.94454127674233.519014852
#Sta/Elev= 30
       0 1774.47    62.2 1755.86    90.4 1743.64   106.5 1733.76   118.6 1730.76
   146.8 1715.59   158.8 1710.55   166.9 1705.11     191 1703.99  206.581694.287
   211.2 1692.19   215.2 1692.03   327.8 1691.97   338.7 1692.32  347.51 1694.29
   364.2 1699.14   384.3 1703.22   420.5 1708.32   440.7 1709.04   484.9 1707.85
   509.1 1702.82   541.3 1705.29   549.3    1709   574.5 1715.57   601.6    1730
   632.8 1744.43   665.1 1763.26   697.9 1779.19     734  1798.7   788.9 1821.63
#Mann= 4 ,-1,0
       0      .1       0  206.58    .045       0  347.51    .025       0
     400      .1       0
Bank Sta=206.58,347.51
XS Rating Curve= 0 ,0
Exp/Cntr(USF)=0,0
Exp/Cntr=0.3,0.1

Type RM Length L Ch R = 1 ,69954   ,364,356.2,347.3
XS GIS Cut Line= 3
2194694.11285963674601.8951187852195215.58033143674539.701750588
2195378.23990979674487.076592884
#Sta/Elev= 30
       0 1768.87    18.2 1764.77    42.1    1756    54.4 1750.33     127  1729.4
   146.5 1722.14   155.2 1717.76   175.3 1704.12   179.3 1702.59   195.4 1701.17
  220.651692.609   235.7  1690.1   284.1 1690.09   344.5 1690.19   358.5 1692.61
   388.8 1703.34   433.1 1704.56   465.3 1703.21   473.4 1704.41   485.5 1709.75
   497.6 1717.94   517.2 1727.18   534.2 1733.75   580.4 1754.53   593.1  1757.4
   601.5 1762.59   630.9 1776.63   664.5 1794.94   681.3 1803.09   696.1 1808.04
#Mann= 3 ,-1,0
       0      .1       0  220.65    .045       0   358.5      .1       0
Bank Sta=220.65,358.5
XS Rating Curve= 0 ,0
Exp/Cntr(USF)=0,0
Exp/Cntr=0.3,0.1

Type RM Length L Ch R = 1 ,69598   ,382.2,366,346.7
XS GIS Cut Line= 3
2194727.60159635674994.1917489472195373.45580455674831.532170587
2195536.11538291674731.065960423
#Sta/Elev= 30
       0 1784.54    62.5 1769.01    95.5 1759.61   107.8 1754.95   157.3 1741.28
   161.5 1739.56   181.3 1722.97   206.8 1704.29     211 1702.16   235.3 1698.14
  244.771691.191   248.1  1688.6   252.2  1688.1   293.5 1688.05     344 1688.16
   359.91691.194   371.8  1695.4   396.6 1696.28   413.1 1701.19   421.3 1702.33
     574 1700.57   594.6 1699.25   602.8 1700.29     634 1710.89   706.8 1745.08
   742.4 1755.77   780.1 1770.37   791.5 1773.76   809.2  1781.3   857.2 1796.33
#Mann= 3 ,-1,0
       0      .1       0  244.77    .045       0   359.9      .1       0
Bank Sta=244.77,359.9
XS Rating Curve= 0 ,0
Exp/Cntr(USF)=0,0
Exp/Cntr=0.3,0.1

Type RM Length L Ch R = 1 ,69232   ,388.3,388.9,384.8
XS GIS Cut Line= 2
2194880.69296422675410.4089053392195516.97896192675061.169222389
#Sta/Elev= 30
       0 1789.74    31.3  1779.9    95.2 1748.61   118.4 1739.86     150 1730.58
   163.7 1724.88     195 1715.24   213.9 1707.18   224.4  1698.1   254.9 1696.57
   259.8 1694.99  267.99 1689.44   273.2 1687.58   277.4 1687.44   404.1 1687.36
     413 1687.66  419.281689.444   432.9 1691.48     442 1694.01   460.1 1694.07
   477.8 1697.38   504.3 1696.78     519 1691.69   527.9 1691.45   537.8 1694.53
   563.2 1698.07   592.3 1705.84   679.3  1718.7   702.1 1724.87   725.8 1729.52
#Mann= 3 ,-1,0
       0      .1       0  267.99    .045       0  419.28      .1       0
#XS Ineff= 2 , 0
                          493.41         1705.72
Permanent Ineff=
       F       F
Bank Sta=267.99,419.28
XS Rating Curve= 0 ,0
Exp/Cntr(USF)=0,0
Exp/Cntr=0.3,0.1

Type RM Length L Ch R = 1 ,68843   ,337.2,343.4,347.2
XS GIS Cut Line= 2
2195100.76180553675735.7280620582195670.07032979675410.408905339
#Sta/Elev= 30
       0 1761.87      22 1747.38    37.4 1739.98    45.4 1734.18    93.8 1715.75
   105.3 1706.85   109.9 1704.57   133.4 1704.85   165.2 1702.78   169.8 1701.15
   174.4 1697.72   180.3 1694.86     192 1693.06   215.9 1693.67     233 1691.76
   253.6 1686.67  259.361684.318   266.5 1683.01     376 1682.66   400.71684.318
   435.3 1690.83   446.2 1691.16   469.2    1686   492.3 1684.87   501.5 1686.92
   510.7 1692.27   514.5 1693.46   533.7 1692.35   537.9 1692.89   655.7 1742.22
#Mann= 3 ,-1,0
       0      .1       0  259.36    .045       0   400.7      .1       0
Bank Sta=259.36,400.7
XS Rating Curve= 0 ,0
Exp/Cntr(USF)=0,0
Exp/Cntr=0.3,0.1

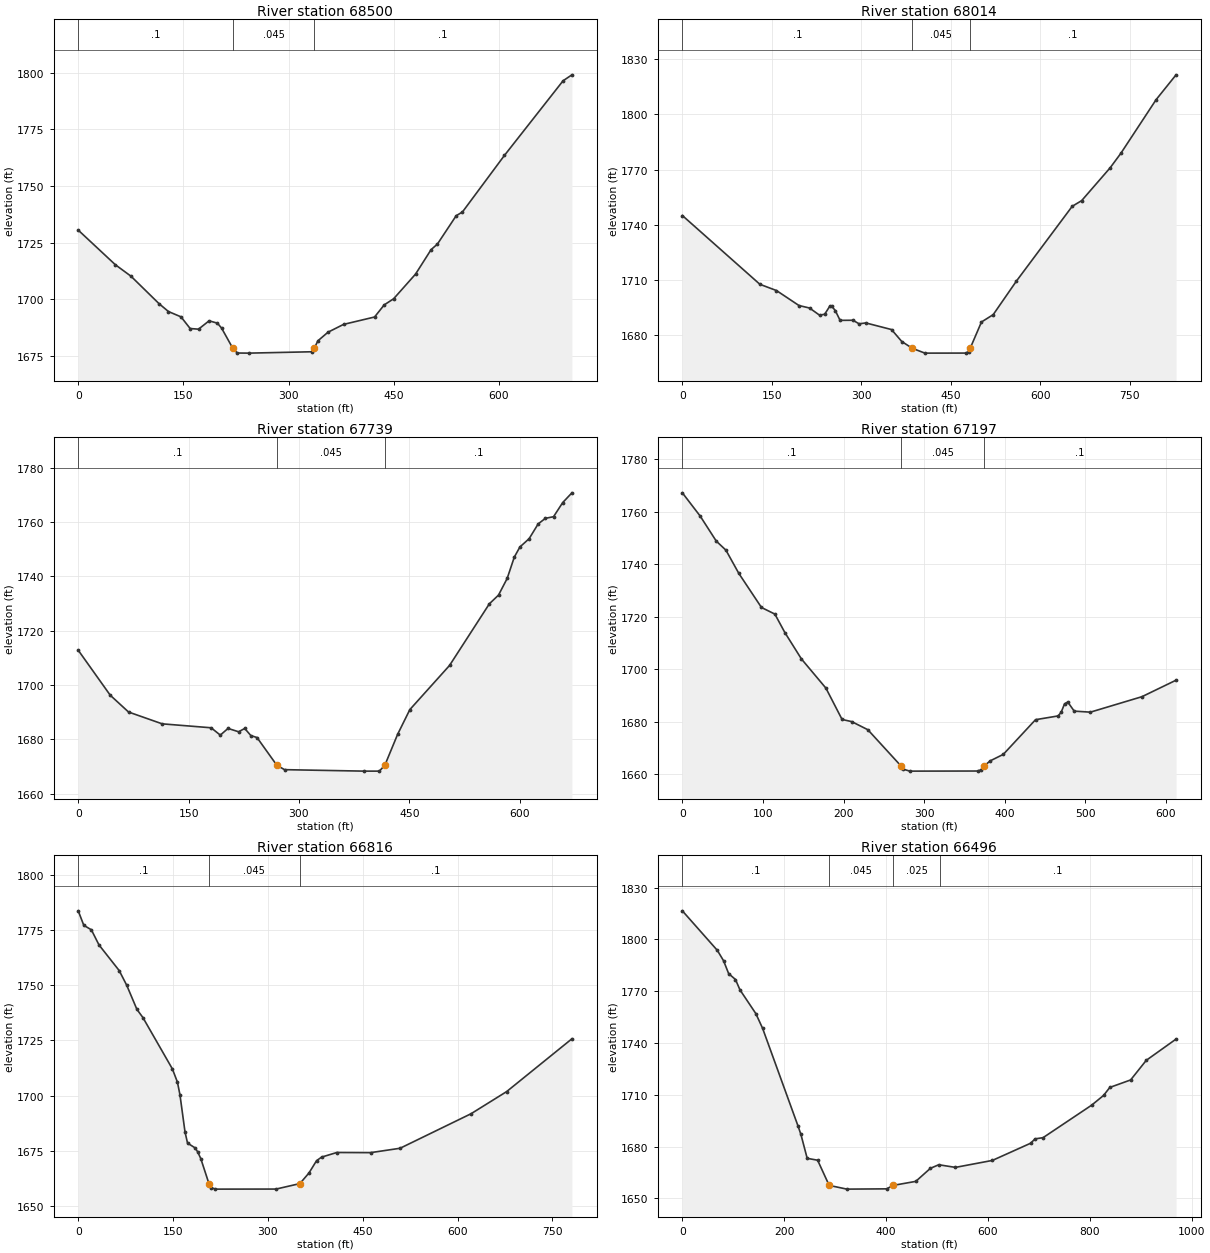
Type RM Length L Ch R = 1 ,68500   ,480.5,486,487.6
XS GIS Cut Line= 2
2195292.74794905675999.380102159 2195924.2498415675688.413261177
#Sta/Elev= 30
       0 1730.48    52.9  1715.2    75.2 1710.13   115.3 1697.97   128.7 1694.51
   146.5 1692.18   159.6 1687.01   171.5 1686.73   186.6 1690.42   198.4 1689.39
   204.4  1687.2  220.291678.345   226.8  1676.2   243.2 1676.15   332.8 1676.75
  336.511678.347   341.8 1681.61   356.1 1685.39   378.3 1688.84   422.5  1692.1
   436.3 1697.47   449.7 1700.16   480.9 1711.04   503.1 1721.86   512.1 1724.31
   538.9 1736.85   547.8 1738.49   607.7 1763.49   691.3 1796.45   703.9 1799.07
#Mann= 3 ,-1,0
       0      .1       0  220.29    .045       0  336.51      .1       0
Bank Sta=220.29,336.51
XS Rating Curve= 0 ,0
Exp/Cntr(USF)=0,0
Exp/Cntr=0.3,0.1

Type RM Length L Ch R = 1 ,68014   ,266.1,274.7,284.5
XS GIS Cut Line= 3
2195422.63231717676420.4742230122196054.27773278676168.591081816
2196186.03199125 676102.71395258
#Sta/Elev= 30
       0 1745.04   129.9 1707.69   157.7  1704.3   195.4 1696.16   213.1 1694.81
   229.9 1690.92   238.5 1691.44   247.1 1695.83     250 1695.92   256.2 1693.45
   264.3 1688.11   285.9 1688.16   296.2 1686.22   307.4 1686.71   350.5 1683.11
   367.7 1676.61  385.611672.877   406.5 1670.31   475.4 1670.34   479.7 1671.14
  482.23 1672.88   501.2 1687.21   520.9 1691.22   559.6 1709.35   653.3 1750.05
   669.1 1753.12   716.8 1770.93   734.7 1778.78   793.9 1807.97   827.3 1821.44
#Mann= 3 ,-1,0
       0      .1       0  385.61    .045       0  482.23      .1       0
Bank Sta=385.61,482.23
XS Rating Curve= 0 ,0
Exp/Cntr(USF)=0,0
Exp/Cntr=0.3,0.1

Type RM Length L Ch R = 1 ,67739   ,521.8,542.2,560
XS GIS Cut Line= 2
 2195598.3087511676606.435216809 2196244.1629593676424.639217465
#Sta/Elev= 30
       0 1712.76    43.5  1696.2    68.4 1690.01   114.1 1685.66   180.6 1684.21
   193.1 1681.51   203.6 1683.97     218 1682.74   226.3 1683.96   234.6 1681.34
     243 1680.62  269.981670.395   280.4 1668.79   388.4 1668.25   409.2 1668.25
  416.691670.395   434.1  1681.8   450.7  1690.9   504.7 1707.17   558.8 1729.86
   571.2 1733.05     583  1739.2   592.7 1747.06   600.3 1750.78   612.8 1753.82
   625.1 1759.26   634.9 1761.32     646 1761.92   658.5 1767.13     671 1770.71
#Mann= 3 ,-1,0
       0      .1       0  269.98    .045       0  416.69      .1       0
Bank Sta=269.98,416.69
XS Rating Curve= 0 ,0
Exp/Cntr(USF)=0,0
Exp/Cntr=0.3,0.1

Type RM Length L Ch R = 1 ,67197   ,375.7,380.9,389.1
XS GIS Cut Line= 2
2195670.07032979677056.1411099212196282.43580126677037.004688938
#Sta/Elev= 30
       0 1767.16    22.1 1758.32    42.1 1748.78    54.1 1745.32    70.1 1736.47
    98.2 1723.51   114.8    1721   127.2 1713.98   147.8 1703.91   178.2  1692.8
   198.2 1680.89   210.2 1680.06   230.2 1676.98  271.481663.144   274.2 1661.96
   282.2 1661.22   366.3 1661.26   370.3 1661.67  374.231663.144   382.3 1665.17
   398.3  1667.6   438.3  1680.8   466.3 1682.23   470.1 1683.63   474.3 1686.83
   478.3 1687.52   486.3 1684.06   506.4 1683.67   570.4 1689.56   612.7 1695.84
#Mann= 3 ,-1,0
       0      .1       0  271.48    .045       0  374.23      .1       0
Bank Sta=271.48,374.23
XS Rating Curve= 0 ,0
Exp/Cntr(USF)=0,0
Exp/Cntr=0.3,0.1

Type RM Length L Ch R = 1 ,66816   ,305.3,319.5,336.2
XS GIS Cut Line= 3
2195751.40011897677414.9490033622196272.86759077677434.085424346
2196531.20927405 677453.22184533
#Sta/Elev= 30
       0 1783.63     8.8 1777.08    20.8 1775.04    32.8 1768.22    64.8  1756.6
    76.8  1749.9    92.8 1739.06   102.4  1735.3   148.9 1712.12   156.9 1706.13
   160.9 1700.42   168.9 1683.59   172.9 1678.54   184.9 1676.37   188.9 1674.58
   193.8 1671.57  206.75 1660.23   210.4 1658.41   216.9 1657.72     313 1657.75
  350.611660.231     365 1665.03     377  1670.6     385 1672.21     409 1674.29
   462.4 1674.22   509.1 1676.21   621.4 1691.84   677.6 1701.84   780.9 1725.74
#Mann= 3 ,-1,0
       0      .1       0  206.75    .045       0  350.61      .1       0
Bank Sta=206.75,350.61
XS Rating Curve= 0 ,0
Exp/Cntr(USF)=0,0
Exp/Cntr=0.3,0.1

Type RM Length L Ch R = 1 ,66496   ,330.2,353.5,373.4
XS GIS Cut Line= 4
2195622.36887648677618.901300041 2195780.2443496677695.446983975
2196206.02971648677791.1290888932196555.26939943677867.674772827
#Sta/Elev= 30
       0 1816.51    68.7 1793.61    80.9  1787.6    90.9 1780.15   104.3 1776.74
   113.1 1770.75   144.3 1756.99   157.6 1748.43   227.1 1691.91   232.8 1687.01
   245.1 1673.18   265.6 1672.09  288.251657.514     323 1655.35   401.1 1655.51
     4141657.515   458.3 1659.84     487 1667.39   503.4 1669.47   536.2 1667.94
   608.7 1671.97   683.7 1681.91   692.6 1684.46   708.2 1685.14   803.5 1703.94
     827 1709.59   839.3 1714.24   880.2 1718.58   910.9 1729.94   969.4 1742.24
#Mann= 4 ,-1,0
       0      .1       0  288.25    .045       0     414    .025       0
  505.45      .1       0
Bank Sta=288.25,414
XS Rating Curve= 0 ,0
Exp/Cntr(USF)=0,0
Exp/Cntr=0.3,0.1

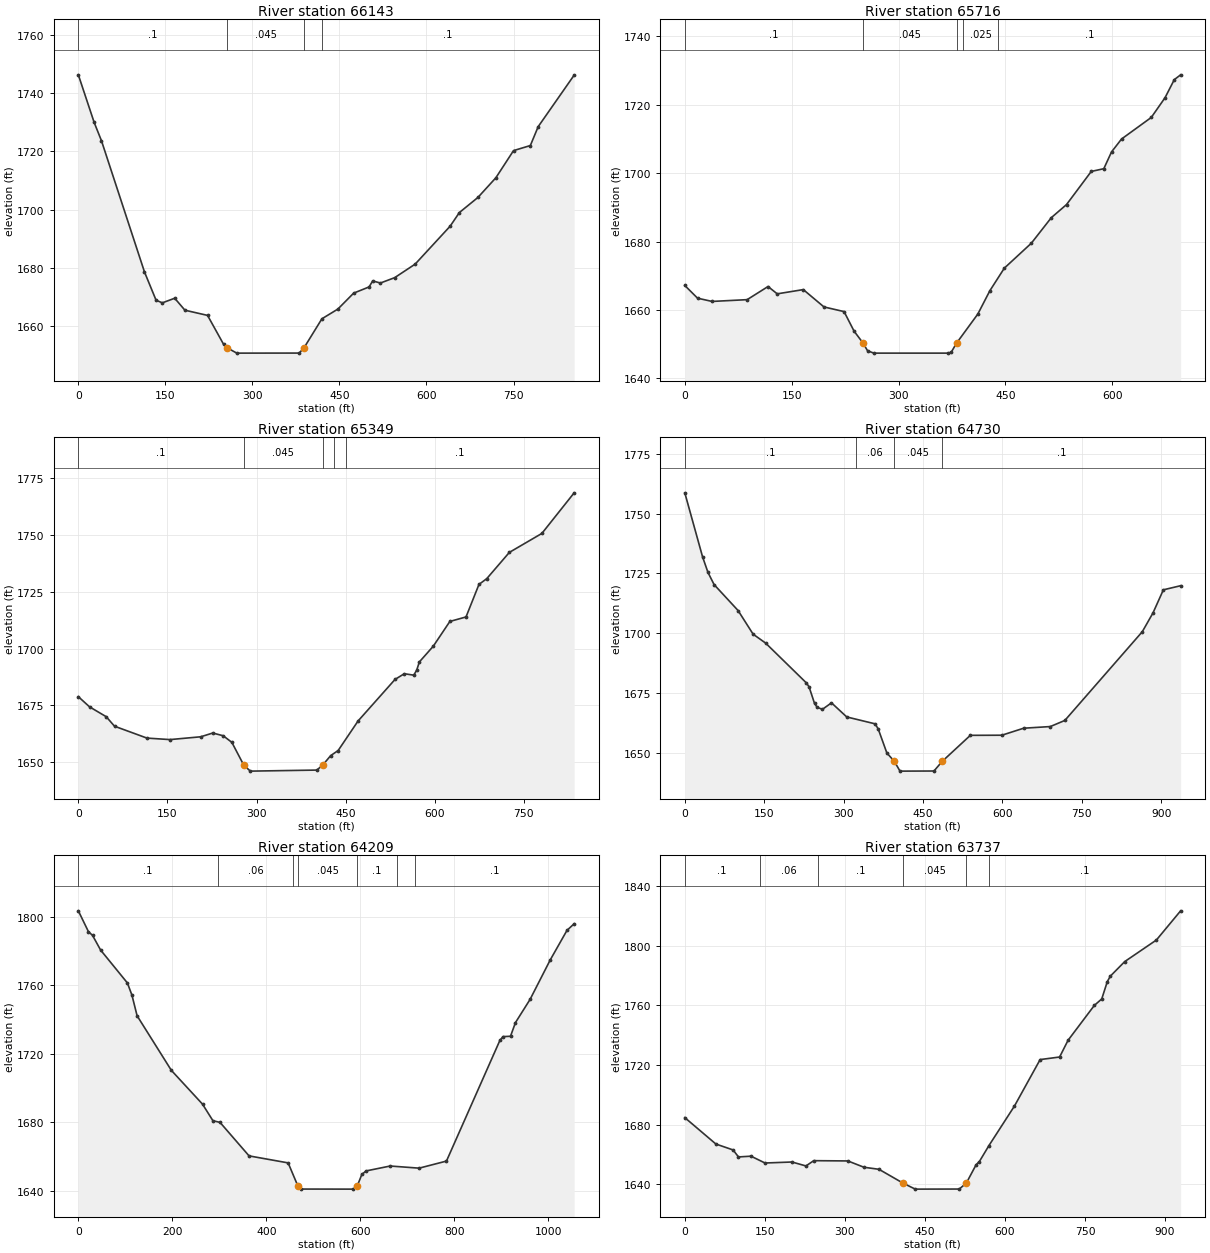
Type RM Length L Ch R = 1 ,66143   ,423.1,426.6,428.9
XS GIS Cut Line= 4
2195593.66424501677867.6747728272195679.77813944677977.709193482
2196081.64298009678202.5621400392196273.00718992678370.005823645
#Sta/Elev= 30
       0 1746.26    27.3 1729.91    39.9 1723.62     114 1678.61     134  1668.9
   144.8 1668.01   166.1 1669.59   183.7 1665.48   222.7  1663.7   250.2 1653.82
  256.811652.534   273.1 1650.75   380.6 1650.77  388.811652.536   419.8 1662.54
   447.3 1665.87   474.5 1671.34   501.1 1673.47   507.3 1675.53   520.6 1674.81
   545.2 1676.65   580.5  1681.3   640.8 1694.32   656.7    1699   688.6 1704.17
   719.6 1710.94     750 1720.25     779 1721.99   792.5 1728.47   854.5 1746.16
#Mann= 4 ,-1,0
       0      .1       0  256.81    .045       0  388.81    .025       0
  419.73      .1       0
Bank Sta=256.81,388.81
XS Rating Curve= 0 ,0
Exp/Cntr(USF)=0,0
Exp/Cntr=0.3,0.1

Type RM Length L Ch R = 1 ,65716   ,368.5,367.8,366.9
XS GIS Cut Line= 2
 2195373.5954037678279.1078239732195966.82445419 678642.69982266
#Sta/Elev= 30
       0 1667.19    17.9 1663.47    38.3 1662.52    87.5 1663.04   116.8 1666.88
   129.7 1664.74   166.3 1665.98   195.3 1660.91   223.5 1659.55   237.6 1653.82
  250.241650.324   256.4 1648.12   265.2 1647.41     369 1647.41   373.7 1647.61
  381.331650.323   411.2 1658.83   428.1 1665.65   448.4 1672.25   486.3 1679.54
   514.4 1687.02   535.7 1690.84   570.4 1700.52     588 1701.32   598.8 1706.21
   612.9    1710   654.6  1716.3   673.9 1722.06   686.9 1727.35   695.8 1728.76
#Mann= 5 ,-1,0
       0      .1       0  250.24    .045       0  381.33      .1       0
     390    .025       0     440      .1       0
Bank Sta=250.24,381.33
XS Rating Curve= 0 ,0
Exp/Cntr(USF)=0,0
Exp/Cntr=0.3,0.1

Type RM Length L Ch R = 1 ,65349   ,670.1,618.9,548.8
XS GIS Cut Line= 3
 2195143.9583519678570.9382439722195694.13045517678901.041505938
2195871.14234927678977.587189872
#Sta/Elev= 30
       0 1678.81    18.9 1674.33    46.9    1670    60.9 1665.81   115.5 1660.58
   154.2 1659.92   205.9 1661.15   226.3 1662.81   243.8 1661.61   258.4  1658.7
  278.481648.658   289.5 1646.04   401.4  1646.5  411.161648.658   424.7 1652.86
   437.3 1655.11   470.8 1668.11     533  1686.4   548.6 1688.91   564.5 1688.28
   569.4 1690.42     574 1694.11   597.3 1700.99   625.3 1711.92   652.5  1713.9
   674.3 1728.23   687.4 1730.75   725.4 1742.31   780.2 1750.67   834.5 1768.53
#Mann= 5 ,-1,0
       0      .1       0  278.48    .045       0  411.16      .1       0
     430    .025       0     450      .1       0
Bank Sta=278.48,411.16
XS Rating Curve= 0 ,0
Exp/Cntr(USF)=0,0
Exp/Cntr=0.3,0.1

Type RM Length L Ch R = 1 ,64730   ,554.2,520.6,483.6
XS GIS Cut Line= 4
2194885.61666862679561.2480298692195062.62856272679379.452030526
2195483.62982435679145.0308734782195684.56224468679140.246768232
#Sta/Elev= 30
       0 1758.65    33.6 1731.84    43.8 1725.35    55.3 1720.28   100.6 1709.43
   129.1 1699.52   152.7  1695.8     229 1679.29   234.6 1677.58   245.1 1670.55
   250.2 1668.89   260.1 1668.12   277.1 1670.81   305.9 1664.91   359.5 1662.03
   365.4 1659.87   381.7 1649.84  395.941646.314   406.5 1642.25   470.7  1642.3
  486.151646.313   539.4 1657.22   598.9 1657.27   640.1  1660.2   690.4 1660.89
   717.9 1663.45   864.2 1700.56   884.5 1708.46     904 1718.08   936.6  1719.8
#Mann= 4 ,-1,0
       0      .1       0  323.74     .06       0  395.94    .045       0
  486.15      .1       0
Bank Sta=395.94,486.15
XS Rating Curve= 0 ,0
Exp/Cntr(USF)=0,0
Exp/Cntr=0.3,0.1

Type RM Length L Ch R = 1 ,64209   ,466,471.7,473.8
XS GIS Cut Line= 4
2195278.04507172 679996.994422562195498.92721092679845.864537843
2195746.93522687679376.9743826942195952.31686507679221.969372727
#Sta/Elev= 30
       0  1803.5    21.5 1791.34    30.2 1789.19    47.4 1780.62   104.4 1761.42
   114.1  1754.3   125.1 1742.24     198  1710.4   264.3 1690.69   286.5    1681
   301.6 1680.03   363.4 1660.48   446.6 1656.39  467.641642.694   473.3 1641.12
   585.2 1641.08  593.361642.693   603.5 1649.66   612.5  1651.7   663.8 1654.57
   725.4 1653.32   783.6 1657.45   897.3 1727.87     904 1730.09   919.9 1730.29
   930.5 1738.29   961.6 1751.83  1004.4 1774.81  1040.2 1792.13  1055.4 1795.95
#Mann= 7 ,-1,0
       0      .1       0  297.64     .06       0  457.64      .1       0
  467.64    .045       0  593.36      .1       0  677.64    .025       0
  717.64      .1       0
Bank Sta=467.64,593.36
XS Rating Curve= 0 ,0
Exp/Cntr(USF)=0,0
Exp/Cntr=0.3,0.1

Type RM Length L Ch R = 1 ,63737   ,404.4,416.6,426
XS GIS Cut Line= 3
2195801.18698036680190.7506850182196177.07412952679582.356020899
2196320.45376374679423.475885684
#Sta/Elev= 30
       0 1684.63    58.3 1666.87    90.5  1662.9   100.6  1658.2   124.1 1658.71
   150.3 1654.12   200.9 1654.79   227.1 1652.14   241.6 1655.69   305.6 1655.51
   335.7 1651.27   363.9 1649.89  408.861640.622   431.9 1636.56   514.4 1636.62
  527.591640.623     546 1652.98     552 1655.08     570 1665.85   617.8 1692.42
   665.9 1723.64   702.4 1725.37   718.2 1736.59   767.5 1760.06   781.4 1764.42
   791.8 1776.06   797.5 1779.74   824.5 1789.53   883.8 1804.02   929.2 1823.64
#Mann= 6 ,-1,0
       0      .1       0     140     .06       0     250      .1       0
  408.86    .045       0  527.59    .025       0     570      .1       0
Bank Sta=408.86,527.59
XS Rating Curve= 0 ,0
Exp/Cntr(USF)=0,0
Exp/Cntr=0.3,0.1

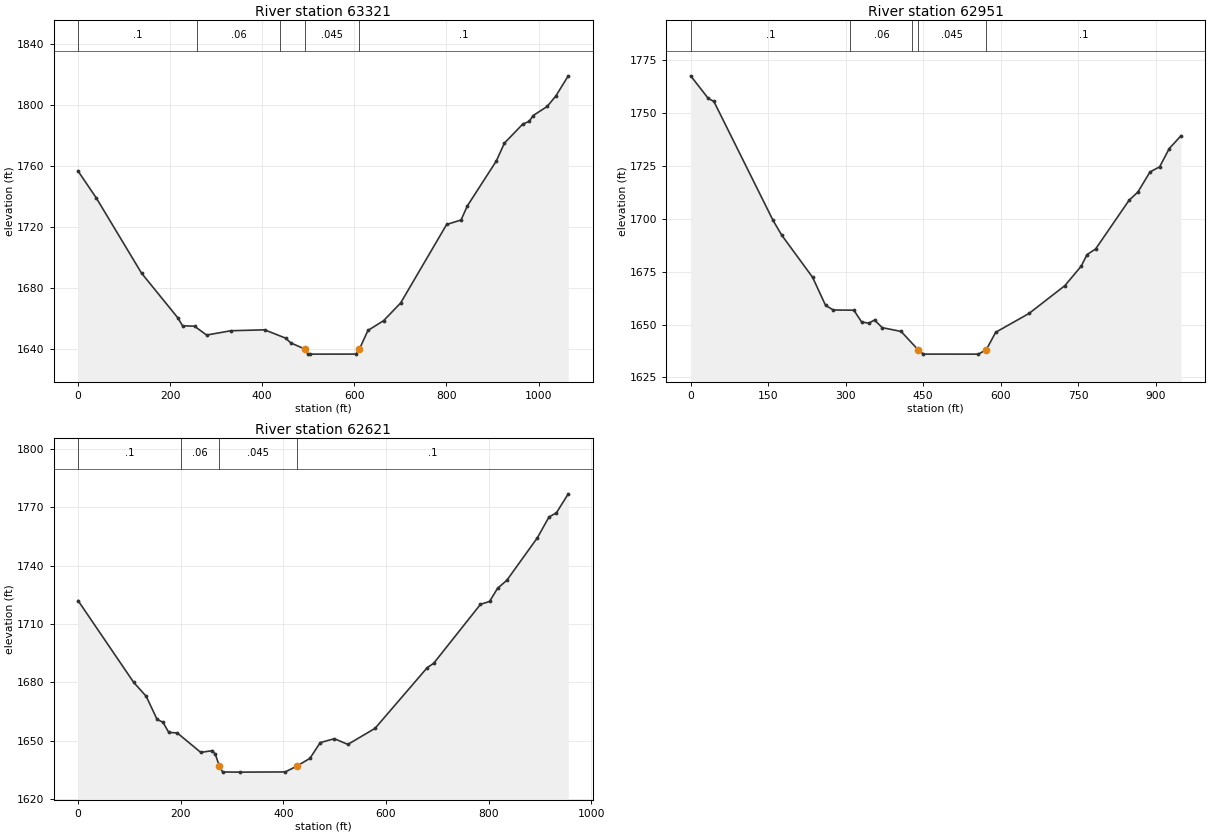
Type RM Length L Ch R = 1 ,63321   ,377.6,370.2,366.1
XS GIS Cut Line= 4
 2196064.6954973680496.8855797022196165.44875378680291.503941496
2196556.83640394679834.2391620952196661.46478567 679624.98239864
#Sta/Elev= 30
       0 1756.48    39.8 1738.76   137.8 1689.64   216.8 1660.29   226.9 1655.15
   252.9 1654.84   279.2 1649.06   331.9 1651.88   405.2 1652.48   450.8 1647.03
   462.1 1643.89  492.981639.841     499 1636.84   503.6 1636.56     604 1636.58
  611.031639.838   629.5 1652.06   663.7 1658.52   700.5 1670.04   800.5  1721.5
   831.8 1724.41   845.3 1733.57   908.5 1763.14   925.8 1774.73     966 1787.32
   979.4 1788.94   988.4 1792.84  1018.8 1798.79  1037.6 1805.64  1064.6 1818.85
#Mann= 5 ,-1,0
       0      .1       0  258.76     .06       0  438.76      .1       0
  492.98    .045       0  611.03      .1       0
Bank Sta=492.98,611.03
XS Rating Curve= 0 ,0
Exp/Cntr(USF)=0,0
Exp/Cntr=0.3,0.1

Type RM Length L Ch R = 1 ,62951   ,323,329.8,333.9
XS GIS Cut Line= 4
2196320.45376374680702.2672179082196448.33289697680562.762708938
 2196766.0931674 680136.498931532196847.47079763679923.367042826
#Sta/Elev= 30
       0 1767.44      34 1756.78    44.9 1755.36   159.4  1699.2   176.1 1692.26
     236 1672.31   261.1 1659.08     276 1656.88     316 1656.77   330.9 1651.22
   344.6 1650.66   355.9 1652.13   370.8 1648.54   407.5 1646.73  440.131638.126
   450.4 1636.04   557.1 1636.03  572.321638.126   590.5 1646.34   655.2 1655.26
   724.5 1668.38   756.1 1677.58   767.3 1683.01     784 1685.68   848.6 1708.64
   865.8 1712.57   889.3 1722.07   907.9 1724.46   926.5 1733.09   949.1 1739.12
#Mann= 5 ,-1,0
       0      .1       0  309.25     .06       0  429.25      .1       0
  440.13    .045       0  572.32      .1       0
Bank Sta=440.13,572.32
XS Rating Curve= 0 ,0
Exp/Cntr(USF)=0,0
Exp/Cntr=0.3,0.1

Type RM Length L Ch R = 1 ,62621   ,489.3,507.7,515.1
XS GIS Cut Line= 3
2196661.46478567 680783.644848142197068.35293683680310.879567742
2197227.23307205680020.245174055
#Sta/Elev= 30
       0 1722.05   108.4 1680.04   132.9 1672.83     154    1661   165.3  1659.6
   176.7 1654.35   193.2 1654.08   239.1 1644.08   261.7 1644.99   267.5 1643.06
  275.381636.965   281.6 1634.03   314.6 1633.95   403.6 1634.05  425.65 1636.96
   451.8 1641.03   471.7  1649.1   499.3 1651.11   525.6 1648.19   578.5 1656.41
   680.4 1687.65   692.7  1689.8     784 1720.12   801.7 1721.59   817.2 1728.32
   835.4 1732.49   894.7 1754.25   917.4 1764.95   931.9 1767.11     955 1776.86
#Mann= 4 ,-1,0
       0      .1       0     200     .06       0  275.38    .045       0
  425.65      .1       0
Bank Sta=275.38,425.65
XS Rating Curve= 0 ,0
Exp/Cntr(USF)=0,0
Exp/Cntr=0.3,0.1