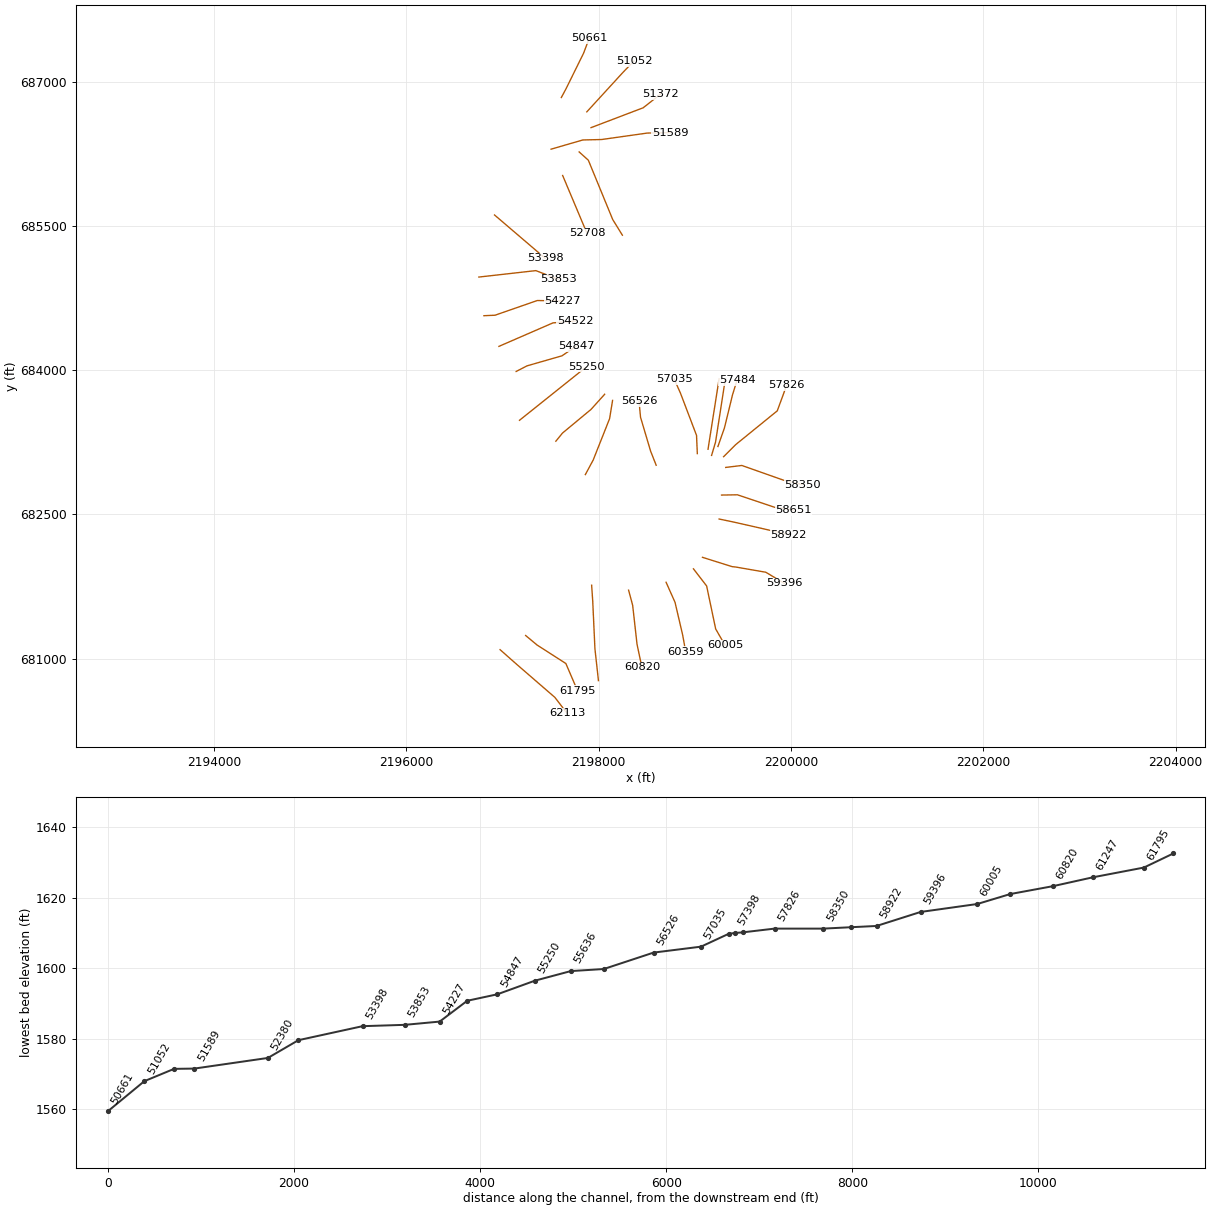
HEC-RAS study BUCKHANR_U.prj: BUCKHANR_U

--- BUCKHANR_U.g01 (geometry) --- (continued)

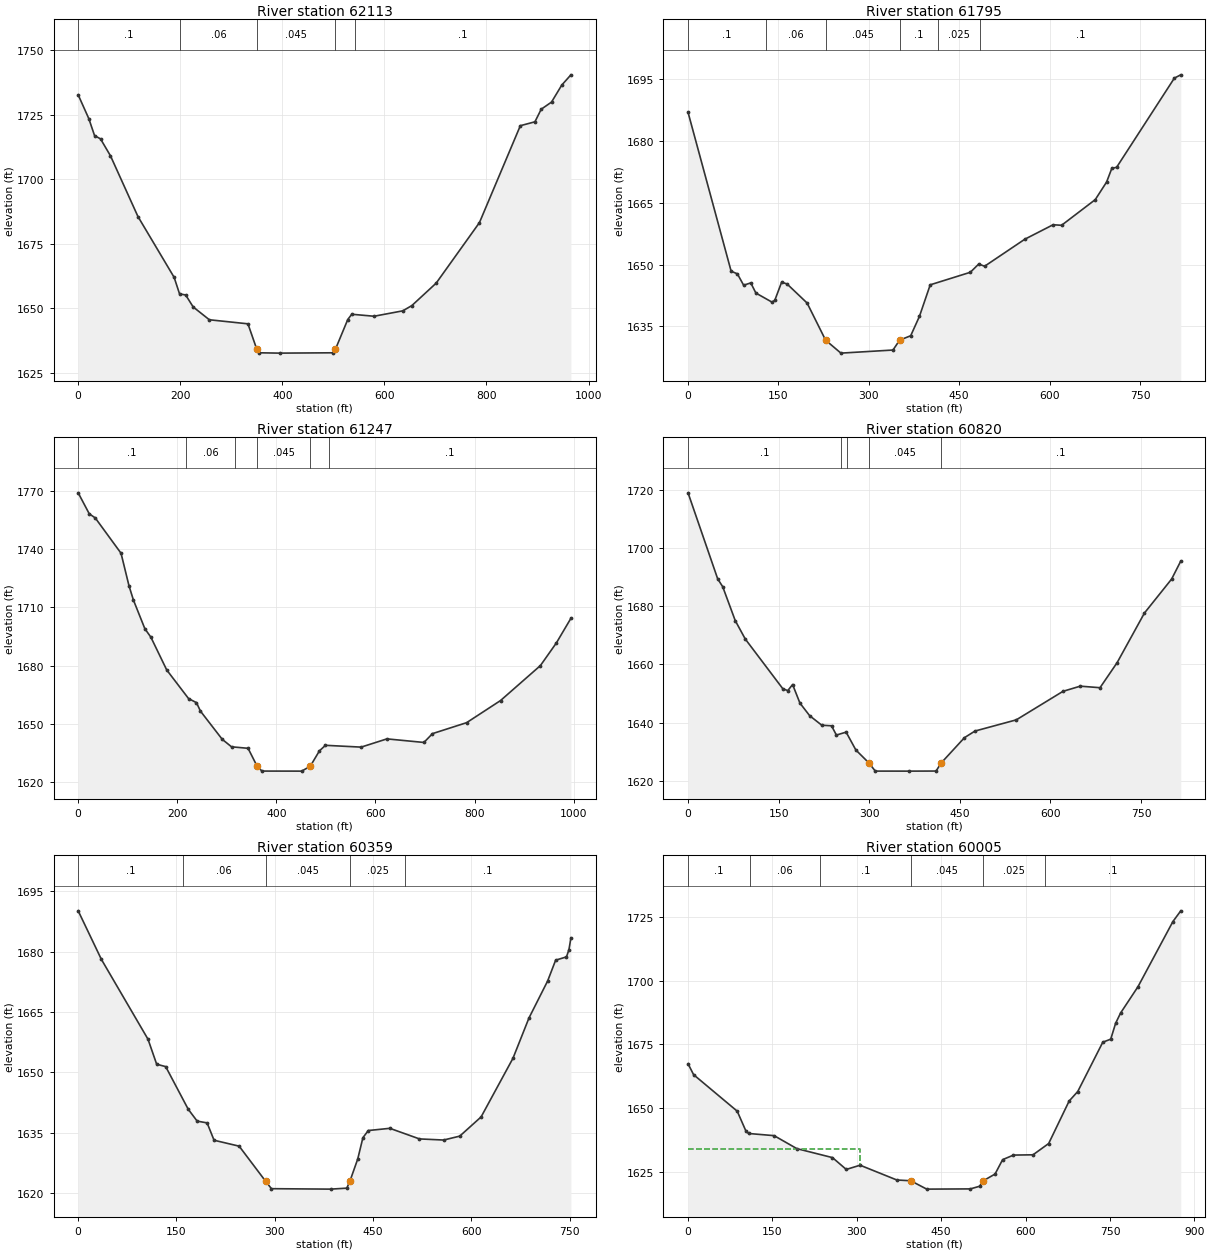
Type RM Length L Ch R = 1 ,62113   ,300.4,317.8,325.3
XS GIS Cut Line= 4
2196975.34993085681093.6548680732197141.98031657680946.400108605
2197544.99334248 680597.63883618 2197672.8724757680431.008450466
#Sta/Elev= 30
       0 1732.64    20.8 1723.44    32.1 1716.84    43.8 1715.57    63.3    1709
   117.1 1685.47     188  1661.9   198.6 1655.49   210.6 1655.06   225.3 1650.42
     257 1645.45   332.6 1643.88  349.871634.056   355.2 1632.65   394.5 1632.52
   499.3 1632.65  504.091634.052   528.2 1645.55     536 1647.59   579.7 1646.82
     636 1648.91   653.8 1650.96   701.4 1659.65   786.2 1683.12   866.3 1720.68
   894.9 1722.19   907.2 1727.07   927.4 1729.83   947.5 1736.43   965.4  1740.4
#Mann= 5 ,-1,0
       0      .1       0     200     .06       0  349.87    .045       0
  504.09    .025       0  542.37      .1       0
Bank Sta=349.87,504.09
XS Rating Curve= 0 ,0
Exp/Cntr(USF)=0,0
Exp/Cntr=0.3,0.1

Type RM Length L Ch R = 1 ,61795   ,638.3,548.7,511.8
XS GIS Cut Line= 4
2197241.23654678681240.8844312542197359.88513166681142.010610522
2197659.33156016 680949.912901672197780.80511135680667.416271006
#Sta/Elev= 30
       0 1686.96    71.5  1648.4    81.9 1647.75    92.3 1644.99   104.1 1645.56
   112.6 1643.09   139.2  1640.9   143.9  1641.3   155.3 1645.73   164.3  1645.3
   197.6 1640.67  228.281631.657   253.7 1628.51   340.1 1629.26   351.11631.657
   369.5 1632.73     384 1637.43   401.9 1645.09   468.4 1648.13   482.4 1650.13
   492.2  1649.6   558.9 1656.16   605.8 1659.67   619.9 1659.54   675.8 1665.77
   694.6 1670.04   703.2 1673.33   711.3 1673.63   807.1 1695.27   817.7 1696.06
#Mann= 6 ,-1,0
       0      .1       0     130     .06       0  228.28    .045       0
   351.1      .1       0  414.45    .025       0  484.45      .1       0
Bank Sta=228.28,351.1
XS Rating Curve= 0 ,0
Exp/Cntr(USF)=0,0
Exp/Cntr=0.3,0.1

Type RM Length L Ch R = 1 ,61247   ,421.5,427.1,431.1
XS GIS Cut Line= 4
2197927.70335929681763.5031979822197939.00322452681596.830185891
2197961.60295497681105.2860485352197998.32751696680771.940024352
#Sta/Elev= 30
       0 1768.92    22.4 1758.11    34.4 1756.03    86.5 1737.84   102.6 1721.05
   111.5 1713.76   134.6    1699   146.7 1694.67   178.7  1677.8   222.8 1663.07
   238.8 1660.96   246.8 1656.62   290.8  1642.1   309.5 1638.26   342.9 1637.49
  361.161628.271   370.9 1625.78   451.1 1625.75  468.431628.272     487 1636.21
   499.1 1639.03   571.1  1638.1   623.2 1642.34   697.8  1640.5   715.1 1645.04
     784 1650.68   852.4 1662.05   932.9 1680.04   965.1 1691.68   994.5 1704.37
#Mann= 6 ,-1,0
       0      .1       0  217.06     .06       0  317.06      .1       0
  361.16    .045       0  468.43    .025       0  507.06      .1       0
Bank Sta=361.16,468.43
XS Rating Curve= 0 ,0
Exp/Cntr(USF)=0,0
Exp/Cntr=0.3,0.1

Type RM Length L Ch R = 1 ,60820   ,451.1,460.7,467.4
XS GIS Cut Line= 4
  2198311.898777681712.6538044632198354.27327159681554.455691291
 2198399.4727325681150.4855094412198450.32212602680910.363373377
#Sta/Elev= 30
       0 1719.16    49.1  1689.5    57.4  1686.8    78.1 1675.14    94.7 1668.79
   156.8 1651.67   165.1 1650.99   173.1  1653.1   185.2 1646.71   201.3 1642.36
   221.4 1639.07   237.5 1638.88   245.6 1635.68   261.7 1636.69   277.8 1630.54
  299.451626.067     310 1623.26   365.7 1623.25   410.6 1623.28  419.071626.065
   457.6 1634.78     475 1637.06   543.4 1640.92   620.7 1650.75   649.3 1652.53
     682    1652   710.3 1660.63   755.6 1677.75   800.6 1689.46   815.7 1695.64
#Mann= 5 ,-1,0
       0      .1       0  253.77     .06       0  263.77     .05       0
  299.45    .045       0  419.07      .1       0
Bank Sta=299.45,419.07
XS Rating Curve= 0 ,0
Exp/Cntr(USF)=0,0
Exp/Cntr=0.3,0.1

Type RM Length L Ch R = 1 ,60359   ,355.8,354.1,352.6
XS GIS Cut Line= 4
2198701.74412731681794.5778273552198794.96801543681585.530320664
2198874.06707202681246.5343638672198905.14170139681074.211419162
#Sta/Elev= 30
       0 1690.12    35.4 1678.07   106.6 1658.23   119.8 1652.03   133.6 1651.43
     168 1640.84   181.6  1637.9   196.8 1637.46   207.4 1633.15   245.7 1631.68
  285.951623.001     295 1621.12   385.3 1621.01     410 1621.25   414.81623.003
   426.7 1628.49   434.6 1633.78   442.8 1635.56   475.7 1636.11   520.9 1633.48
   557.8  1633.2   582.4 1634.17     615 1638.94   663.7 1653.52   688.1 1663.52
   716.6 1672.71   728.8 1677.87   745.3 1678.68   749.1 1680.47   752.1 1683.42
#Mann= 5 ,-1,0
       0      .1       0     160     .06       0  285.95    .045       0
   414.8    .025       0  498.89      .1       0
Bank Sta=285.95,414.8
XS Rating Curve= 0 ,0
Exp/Cntr(USF)=0,0
Exp/Cntr=0.3,0.1

Type RM Length L Ch R = 1 ,60005   ,521.8,608.9,707.2
XS GIS Cut Line= 4
 2198986.1246424681934.345186741 2199123.4180049681756.372309422
2199217.48938291681308.897646451 2199314.1032306681141.094647836
#Sta/Elev= 30
       0 1667.36     9.9 1663.07    87.4 1648.76   102.5 1641.15   107.6 1640.01
     153 1639.16   193.4 1634.07   256.7 1630.55   281.2 1625.91   305.8 1627.57
   371.1 1621.77  395.811621.469   424.2 1618.19   501.7 1618.28   518.2 1619.32
  524.671621.469   545.6  1624.1   559.1 1629.76   578.4 1631.54   613.1 1631.65
   640.9 1636.07   677.3 1652.74   692.6 1656.47   737.1 1675.81   751.2    1677
   759.9 1683.23   768.7 1687.25   799.6 1697.56   861.7 1723.12   875.7 1727.33
#Mann= 6 ,-1,0
       0      .1       0     110     .06       0  234.78      .1       0
  395.81    .045       0  524.67    .025       0  634.78      .1       0
#XS Ineff= 2 , 0
          305.23 1633.96
Permanent Ineff=
       F       F
Bank Sta=395.81,524.67
XS Rating Curve= 0 ,0
Exp/Cntr(USF)=0,0
Exp/Cntr=0.3,0.1

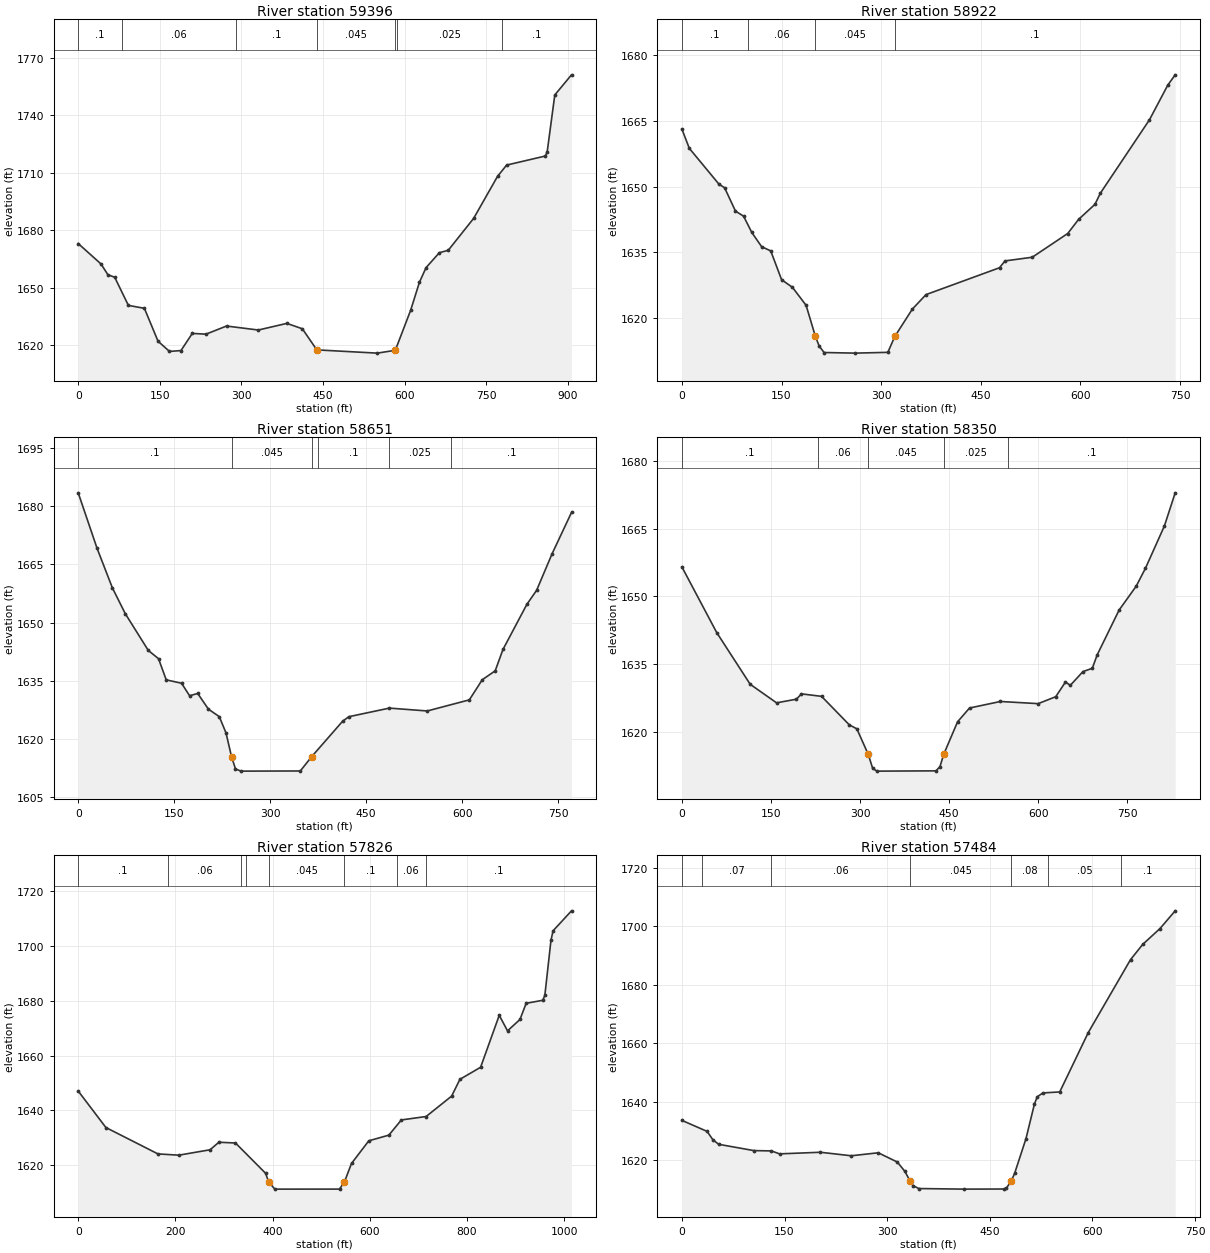
Type RM Length L Ch R = 1 ,59396   ,481.3,473.7,481.3
XS GIS Cut Line= 5
2199080.19602041682053.841261512 2199387.8348512681957.227413825
2199431.05683569681952.1424744732199738.69566649681898.750611277
2199934.46583154681781.797006182
#Sta/Elev= 30
       0 1673.06    41.9  1662.4    54.5 1656.82    67.1 1655.46    92.2 1640.82
   121.6 1639.29   146.7 1622.13   167.7 1616.83   188.8 1617.27   209.6 1626.21
   234.8 1625.83   272.5 1630.06   330.9 1627.98   383.3 1631.44   411.8 1628.63
   438.41617.631   549.4 1615.94  582.591617.411   610.7 1638.21   626.9 1652.85
   639.1 1660.51   663.5 1668.27   679.9 1669.55   726.5 1686.16   770.5 1708.11
   787.1 1713.94   858.4 1718.68   861.7 1720.99   875.6 1750.48   906.3 1760.98
#Mann= 7 ,-1,0
       0      .1       0      80     .06       0     290      .1       0
   438.4    .045       0  582.59      .1       0  585.97    .025       0
  778.21      .1       0
Bank Sta=438.4,582.59
XS Rating Curve= 0 ,0
Exp/Cntr(USF)=0,0
Exp/Cntr=0.3,0.1

Type RM Length L Ch R = 1 ,58922   ,279,271.3,264.4
XS GIS Cut Line= 4
2199253.23026588682452.3176352392199410.86338579682419.265529451
2199680.36517145682358.2462572282199977.83412354682289.599575976
#Sta/Elev= 30
       0 1663.14    11.2 1658.74    55.8 1650.56    64.3 1649.74    80.7  1644.4
    92.9 1643.25   105.2 1639.54     120 1636.29   133.8 1635.31   150.1 1628.74
   166.5 1626.99     187 1622.89  200.991615.795   206.7 1613.58   214.1 1612.11
   260.9 1611.97   310.1 1612.15  320.651615.796     347 1622.03   367.5 1625.33
   478.2 1631.47   486.5 1633.03   527.5 1633.87   580.9 1639.29   597.3 1642.52
   621.9 1645.95   630.1 1648.51     704 1665.27   731.6 1673.19   742.7 1675.53
#Mann= 4 ,-1,0
       0      .1       0     100     .06       0  200.99    .045       0
  320.65      .1       0
Bank Sta=200.99,320.65
XS Rating Curve= 0 ,0
Exp/Cntr(USF)=0,0
Exp/Cntr=0.3,0.1

Type RM Length L Ch R = 1 ,58651   ,302.2,301.3,300.1
XS GIS Cut Line= 4
2199278.65496264682701.4796634842199443.91549158 682704.02213316
2199830.37088233682574.3561796862200026.14104738 682546.38901325
#Sta/Elev= 30
       0 1683.51    29.5 1669.16    53.5 1658.92    73.5 1652.31   109.5  1642.8
   125.5 1640.66   137.5  1635.2   161.5 1634.32     174 1631.09   186.7 1631.68
   203.5 1627.62   220.4  1625.7   230.9  1621.5  239.511615.371   245.7 1612.21
   254.2 1611.62     347 1611.66  364.831615.374   413.1 1624.51   422.9 1625.68
   486.2  1627.9   545.3 1627.16   611.1 1630.03   631.3 1635.23   651.5 1637.53
   663.6 1643.04   700.9 1654.68   716.2 1658.33   740.4 1667.78   770.7 1678.44
#Mann= 6 ,-1,0
       0      .1       0  239.51    .045       0  364.83     .06       0
  375.28      .1       0  485.28    .025       0  582.91      .1       0
Bank Sta=239.51,364.83
XS Rating Curve= 0 ,0
Exp/Cntr(USF)=0,0
Exp/Cntr=0.3,0.1

Type RM Length L Ch R = 1 ,58350   ,435.6,523.8,603.3
XS GIS Cut Line= 4
2199321.87694713 682988.778736872199489.67994575683009.118494278
2199921.89979066682856.5703137192200120.21242539682810.805859551
#Sta/Elev= 30
       0 1656.56    58.7 1641.97   115.1 1630.49   159.5 1626.38   192.9 1627.19
   201.4 1628.37   235.3 1627.82     282 1621.49   294.7 1620.61  313.94 1614.92
   321.4 1611.82   328.6 1611.22     428 1611.28   434.7 1612.21   440.91614.919
   464.4 1622.18   484.5 1625.23   536.5 1626.68   600.1  1626.2   629.7 1627.74
   646.1    1631   654.3 1630.27   675.5 1633.31   691.3 1634.05   699.5 1637.02
   736.4 1646.97   765.2 1652.27   780.7 1656.22   812.7 1665.63   830.9    1673
#Mann= 5 ,-1,0
       0      .1       0  229.03     .06       0  313.94    .045       0
   440.9    .025       0  549.03      .1       0
Bank Sta=313.94,440.9
XS Rating Curve= 0 ,0
Exp/Cntr(USF)=0,0
Exp/Cntr=0.3,0.1

Type RM Length L Ch R = 1 ,57826   ,296.7,342.1,407.7
XS GIS Cut Line= 4
2199300.10666571683100.6310409732199424.11067369683224.635048946
2199858.12470159 683577.271446622199955.00283282683840.779963563
#Sta/Elev= 30
       0 1647.07      57 1633.73   164.1 1624.09   207.1 1623.63   271.4  1625.6
   289.5 1628.35   323.7 1628.08   385.6 1617.02   391.9 1613.91   391.9  1613.9
   404.6 1611.22   537.8 1611.23  548.061613.906   562.5  1620.6   598.1 1628.88
   639.4 1630.95   665.1  1636.5   716.1 1637.76   768.6 1645.21   785.6 1651.34
   828.2 1655.75   866.6 1674.74   883.6 1669.06   909.2 1673.21     922 1679.13
   956.1 1680.23   960.4 1681.99   973.1 1702.21   977.4 1705.63  1015.3 1712.92
#Mann= 8 ,-1,0
       0      .1       0  185.37     .06       0  335.37     .07       0
  345.37      .1       0   391.9    .045       0  548.06      .1       0
  655.37     .06       0  715.37      .1       0
Bank Sta=391.9,548.06
XS Rating Curve= 0 ,0
Exp/Cntr(USF)=0,0
Exp/Cntr=0.3,0.1

Type RM Length L Ch R = 1 ,57484   ,82.9,85.5,93.3
XS GIS Cut Line= 4
2199240.84771951683206.4456876672199308.80793395683400.029328796
2199393.24335189683746.0086023032199440.60956195683898.404234681
#Sta/Elev= 30
       0 1633.68    36.8 1629.91    45.3 1627.05    53.8 1625.49   105.2 1623.34
   130.8 1623.23   142.8 1622.22   202.4 1622.77   247.5 1621.57   286.9 1622.59
   314.8 1619.43   325.8 1616.26  333.221613.039   338.1  1611.3   346.3 1610.36
   412.2 1610.16   470.4  1610.2     474 1610.41  481.511613.039   486.3 1615.58
   502.8 1627.38   515.2 1639.26   519.3 1641.73   527.5 1643.06   552.2 1643.41
   593.9 1663.72   655.6 1688.65   673.5 1693.88   698.7 1699.29   720.9 1705.35
#Mann= 7 ,-1,0
       0      .1       0      30     .07       0     130     .06       0
  333.22    .045       0  481.51     .08       0  535.17     .05       0
   641.3      .1       0
Bank Sta=333.22,481.51
XS Rating Curve= 0 ,0
Exp/Cntr(USF)=0,0
Exp/Cntr=0.3,0.1

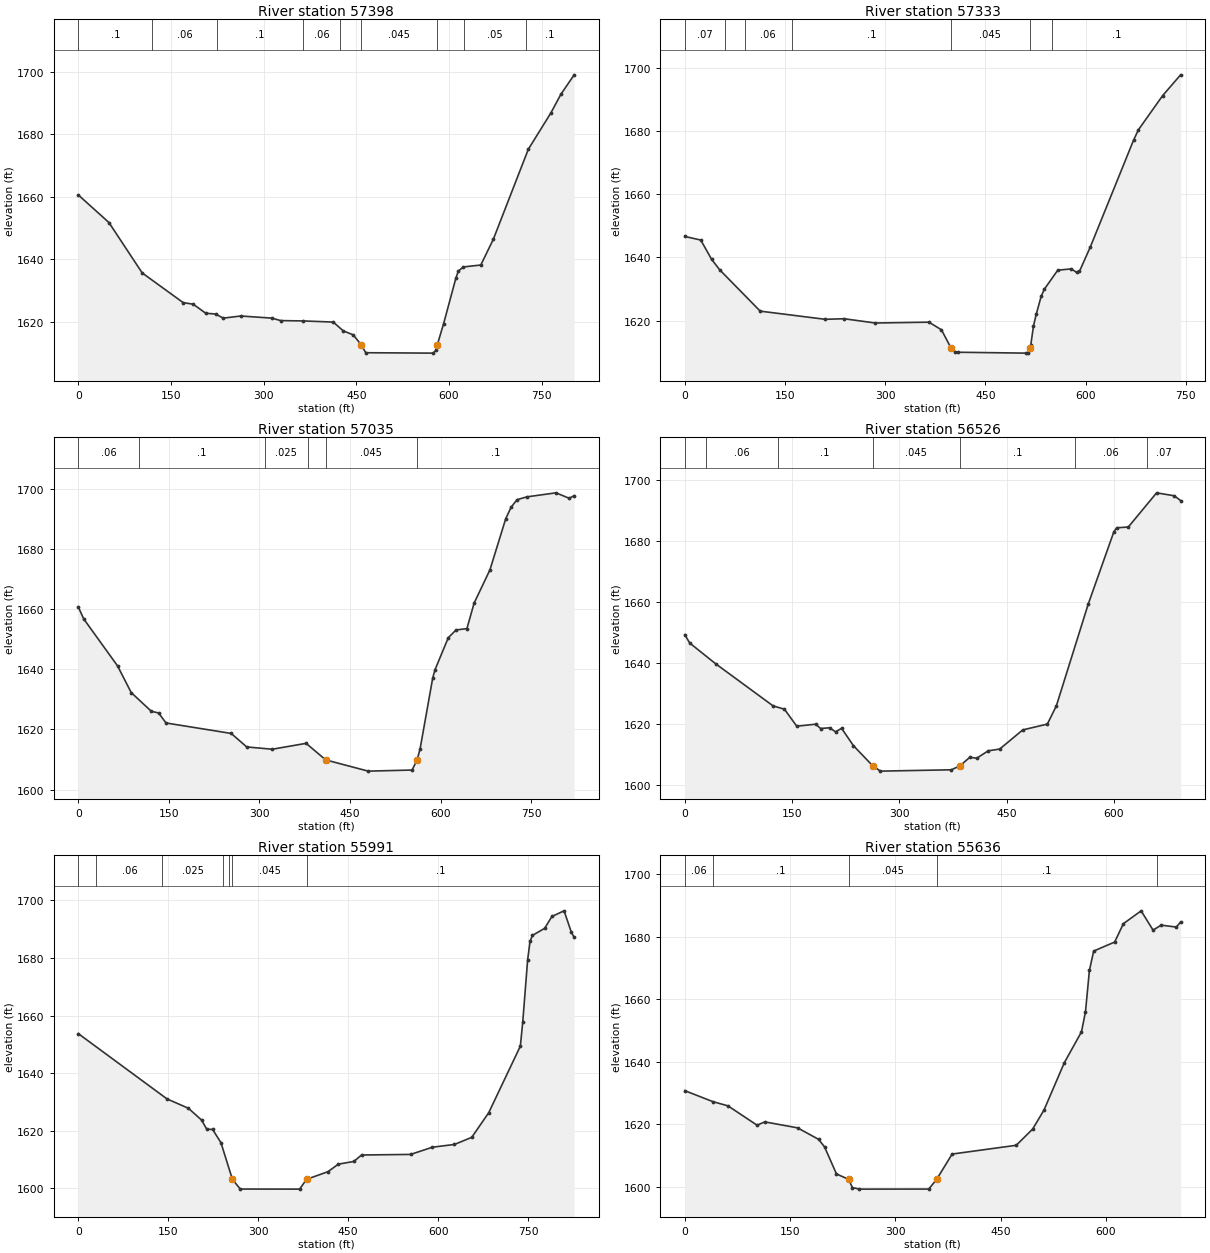
Type RM Length L Ch R = 1 ,57398   ,65.3,65.2,65.1
XS GIS Cut Line= 3
2199174.94690551683113.7726679782199216.13491426683251.752497293
 2199317.0455357683902.523035556
#Sta/Elev= 30
       0 1660.54    49.5 1651.74   103.4 1635.61   169.6 1626.14   185.9 1625.62
   206.2 1622.74   222.4 1622.47   234.5 1621.16   262.8 1621.85   313.3 1621.17
   327.5 1620.38     364 1620.27   412.6 1619.91   428.8  1617.1     445 1615.81
  457.84 1612.64   465.2 1610.11   574.5 1609.98   578.6 1610.87  580.991612.639
   591.2 1619.38   610.9 1633.84     615  1636.2   623.1 1637.53   651.4 1638.15
   671.7 1646.39   728.3 1675.15   764.8 1686.76   780.9 1692.69   802.5 1698.95
#Mann= 9 ,-1,0
       0      .1       0     120     .06       0     224      .1       0
     364     .06       0     424     .08       0  457.84    .045       0
  580.99     .06       0     624     .05       0     724      .1       0
Bank Sta=457.84,580.99
XS Rating Curve= 0 ,0
Exp/Cntr(USF)=0,0
Exp/Cntr=0.3,0.1

Type RM Length L Ch R = 1 ,57333   ,259.6,297.7,339.4
XS GIS Cut Line= 2
2199137.87769763683177.6140815422199253.20412214683910.760637306
#Sta/Elev= 30
       0 1646.63    23.9 1645.49    40.1  1639.4    52.2 1636.09   112.9 1623.02
   210.1 1620.44   238.5 1620.62     285 1619.27   365.5 1619.53   384.2 1617.12
  398.211611.482   404.5 1610.12   408.5 1610.03   510.9 1609.75   513.8 1609.75
  516.611611.482   517.9 1612.31   521.9 1618.25     526 1621.99   533.4 1627.67
   538.1 1629.93   558.3 1635.96   578.6 1636.38   586.7 1635.24   590.7 1635.56
     607 1643.29   671.7 1677.03     679 1680.33   715.4 1691.17   742.2 1697.71
#Mann= 7 ,-1,0
       0     .07       0      60      .1       0      90     .06       0
     160      .1       0  398.21    .045       0  516.61     .06       0
     550      .1       0
Bank Sta=398.21,516.61
XS Rating Curve= 0 ,0
Exp/Cntr(USF)=0,0
Exp/Cntr=0.3,0.1

Type RM Length L Ch R = 1 ,57035   ,507.8,509.5,504
XS GIS Cut Line= 4
2199026.67007401683132.3072719162199018.43247226683321.772112169
2198851.62103681683760.4244053662198785.72022281683908.701236869
#Sta/Elev= 30
       0 1660.65     8.9 1656.72    64.9 1641.11    87.6 1632.22     121 1625.98
     133 1625.45   145.2 1622.12   253.2 1618.64   278.9 1614.15   321.2 1613.39
   377.3 1615.35  409.651609.845     480 1606.11   552.8 1606.47  561.091609.848
   566.1 1613.58     587 1637.14   590.9 1639.89   612.7 1650.46   625.5 1653.03
   643.6  1653.5   655.5 1661.97   681.7 1673.01   707.9 1690.05   716.7 1693.81
   726.5 1696.34   742.9 1697.29   791.1 1698.63     813 1696.82   821.2 1697.68
#Mann= 6 ,-1,0
       0     .06       0     100      .1       0  309.64    .025       0
  379.64      .1       0  409.65    .045       0  561.09      .1       0
Bank Sta=409.65,561.09
XS Rating Curve= 0 ,0
Exp/Cntr(USF)=0,0
Exp/Cntr=0.3,0.1

Type RM Length L Ch R = 1 ,56526   ,578.2,535.1,483.7
XS GIS Cut Line= 4
2198598.70899561683011.5031602422198540.58211688 683158.75791971
2198435.95373515683511.3943173842198420.45323415683678.024703098
#Sta/Elev= 30
       0 1649.27     6.9 1646.53    43.3 1639.69   123.5 1625.87   139.4 1624.78
   156.6 1619.19   183.1 1619.86     190 1618.44   202.6 1618.68   210.9 1617.35
   219.3  1618.5   235.9 1612.79  262.551606.252   273.5 1604.43     373 1604.87
  385.321606.253   398.7    1609   408.3 1608.66   424.4 1611.11   440.4 1611.68
   472.7 1617.98   507.1 1619.89   519.7 1625.89   564.3 1659.35   600.2 1683.15
   604.3 1684.42   620.3 1684.65   659.9  1695.9   684.6 1694.93   693.5 1693.37
#Mann= 7 ,-1,0
       0      .1       0      30     .06       0     130      .1       0
  262.55    .045       0  385.32      .1       0  546.14     .06       0
  646.14     .07       0
Bank Sta=262.55,385.32
XS Rating Curve= 0 ,0
Exp/Cntr(USF)=0,0
Exp/Cntr=0.3,0.1

Type RM Length L Ch R = 1 ,55991   ,388.1,355.2,316
XS GIS Cut Line= 4
2197862.43519827682914.625029013 2197943.8128285 683065.75491373
2198114.31833947683495.8938163882198145.31934146683685.774953597
#Sta/Elev= 30
       0 1653.72   147.9 1631.07   183.5 1627.84   205.4 1623.76   214.1 1620.57
   223.9 1620.48   237.8 1615.89  256.871603.172     270 1599.81     369 1599.78
  380.521603.175   416.3 1605.84   433.5 1608.44   459.3 1609.38   472.2 1611.62
     554 1611.82   590.5 1614.33   627.1 1615.28   655.9 1617.74   684.3 1626.31
     737  1649.4     741  1657.8   749.1 1679.23   753.2 1685.81   757.2 1687.82
   777.5 1690.25   789.7 1694.39   809.9 1696.33   821.7 1689.09   826.7 1687.09
#Mann= 7 ,-1,0
       0      .1       0      30     .06       0     140    .025       0
  241.65      .1       0  251.65    .025       0  256.87    .045       0
  380.52      .1       0
Bank Sta=256.87,380.52
XS Rating Curve= 0 ,0
Exp/Cntr(USF)=0,0
Exp/Cntr=0.3,0.1

Type RM Length L Ch R = 1 ,55636   ,386.2,385.9,382.5
XS GIS Cut Line= 4
2197555.52234306683261.4742182142197625.27459755683346.726973696
2197919.78411648683590.859864393 2198063.1637507683749.739999609
#Sta/Elev= 30
       0  1630.7      40 1627.19    61.6 1625.83     103 1619.65     114 1620.71
   160.7  1618.8   190.7 1615.12   199.2  1612.7   216.2 1604.04  233.411602.334
   238.9 1599.68     249 1599.19   347.7 1599.21  359.051602.337     381 1610.41
   472.4 1613.22   495.8 1618.41     512 1624.51     541 1639.68   565.4 1649.52
   571.1 1655.97   576.7  1669.2   582.8 1675.38   612.7 1678.26   625.1 1684.13
   650.4 1688.25   667.4 1682.08     679 1683.67   700.6 1683.05   706.7 1684.68
#Mann= 5 ,-1,0
       0     .06       0      40      .1       0  233.41    .045       0
  359.05      .1       0  672.69     .06       0
Bank Sta=233.41,359.05
XS Rating Curve= 0 ,0
Exp/Cntr(USF)=0,0
Exp/Cntr=0.3,0.1

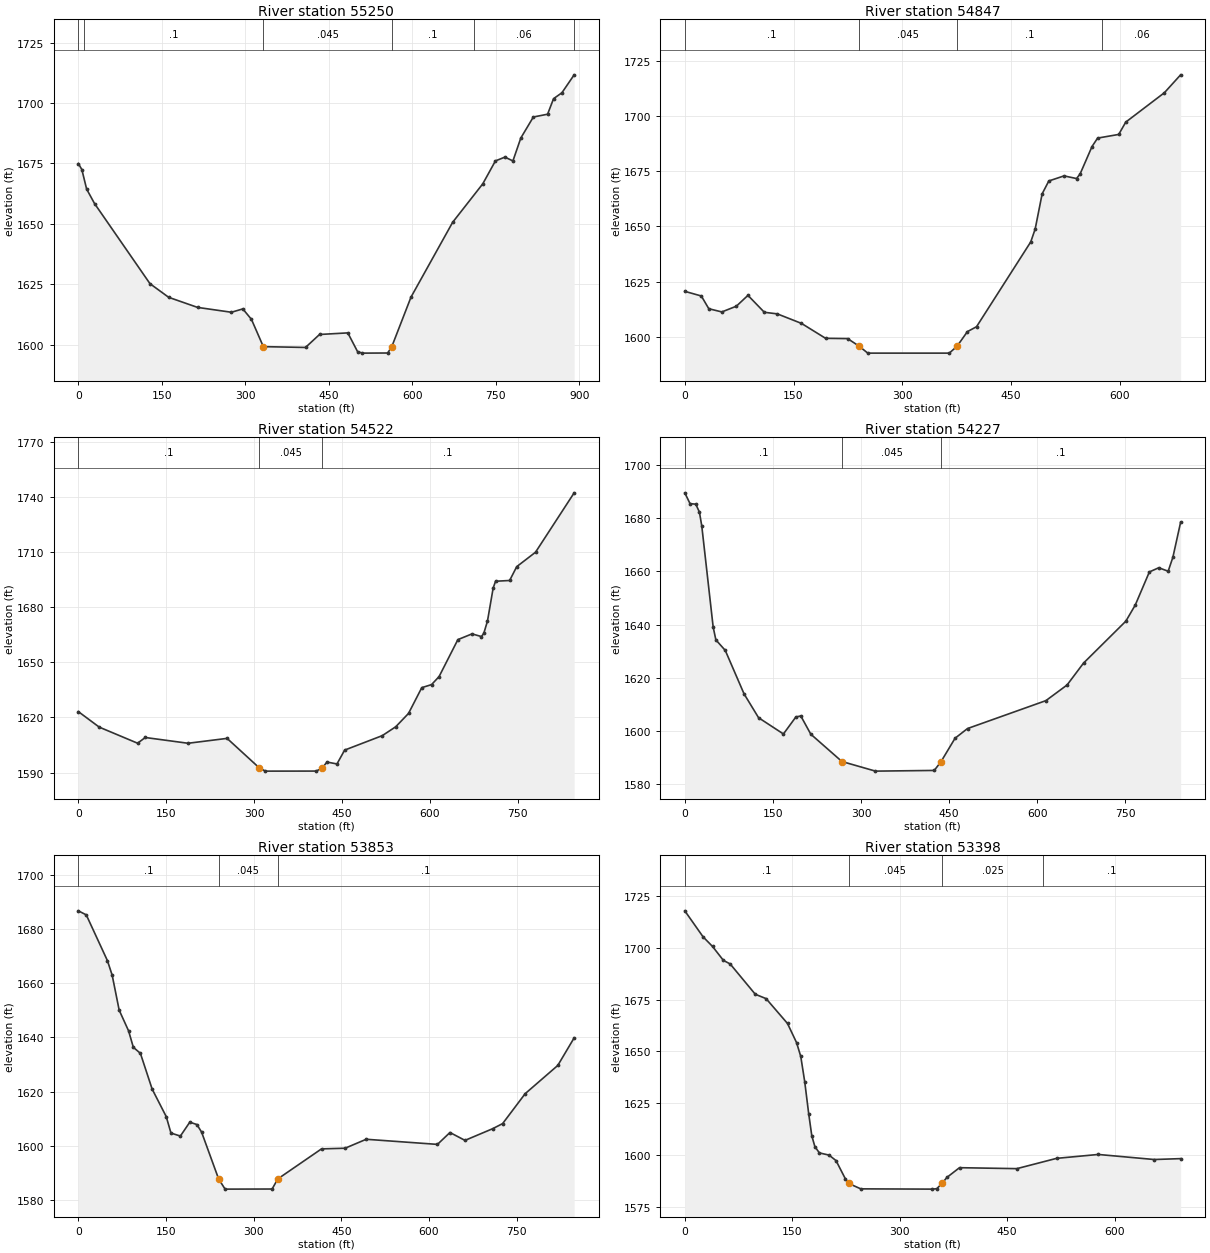
Type RM Length L Ch R = 1 ,55250   ,419.5,403,309.9
XS GIS Cut Line= 2
2197177.40962877683479.0339969682197873.09724309684034.941420884
#Sta/Elev= 30
       0 1674.94     6.3 1672.48    14.9 1664.38    29.1 1658.39   128.7 1625.21
   162.3 1619.57   214.1  1615.4   274.9 1613.39   295.4 1614.77   310.9 1610.46
  332.271599.156     408 1598.82   433.2 1604.19     484 1604.85   501.5 1597.09
   510.1 1596.47   555.6 1596.52  562.971599.156   597.5 1619.67   672.3 1650.64
   726.4 1666.56   749.1 1676.04   766.2 1677.61   780.5 1676.02   794.7 1685.51
   817.2 1694.21   842.8 1695.37   853.5  1701.8   868.5 1704.24   890.5 1711.67
#Mann= 6 ,-1,0
       0     .06       0      10      .1       0  332.27    .045       0
  562.97      .1       0     710     .06       0     890      .1       0
Bank Sta=332.27,562.97
XS Rating Curve= 0 ,0
Exp/Cntr(USF)=0,0
Exp/Cntr=0.3,0.1

Type RM Length L Ch R = 1 ,54847   ,317.2,324.2,337.8
XS GIS Cut Line= 4
2197142.78882328683986.7114425262197255.16745551684044.838321264
2197619.42922893684149.466702991 2197766.6839884 684250.21995947
#Sta/Elev= 30
       0 1620.58    22.8 1618.47    33.1 1612.71    51.1 1611.26    71.1 1613.85
    87.1 1618.76   109.7  1611.1   127.6 1610.38   160.9 1606.08   194.2 1599.32
   224.6 1599.19  240.561595.741   252.4 1592.62   364.8 1592.62  375.54 1595.74
   389.8 1602.35   402.4 1604.57   477.2 1642.96   483.3 1648.81   492.9  1664.7
   502.1 1670.52   523.1 1672.81   540.3 1671.62   545.2 1673.65   561.7 1686.11
   569.4 1689.91   598.5 1691.57   608.2 1697.14   661.5 1710.44   683.9 1718.54
#Mann= 4 ,-1,0
       0      .1       0  240.56    .045       0  375.54      .1       0
  575.51     .06       0
Bank Sta=240.56,375.54
XS Rating Curve= 0 ,0
Exp/Cntr(USF)=0,0
Exp/Cntr=0.3,0.1

Type RM Length L Ch R = 1 ,54522   ,309.9,295.6,288.6
XS GIS Cut Line= 3
2196963.40614047684247.6681147262197525.29930159684491.801005423
2197757.80681654684511.176631669
#Sta/Elev= 30
       0 1623.19    35.7 1614.73   101.1 1605.98   114.2 1609.09   187.2 1605.95
   253.8 1608.61  308.821592.534   319.2 1590.78   406.1 1590.81  416.071592.531
   424.3 1595.72   441.3 1594.69   454.4 1602.23   518.6  1610.1   541.6 1614.94
   563.4  1622.2     586 1636.23   602.7 1637.89   615.5 1642.25   647.6 1662.38
   671.7  1665.5   687.8 1664.05   691.8 1665.77   698.1 1672.48   707.8 1690.46
   711.9 1694.16   735.9 1694.57     748  1702.1   780.1 1709.97     846  1742.3
#Mann= 3 ,-1,0
       0      .1       0  308.82    .045       0  416.07      .1       0
Bank Sta=308.82,416.07
XS Rating Curve= 0 ,0
Exp/Cntr(USF)=0,0
Exp/Cntr=0.3,0.1

Type RM Length L Ch R = 1 ,54227   ,389.2,373.8,357.7
XS GIS Cut Line= 4
2196807.31361558684566.6104435462196922.13214148684571.394548792
 2197362.2698241 684724.485916662197625.39561262684719.701811414
#Sta/Elev= 30
       0 1689.53     8.9 1685.47    18.7 1685.26    24.9 1682.27    28.9 1677.06
    48.3 1639.05    52.9 1634.24    68.9 1630.28   100.9 1613.93   125.6 1604.97
   167.9 1598.86   189.1 1605.26   197.5 1605.63   214.5 1598.78  267.491588.505
   324.6 1584.89   424.7 1585.15  436.341588.505   460.1 1597.26   481.3  1600.9
   614.8  1611.4   650.8 1617.28   678.8 1625.51   750.9 1641.29   766.9 1647.35
   790.9 1659.79   806.9 1661.36   822.9 1660.05   830.9 1665.28   844.1 1678.48
#Mann= 3 ,-1,0
       0      .1       0  267.49    .045       0  436.34      .1       0
Bank Sta=267.49,436.34
XS Rating Curve= 0 ,0
Exp/Cntr(USF)=0,0
Exp/Cntr=0.3,0.1

Type RM Length L Ch R = 1 ,53853   ,510.5,455.1,397.6
XS GIS Cut Line= 3
2196754.68845787  684968.47528422197347.91750836685035.452757642
2197582.33866541684944.554757971
#Sta/Elev= 30
       0 1686.79    13.6 1685.29    49.8 1668.37    57.9 1663.02    69.9 1650.09
      86 1642.43    94.1 1636.37   106.2 1634.14   126.3 1620.93   150.4 1610.77
   158.5 1604.69   174.6 1603.57   190.7  1608.7   202.8 1607.84   210.8 1605.09
  240.041587.741   251.1 1583.97   331.6 1584.01  341.271587.737   416.1 1598.84
   456.4 1599.08   492.6 1602.39   614.5  1600.5   635.9 1604.89   661.6 1601.98
   708.8 1606.28     726 1608.18   764.6 1619.24   820.4 1629.67   848.4 1639.86
#Mann= 3 ,-1,0
       0      .1       0  240.04    .045       0  341.27      .1       0
Bank Sta=240.04,341.27
XS Rating Curve= 0 ,0
Exp/Cntr(USF)=0,0
Exp/Cntr=0.3,0.1

Type RM Length L Ch R = 1 ,53398   ,729,689.9,656
XS GIS Cut Line= 2
2196917.34803623685614.3294923942197443.59961328685164.623599281
#Sta/Elev= 30
       0 1717.82    25.5 1705.28    38.7 1700.64    53.9 1693.91    63.3 1692.21
    98.4 1677.58   113.5 1675.47   143.4 1663.48     156 1654.27   161.9 1647.58
   167.4 1635.43     173 1619.87   177.3 1609.31   181.6 1604.09   187.9 1601.06
   201.4    1600   211.1 1597.35   224.1 1588.61   228.81586.325   245.7 1583.72
   345.7 1583.59   351.8 1583.81  359.011586.327     366 1589.26   383.5 1593.93
   463.6 1593.47     519 1598.43   577.2 1600.31   655.4 1597.87   692.2  1598.3
#Mann= 4 ,-1,0
       0      .1       0   228.8    .045       0  359.01    .025       0
     500      .1       0
Bank Sta=228.8,359.01
XS Rating Curve= 0 ,0
Exp/Cntr(USF)=0,0
Exp/Cntr=0.3,0.1

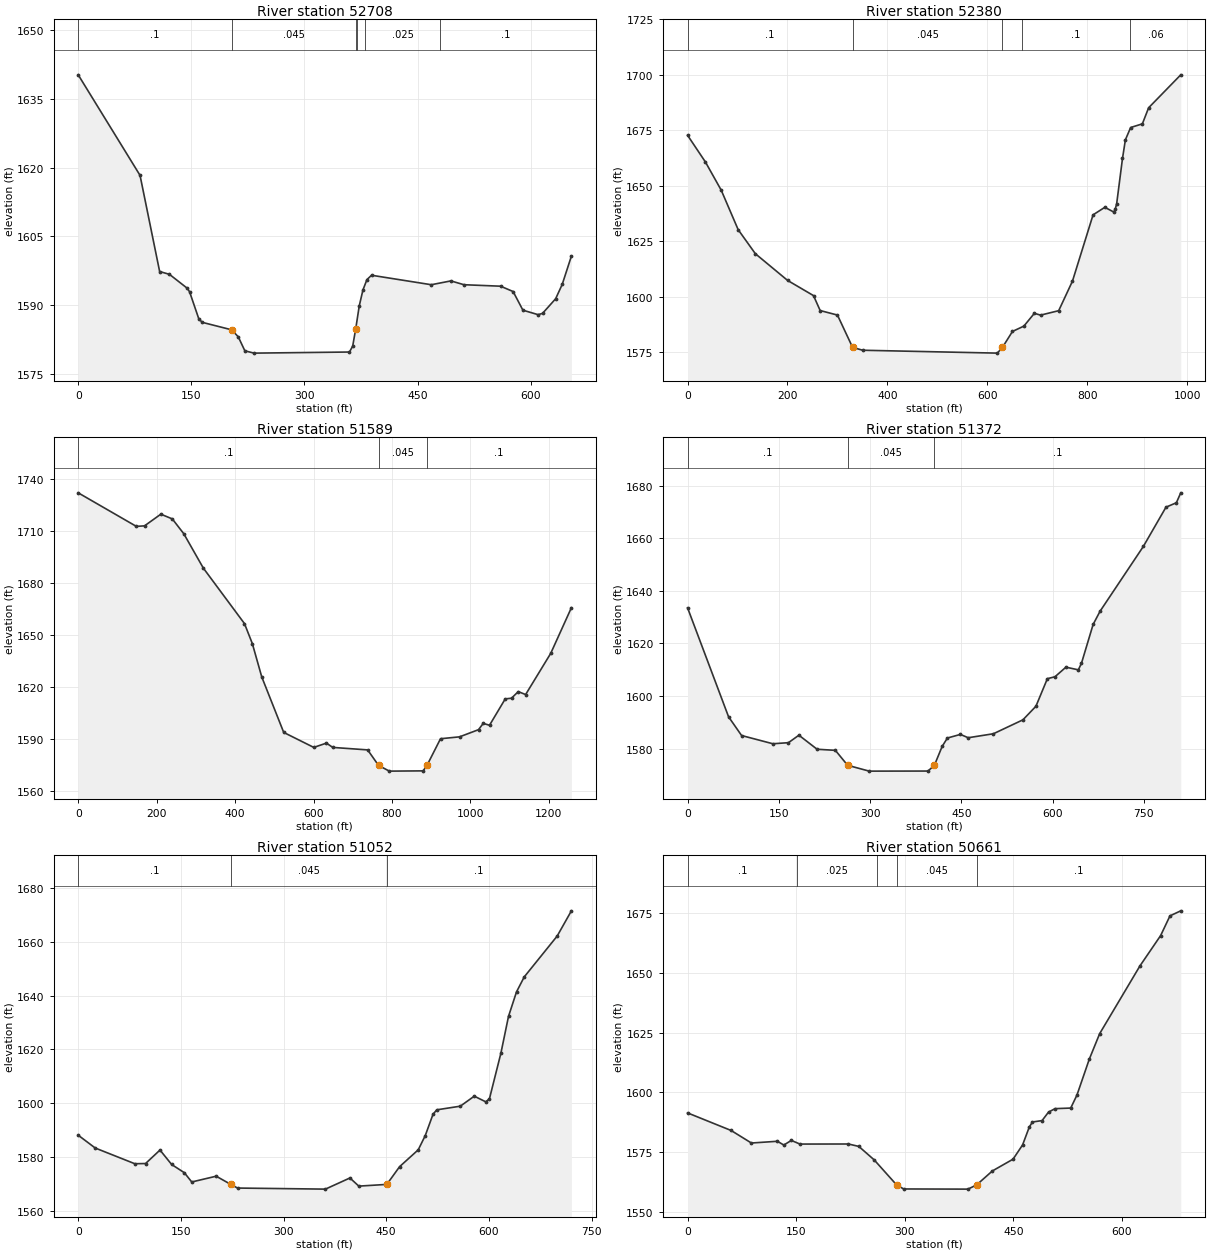
Type RM Length L Ch R = 1 ,52708   ,309.7,327.7,318
XS GIS Cut Line= 2
2197626.28903561686024.7340340382197879.84661364685421.936773057
#Sta/Elev= 30
       0 1640.16      82 1618.29     108 1597.37     121 1596.76   144.7 1593.72
   147.7 1592.96   159.9 1587.09   164.4 1586.32   203.5 1584.69   212.2 1583.18
     221 1580.12   233.2 1579.62   359.7 1579.86     364 1581.15  368.041584.935
   372.7 1589.91   377.6 1593.37   382.9 1595.62     389 1596.56   468.2  1594.5
   494.2 1595.33   511.6  1594.5   560.1 1594.18   576.7 1593.02   589.7 1588.96
   609.8 1587.99   615.7 1588.26   633.1 1591.45   641.8 1594.56     654 1600.72
#Mann= 6 ,-1,0
       0      .1       0   203.5    .045       0  368.04    .025       0
     370      .1       0     380    .025       0     480      .1       0
Bank Sta=203.5,368.04
XS Rating Curve= 0 ,0
Exp/Cntr(USF)=0,0
Exp/Cntr=0.3,0.1

Type RM Length L Ch R = 1 ,52380   ,543,791.1,883.4
XS GIS Cut Line= 4
2197797.62340148 686269.751911082197893.30550639686183.638016654
2198146.86308443685566.4884399352198247.32929459685403.828861575
#Sta/Elev= 30
       0 1672.73    35.7 1660.72    67.4 1647.99   101.3 1630.21   135.7 1619.38
   200.2 1607.35   252.1  1600.5   265.4 1593.77     300 1591.74  330.231577.207
   350.4 1575.89     620 1574.59   630.31577.205   650.3 1584.36   673.1 1586.76
   694.1 1592.52   706.5 1591.71   742.8 1593.71   770.4 1607.05   811.6 1636.89
   835.1 1640.28   853.1 1638.15     856 1639.41   858.9    1642   870.5  1662.3
   876.3 1670.69   886.8 1676.23   910.3 1677.89   922.8 1685.13   987.1 1699.97
#Mann= 5 ,-1,0
       0      .1       0  330.23    .045       0   630.3    .025       0
  668.73      .1       0  885.93     .06       0
Bank Sta=330.23,630.3
XS Rating Curve= 0 ,0
Exp/Cntr(USF)=0,0
Exp/Cntr=0.3,0.1

Type RM Length L Ch R = 1 ,51589   ,204,217.2,235
XS GIS Cut Line= 5
2197505.79298148686298.4565425552197835.89624344686394.138647473
2198032.04455853686398.9227527192198505.67097787686465.900226161
2198744.87624016686470.684331407
#Sta/Elev= 30
       0 1732.15   148.2  1712.8   169.1 1713.09   210.7 1719.83   239.9 1717.11
   269.3 1708.52     319 1688.73     424 1656.68     444 1645.16     468 1625.93
     524 1593.91   600.6 1585.27   632.9 1587.74   649.1 1585.26     738 1583.83
  765.85 1574.86   793.3 1571.58   879.4 1571.73  889.251574.857   923.8 1590.27
   972.3 1591.36  1020.7  1595.5  1032.7 1599.13  1048.7 1598.04  1088.8 1613.25
  1104.8 1613.66    1122 1617.45  1140.8 1615.77  1204.8 1639.53  1257.5 1665.87
#Mann= 3 ,-1,0
       0      .1       0  765.85    .045       0  889.25      .1       0
Bank Sta=765.85,889.25
XS Rating Curve= 0 ,0
Exp/Cntr(USF)=0,0
Exp/Cntr=0.3,0.1

Type RM Length L Ch R = 1 ,51372   ,272.8,319.7,382.3
XS GIS Cut Line= 3
2197921.19165418686522.2561137312198463.70918906686728.929460353
2198644.54836735686871.017386155
#Sta/Elev= 30
       0 1633.56    67.4 1592.14    88.8 1585.03   140.2  1581.9   165.8 1582.31
     183 1585.15   212.9 1579.81   242.9  1579.4  263.071573.712   298.5  1571.5
   395.1 1571.53  405.631573.712   418.4 1580.89     427 1584.08   448.4 1585.45
   461.2 1584.19   502.6  1585.7   551.1 1590.99   572.5 1596.15   591.3 1606.63
   603.8 1607.36   621.8    1611   642.2 1609.99   647.3 1612.45   666.5 1627.24
   677.9 1632.26     749 1656.87   786.2 1671.79   803.3 1673.48   810.5 1677.25
#Mann= 3 ,-1,0
       0      .1       0  263.07    .045       0  405.63      .1       0
Bank Sta=263.07,405.63
XS Rating Curve= 0 ,0
Exp/Cntr(USF)=0,0
Exp/Cntr=0.3,0.1

Type RM Length L Ch R = 1 ,51052   ,371.7,391.6,431.6
XS GIS Cut Line= 3
2197877.68784409686686.8240464922198250.66814555687094.127688584
2198367.36750368687215.403492128
#Sta/Elev= 30
       0 1588.07    24.9  1583.3    82.7 1577.46    98.4 1577.53   119.5 1582.55
   136.5 1577.19   155.1 1574.11   165.9 1570.67   201.6 1572.82  222.971569.768
   232.8 1568.41   361.2 1568.01     397 1572.16     410 1569.13  450.921569.768
   469.6 1576.37   496.8 1582.63   507.1 1587.94   518.4 1595.85   523.9 1597.51
   558.3 1598.87   578.7 1602.59   595.4  1600.5   600.8 1601.57   617.6 1618.58
   628.7 1632.27   640.4 1641.38   651.7 1646.96   699.8 1662.15   720.6 1671.54
#Mann= 3 ,-1,0
       0      .1       0  222.97    .045       0  450.92      .1       0
Bank Sta=222.97,450.92
XS Rating Curve= 0 ,0
Exp/Cntr(USF)=0,0
Exp/Cntr=0.3,0.1

Type RM Length L Ch R = 1 ,50661   ,400.4,397.2,396.9
XS GIS Cut Line= 4
2197612.25400991686835.5585225372197660.30668679686924.799208164
2197843.36450346687295.4912869212197902.85829388687451.090431091
#Sta/Elev= 30
       0 1591.44    60.2 1584.07    88.2 1578.82   124.1 1579.55     133 1577.98
   143.4 1579.91   155.3 1578.38   222.2 1578.41   236.6  1577.4   257.9 1571.74
  288.881561.241   298.6 1559.57   387.3  1559.5  399.311561.242   421.1 1567.11
   449.7 1572.05   462.9 1578.03   472.1 1585.49   476.5 1587.63   489.8 1588.22
   498.7 1591.77   507.7 1593.22   529.4 1593.47     538 1598.92   555.1 1614.01
   569.4 1624.66   625.1 1653.07   653.6 1665.74   666.5    1674   681.4 1676.11
#Mann= 5 ,-1,0
       0      .1       0  151.36    .025       0  261.36      .1       0
  288.88    .045       0  399.31      .1       0
Bank Sta=288.88,399.31
XS Rating Curve= 0 ,0
Exp/Cntr(USF)=0,0
Exp/Cntr=0.3,0.1