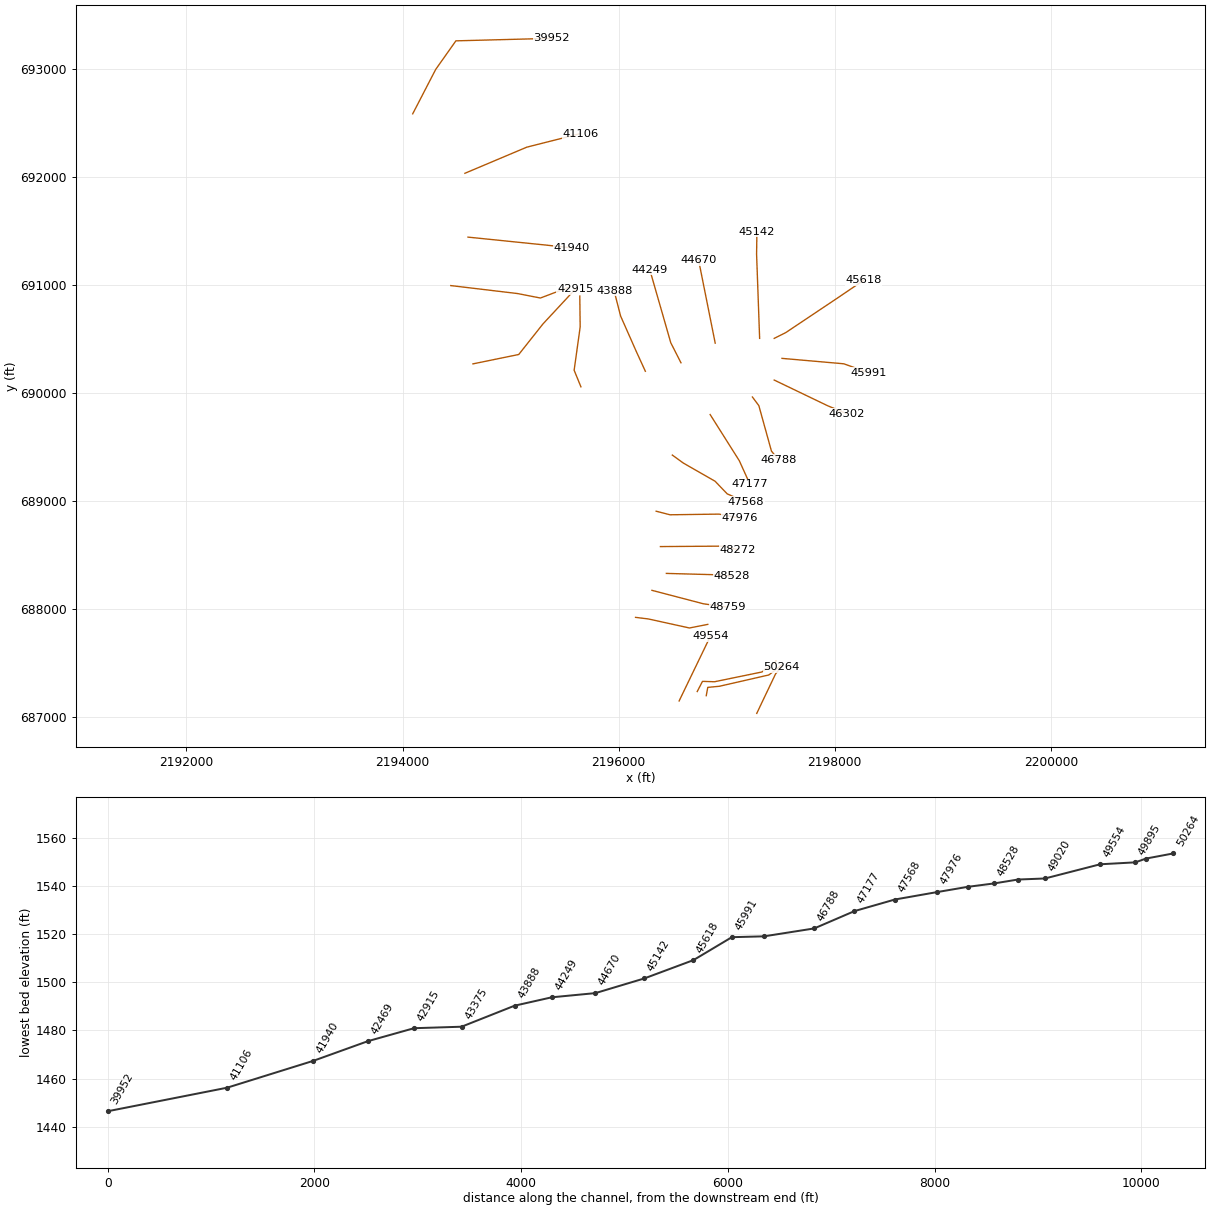
HEC-RAS study BUCKHANR_U.prj: BUCKHANR_U

--- BUCKHANR_U.g01 (geometry) --- (continued)

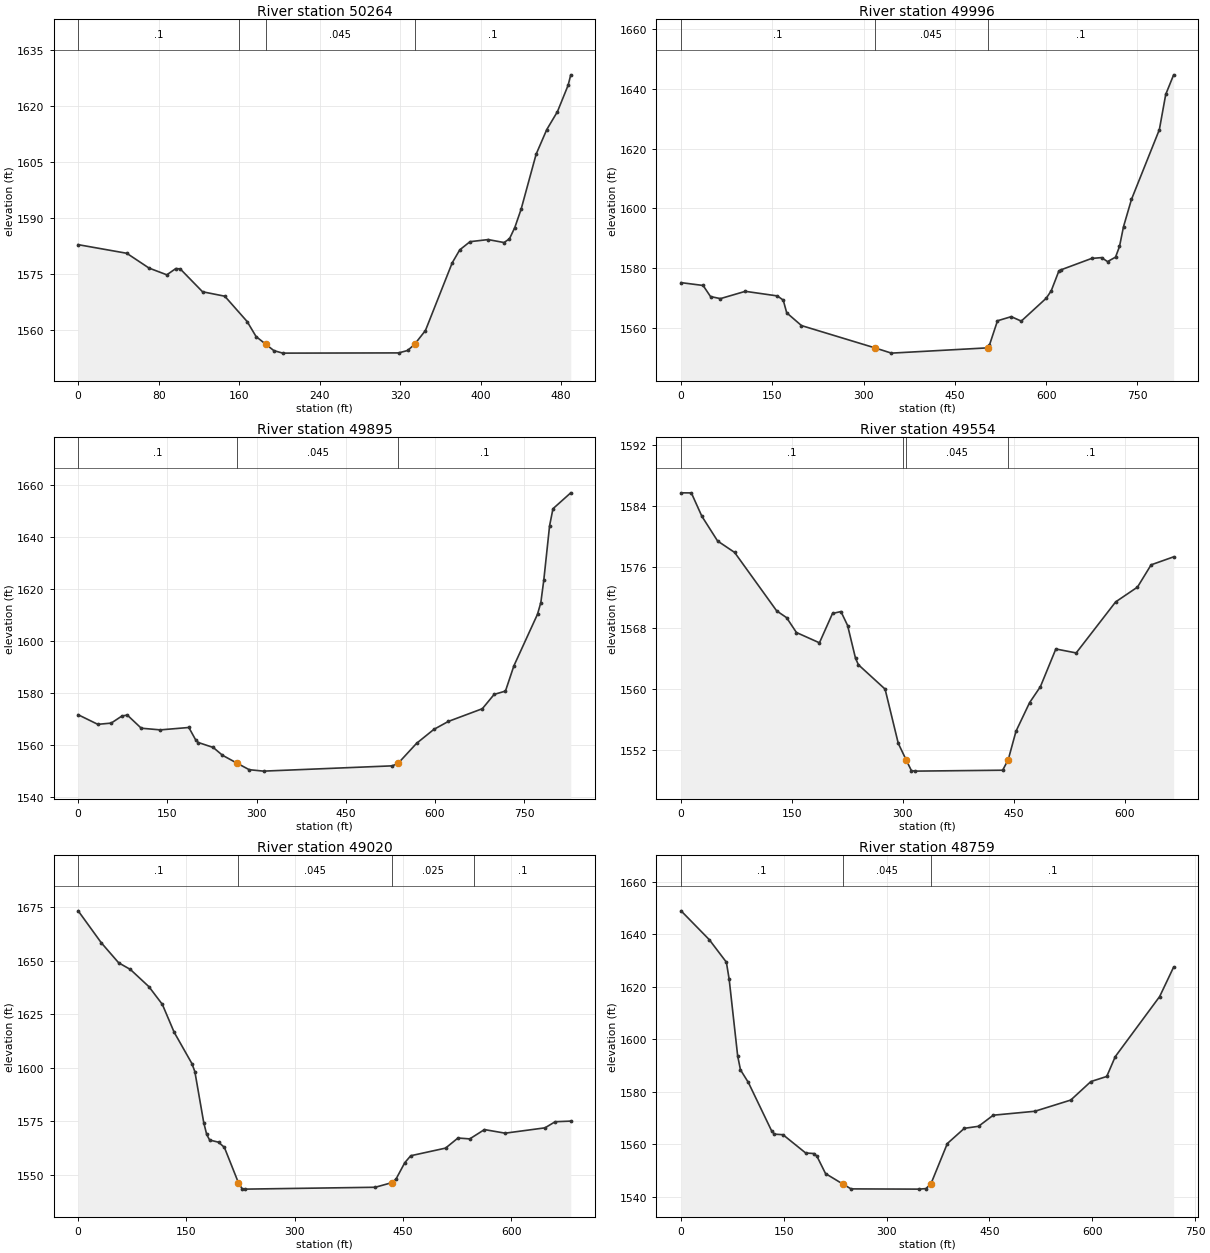
Type RM Length L Ch R = 1 ,50264   ,338.6,267.1,154
XS GIS Cut Line= 3
2197278.39448923687029.5961227412197452.77512545687395.795458787
2197507.80723411687459.166968593
#Sta/Elev= 30
       0 1582.78    48.3 1580.47    70.4 1576.51    88.1  1574.7      97 1576.37
   101.4 1576.29   123.6 1570.16   145.7 1568.97   167.9 1562.19   176.8 1558.16
  186.511556.085   194.5 1554.39   203.3 1553.72   318.5 1553.78   327.4 1554.43
  334.331556.086   345.1 1559.78   371.7 1577.91   379.2 1581.39   389.4 1583.58
   407.4 1584.14   423.2 1583.35   428.6 1584.35   433.9 1587.37   440.2  1592.3
   455.1 1607.02   465.7 1613.63   476.3 1618.43   486.9  1625.5   489.5 1628.28
#Mann= 4 ,-1,0
       0      .1       0     160    .025       0  186.51    .045       0
  334.33      .1       0
Bank Sta=186.51,334.33
XS Rating Curve= 0 ,0
Exp/Cntr(USF)=0,0
Exp/Cntr=0.3,0.1

Type RM Length L Ch R = 1 ,49996   ,122.8,101.1,71.8
XS GIS Cut Line= 5
2196811.05438419687193.5139207812196825.00483508687270.241400714
2196933.12082953687280.7042388872197389.99809641687385.332620614
2197512.06454176687479.498164169
#Sta/Elev= 30
       0 1575.16    36.2 1574.21    48.4  1570.5    64.7 1569.81   105.6 1572.25
   158.3 1570.71   167.9 1569.31   173.6 1565.06   197.9 1560.78  318.481553.325
   345.7 1551.56   503.61553.324   506.7  1554.2     520 1562.39   542.6 1563.77
   559.1 1562.28   600.1 1569.94   608.3 1572.42   620.6 1578.91   623.6 1579.39
   674.7 1583.26     691 1583.54   700.9  1582.2     714  1583.7   720.5 1587.26
   727.1 1593.89   740.2 1603.03     786 1626.37   796.5 1638.19   809.5 1644.73
#Mann= 3 ,-1,0
       0      .1       0  318.48    .045       0   503.6      .1       0
Bank Sta=318.48,503.6
XS Rating Curve= 0 ,0
Exp/Cntr(USF)=0,0
Exp/Cntr=0.3,0.1

Type RM Length L Ch R = 1 ,49895   ,242.6,341.4,485.9
XS GIS Cut Line= 5
 2196727.3516788687231.8776607472196776.17825694687326.043204302
2196887.78186412687322.5555915782197327.22106737687413.233522408
2197456.26273817687510.886678687
#Sta/Elev= 30
       0 1571.64      33 1567.96    55.5 1568.43    73.6 1571.15    82.6 1571.52
   106.1 1566.47   138.1 1565.83   186.1 1566.75   198.1 1561.77   202.1 1560.98
   227.1 1559.08   242.6  1556.1  266.621553.116   287.6 1550.55   311.7    1550
   528.4 1552.03  538.521553.115     569 1560.66     598    1566   622.5 1569.08
   679.6 1573.95   699.5 1579.45   718.5 1580.72   732.7 1590.42   772.4 1610.22
     778 1614.71     783 1623.36   792.7 1644.16   798.4 1650.71   828.3 1656.81
#Mann= 3 ,-1,0
       0      .1       0  266.62    .045       0  538.52      .1       0
Bank Sta=266.62,538.52
XS Rating Curve= 0 ,0
Exp/Cntr(USF)=0,0
Exp/Cntr=0.3,0.1

Type RM Length L Ch R = 1 ,49554   ,638.4,533.8,366.6
XS GIS Cut Line= 2
2196559.94626804687144.6873426412196849.41812415687744.556731212
#Sta/Elev= 30
       0 1585.71    13.9  1585.7    28.1 1582.64    49.4 1579.39    72.4 1577.89
   129.3 1570.22   142.7 1569.33     156 1567.38   187.1 1566.03   204.8 1569.88
   216.2 1570.13   225.2  1568.3   235.9    1564   239.8 1563.15   275.9 1559.95
   293.7 1552.84  304.15 1550.71   311.4 1549.27   315.9 1549.19   434.9 1549.31
  442.461550.709   452.9 1554.42   471.3 1558.18   485.9 1560.27   506.8 1565.22
   534.3  1564.7   587.7  1571.4   617.2 1573.34   635.6 1576.26   666.1 1577.31
#Mann= 4 ,-1,0
       0      .1       0     300    .025       0  304.15    .045       0
  442.46      .1       0
Bank Sta=304.15,442.46
XS Rating Curve= 0 ,0
Exp/Cntr(USF)=0,0
Exp/Cntr=0.3,0.1

Type RM Length L Ch R = 1 ,49020   ,279.8,261.4,253.1
XS GIS Cut Line= 4
2196156.47139269687918.9218891572196276.57562621687903.908859967
2196655.23758466687820.5031422472196825.38524881687853.865429335
#Sta/Elev= 30
       0  1673.3      32 1658.38    56.1 1649.01    72.3 1645.91      98 1637.86
   116.6 1629.58   132.9  1616.6   157.5 1601.95   161.6 1598.19   173.9 1574.37
     178 1568.83   182.1 1566.21   194.4 1565.21   202.5 1562.78  221.951546.264
     227 1543.49   231.2 1543.28   411.4 1544.15  434.041546.267   440.1 1547.92
   452.4 1555.66   460.6 1558.88   508.8 1562.44     526 1567.16   542.3 1566.75
   562.7  1571.1   591.3 1569.42   646.5 1571.91   660.6 1574.77   682.2 1575.06
#Mann= 4 ,-1,0
       0      .1       0  221.95    .045       0  434.04    .025       0
  548.78      .1       0
Bank Sta=221.95,434.04
XS Rating Curve= 0 ,0
Exp/Cntr(USF)=0,0
Exp/Cntr=0.3,0.1

Type RM Length L Ch R = 1 ,48759   ,213.3,230.8,253.7
XS GIS Cut Line= 3
2196308.26979894688169.1390423182196787.01861866688044.030465738
 2197008.8778278688014.004407358
#Sta/Elev= 30
       0 1648.85    41.2 1637.85    66.1 1629.29    70.2 1622.77    82.6 1593.54
    86.7 1588.27    98.2 1583.46   132.2 1564.99   136.3 1563.78   148.7 1563.57
   181.8 1556.61   194.2 1556.39   198.3 1555.34   210.8 1548.76  235.571544.853
     248 1542.93   347.3 1542.84   357.2 1543.04  364.551544.851   388.5 1560.21
   413.3    1566     434 1566.77   455.5    1571   516.2  1572.5   568.6 1576.77
   597.9 1583.81   621.1 1585.76   633.5 1593.31   698.3 1616.21   718.7 1627.43
#Mann= 3 ,-1,0
       0      .1       0  235.57    .045       0  364.55      .1       0
Bank Sta=235.57,364.55
XS Rating Curve= 0 ,0
Exp/Cntr(USF)=0,0
Exp/Cntr=0.3,0.1

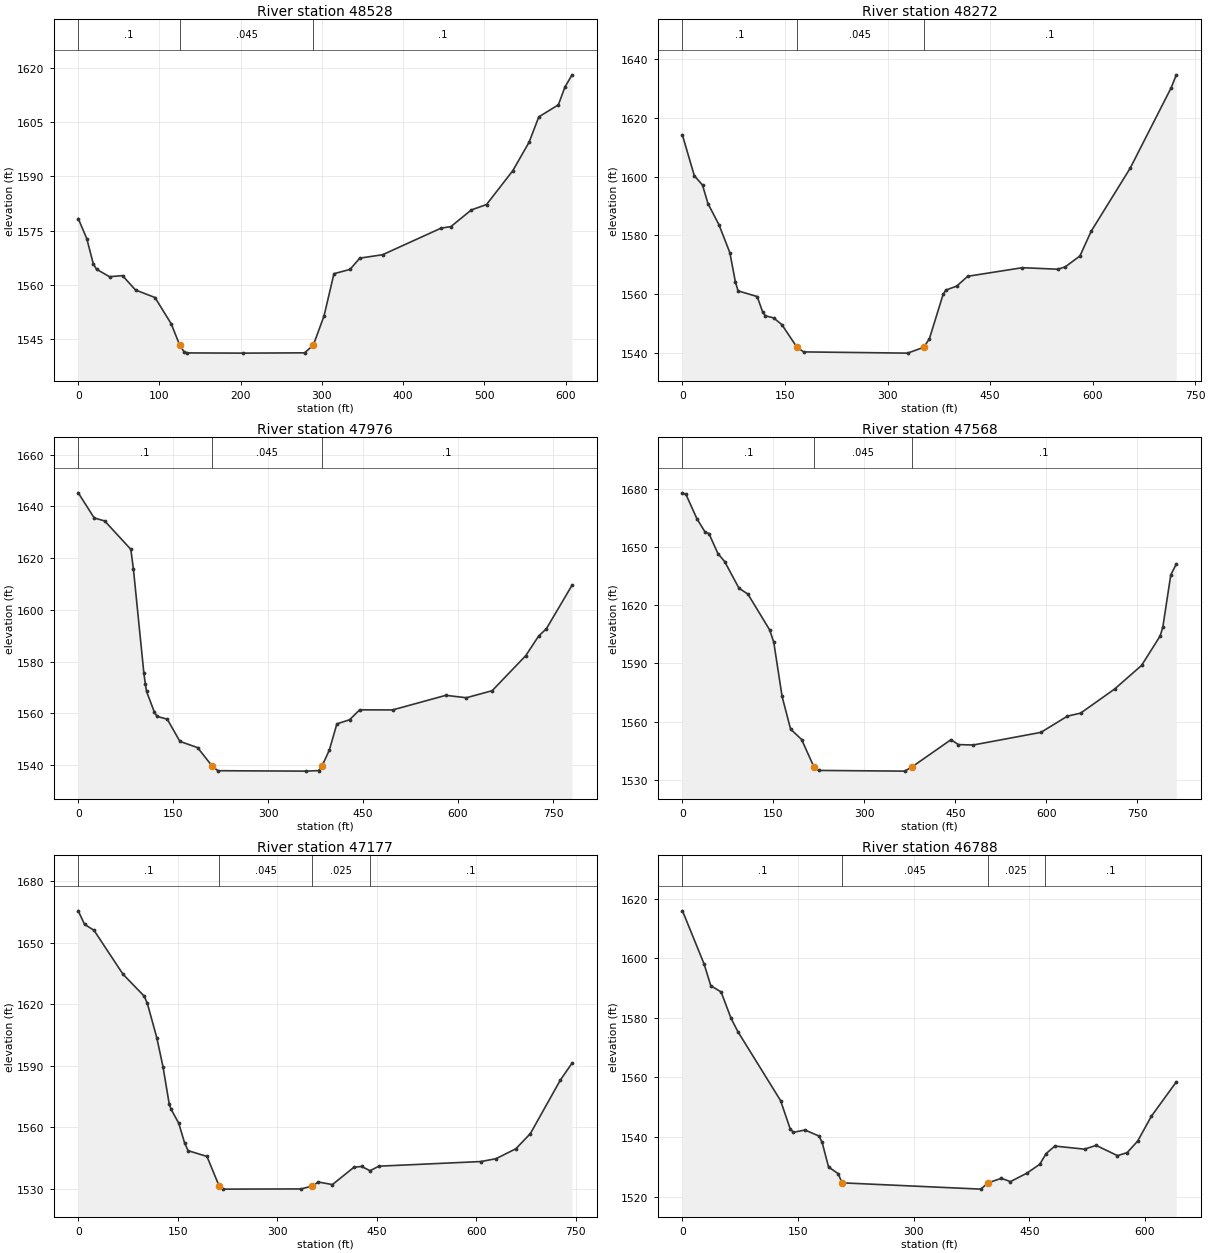
Type RM Length L Ch R = 1 ,48528   ,253.4,256.4,259.5
XS GIS Cut Line= 3
 2196441.7189473688325.9417916332196873.76056509688314.264991152
 2197048.9125723688300.920076317
#Sta/Elev= 30
       0 1578.36    10.5 1572.83    18.5 1565.91    22.5 1564.38    38.5 1562.31
    54.5 1562.62    70.5 1558.65    94.5 1556.57   114.5  1549.3  124.931543.421
   130.5 1541.52   134.5 1541.28   202.5 1541.22   278.6  1541.3  289.39 1543.42
   302.6 1551.49   314.8 1563.14   334.6 1564.33   346.6 1567.44   374.6 1568.37
   446.7 1575.72   458.7 1576.13   483.9 1580.74   502.6 1582.23   534.9 1591.55
     555 1599.43     567 1606.43   591.1 1609.76   599.1 1614.64   607.9 1618.03
#Mann= 3 ,-1,0
       0      .1       0  124.93    .045       0  289.39      .1       0
Bank Sta=124.93,289.39
XS Rating Curve= 0 ,0
Exp/Cntr(USF)=0,0
Exp/Cntr=0.3,0.1

Type RM Length L Ch R = 1 ,48272   ,294.5,295.7,295.9
XS GIS Cut Line= 3
2196386.87386179688574.4807236872196961.44658387688578.599524562
 2197105.6046145688545.649117561
#Sta/Elev= 30
       0 1614.07    17.3 1600.29    29.3 1597.09    37.3 1590.77    53.3 1583.59
    69.3 1574.06    77.3  1564.2    81.3 1561.02   109.3 1559.08   117.3 1553.83
   121.3 1552.51   133.3 1551.81   145.3 1549.53  167.56 1541.78   177.3 1540.21
   329.3 1539.79  353.06 1541.78   361.3 1544.73   381.3  1559.8   385.3 1561.28
   401.3 1562.65   417.3 1565.99   497.3 1568.92   549.3  1568.4     560  1569.2
   581.5 1572.91   597.9 1581.33   654.9  1602.8     715 1630.28   722.5 1634.68
#Mann= 3 ,-1,0
       0      .1       0  167.56    .045       0  353.06      .1       0
Bank Sta=167.56,353.06
XS Rating Curve= 0 ,0
Exp/Cntr(USF)=0,0
Exp/Cntr=0.3,0.1

Type RM Length L Ch R = 1 ,47976   ,457.2,408,357.4
XS GIS Cut Line= 4
2196347.74525348688901.9253932562196475.42808061688868.974986256
2196930.55557731688875.1531875682197120.02041756688838.083979693
#Sta/Elev= 30
       0 1645.23    25.2 1635.52    41.8 1634.35    83.1 1623.37    87.2 1615.71
   103.7 1575.47     106 1571.35   107.9 1568.45   120.2 1560.49   124.4  1558.8
   140.7 1557.69   160.6 1549.11   188.6  1546.7   211.61539.562   220.6 1537.77
   360.6 1537.61   379.8 1537.82  385.091539.563   396.6  1545.7   408.6 1555.89
   428.6 1557.47   444.6 1561.31   496.6 1561.28   580.7 1566.92   613.1 1565.99
   653.9 1568.71   706.9 1582.25   727.3 1589.84   739.5 1592.66   780.1  1609.5
#Mann= 3 ,-1,0
       0      .1       0   211.6    .045       0  385.09      .1       0
Bank Sta=211.6,385.09
XS Rating Curve= 0 ,0
Exp/Cntr(USF)=0,0
Exp/Cntr=0.3,0.1

Type RM Length L Ch R = 1 ,47568   ,430.2,390.7,348.2
XS GIS Cut Line= 5
2196496.91690178 689422.028789062196597.59870095689348.805662392
2196892.77943033689179.4771819722197004.90234304689062.777823845
2197176.51904617688987.266474468
#Sta/Elev= 30
       0 1677.83     5.8 1676.97    23.8 1664.49    37.3 1657.61    43.6 1656.86
    58.4 1646.58    69.5 1642.45    93.1 1628.74   107.9 1625.66   143.7 1607.25
   150.5 1600.88   164.2 1572.97   178.2 1556.18   196.4 1550.79  216.851536.586
   224.3 1534.88   366.4 1534.52  377.881536.588   442.6 1550.71   454.9 1548.19
   479.1 1547.97   590.9 1554.48   634.6 1562.84   656.4  1564.4   712.3 1576.77
   756.9 1588.98   787.5 1604.12   791.9 1608.73     805 1635.57   814.1 1641.23
#Mann= 3 ,-1,0
       0      .1       0  216.85    .045       0  377.88      .1       0
Bank Sta=216.85,377.88
XS Rating Curve= 0 ,0
Exp/Cntr(USF)=0,0
Exp/Cntr=0.3,0.1

Type RM Length L Ch R = 1 ,47177   ,411.2,389.7,362
XS GIS Cut Line= 3
2196847.01497616689797.2973132352197117.02525575689369.399666768
2197215.41883221689152.018509471
#Sta/Elev= 30
       0 1665.56     9.6 1658.94    23.8 1656.05    67.6 1634.57    99.5  1623.9
   104.2 1620.39   118.4  1603.7   127.8 1589.47   137.2 1571.26   140.1 1568.66
   151.5 1561.89   160.4 1552.26   165.7 1548.47   194.1 1545.67  212.451531.235
   217.7  1529.7     336  1529.8  353.161531.231     362 1533.17   383.3 1531.92
   415.6 1540.36   427.2 1540.77     440 1538.69   453.3  1540.9   607.2 1543.17
     630 1544.56   659.9  1549.4   681.8 1556.84     727 1582.96   744.6 1591.22
#Mann= 4 ,-1,0
       0      .1       0  212.45    .045       0  353.16    .025       0
     440      .1       0
Bank Sta=212.45,353.16
XS Rating Curve= 0 ,0
Exp/Cntr(USF)=0,0
Exp/Cntr=0.3,0.1

Type RM Length L Ch R = 1 ,46788   ,409.1,485.6,564.2
XS GIS Cut Line= 4
 2197238.3010593 689959.761125532197297.79484971689879.673330737
2197414.49420784689458.6403523952197480.85266638689378.552557601
#Sta/Elev= 30
       0 1615.89    28.1    1598    36.7 1590.77    50.1 1588.66      63 1579.83
    71.8 1575.37   127.3 1552.18   139.7 1542.74   143.9 1541.55     159 1542.32
   177.1  1540.3   181.2 1538.18   189.5 1529.91     202 1527.67  207.011524.593
   387.1 1522.48  396.481524.596   413.7 1526.11   425.5    1525   446.9 1527.85
   463.5 1530.81   471.8 1534.42   483.1 1536.93   521.6  1535.9   536.7 1537.16
   564.4 1533.72   576.9 1534.73   590.5 1538.58   608.3 1546.92   640.7 1558.47
#Mann= 4 ,-1,0
       0      .1       0  207.01    .045       0  396.48    .025       0
  469.77      .1       0
Bank Sta=207.01,396.48
XS Rating Curve= 0 ,0
Exp/Cntr(USF)=0,0
Exp/Cntr=0.3,0.1

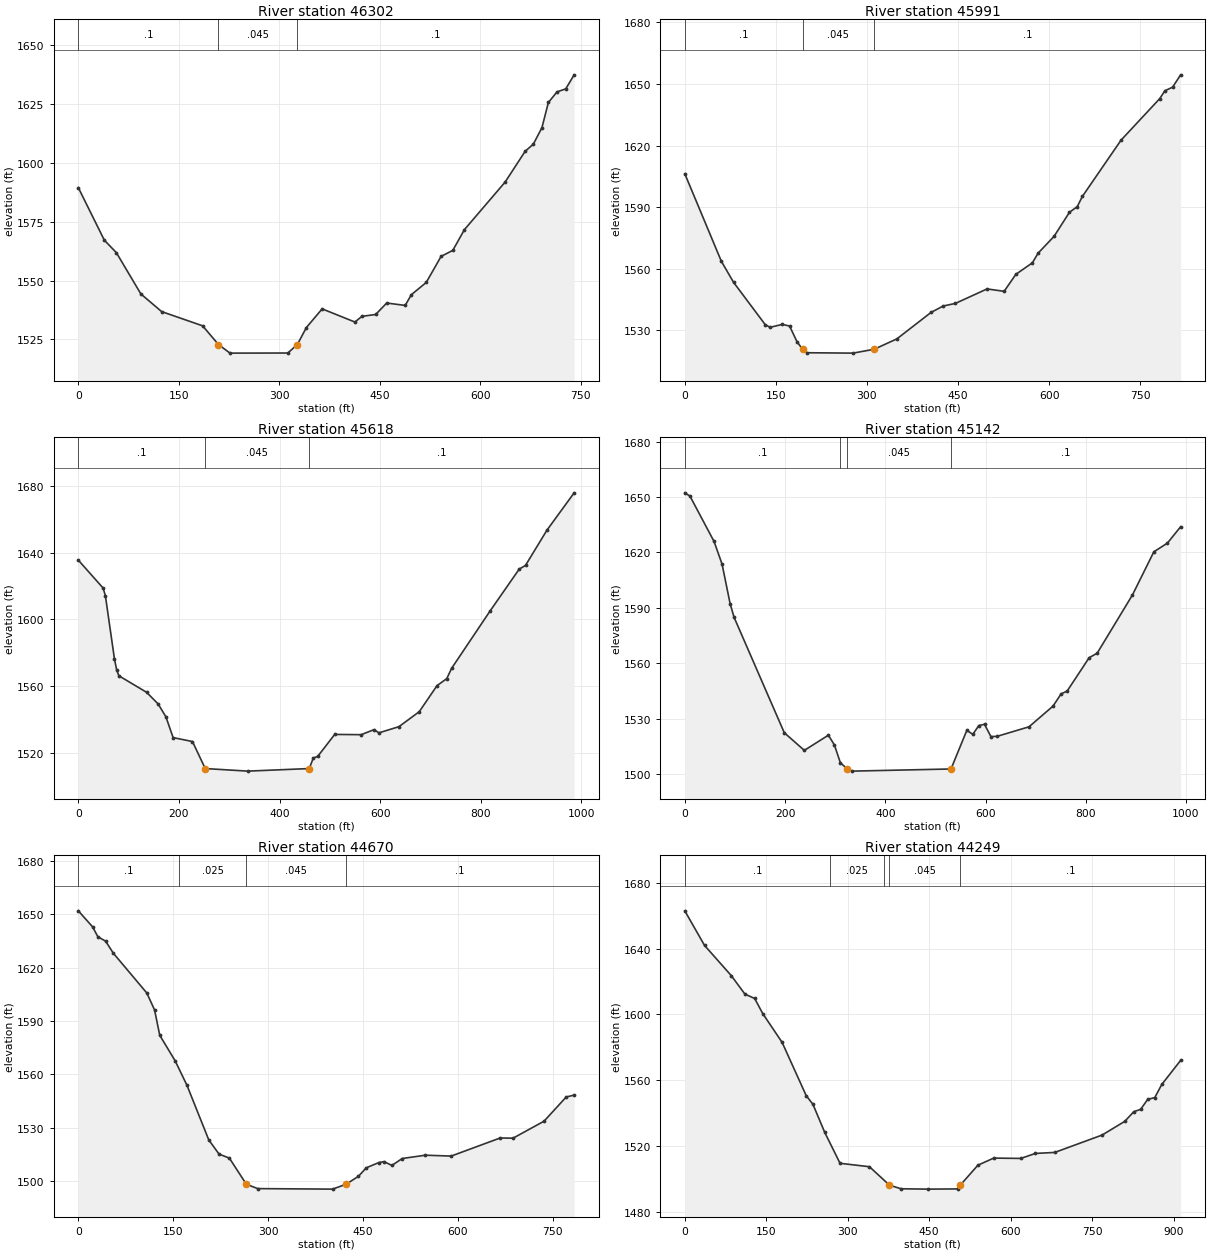
Type RM Length L Ch R = 1 ,46302   ,283.9,311.1,333.8
XS GIS Cut Line= 3
2197440.02828939690116.7748299542197935.96681878689878.222119616
2198111.74250008689806.028536223
#Sta/Elev= 30
       0 1589.42    38.8 1567.15    56.8 1561.84    93.4 1544.31   124.4 1536.82
   185.6 1530.78  209.291522.837   226.5 1519.19   312.8 1519.24  327.071522.839
   340.5 1530.04   364.1 1537.98     413 1532.39   423.5 1534.81     444 1535.59
   460.5 1540.46   488.1 1539.44   497.3    1544   519.5 1549.19   541.7 1560.25
   559.2 1562.82   576.5  1571.6   637.3  1591.8   667.3  1604.9   679.4 1607.88
   692.3 1614.91   701.9 1625.59   714.9 1630.11   727.8 1631.36   740.4 1637.33
#Mann= 3 ,-1,0
       0      .1       0  209.29    .045       0  327.07      .1       0
Bank Sta=209.29,327.07
XS Rating Curve= 0 ,0
Exp/Cntr(USF)=0,0
Exp/Cntr=0.3,0.1

Type RM Length L Ch R = 1 ,45991   ,328,372.3,465.4
XS GIS Cut Line= 3
2197512.22187278690317.6613228722198083.49283701690267.439699642
  2198312.628993690185.829561895
#Sta/Elev= 30
       0 1606.26    60.2  1563.6    80.3 1553.35   132.5 1532.72   140.5 1531.42
   160.6 1532.84   172.6 1532.04   184.7 1524.47  193.911520.725   200.7 1519.03
     277 1518.84  311.921520.726   349.3 1525.78   405.5 1538.66   425.6 1541.79
   445.7 1543.07   497.9 1550.13     526 1548.95   545.3 1557.24   572.5 1562.83
     582 1567.57   608.2 1575.73   633.6 1587.49   646.4 1590.21   654.9 1595.22
   718.6 1622.64   782.3 1642.87   790.8  1646.7   803.5 1648.45   816.7 1654.46
#Mann= 3 ,-1,0
       0      .1       0  193.91    .045       0  311.92      .1       0
Bank Sta=193.91,311.92
XS Rating Curve= 0 ,0
Exp/Cntr(USF)=0,0
Exp/Cntr=0.3,0.1

Type RM Length L Ch R = 1 ,45618   ,418.6,476.6,642
XS GIS Cut Line= 4
2197440.02828939690502.8535585292197546.74923875690556.214033211
2198030.13236233690879.5157327492198265.54622122691039.597156792
#Sta/Elev= 30
       0 1635.49    49.4 1618.73    53.8 1614.14    71.7  1576.6    76.2 1569.76
    80.7  1566.3   135.5 1556.47   158.5 1549.51     174 1541.81   188.4 1529.34
   226.9 1526.97  252.221510.819   336.9 1509.28  458.961510.819   467.1 1517.13
   475.7 1518.06   509.6 1531.24   562.2 1531.08   587.8 1534.11   597.4 1532.18
   637.2 1535.87   677.6 1544.83     713 1560.45   732.3 1564.61     742 1570.81
   818.7 1605.22   876.3 1630.14   888.8 1632.34   931.4 1653.42   985.5 1675.76
#Mann= 3 ,-1,0
       0      .1       0  252.22    .045       0  458.96      .1       0
Bank Sta=252.22,458.96
XS Rating Curve= 0 ,0
Exp/Cntr(USF)=0,0
Exp/Cntr=0.3,0.1

Type RM Length L Ch R = 1 ,45142   ,464.4,471.9,505.2
XS GIS Cut Line= 3
2197305.05767696690502.8535585292197276.80801389691284.427570035
2197279.94686535691491.591765855
#Sta/Elev= 30
       0 1652.25    10.3 1650.48    58.4 1625.91    74.4 1613.63    90.4 1592.29
    98.4 1584.83   198.5 1522.42   238.5 1512.87   286.5 1521.09   298.5 1515.79
   310.5 1506.11  324.471502.807   333.7 1501.64  531.151502.804   562.7 1523.69
   574.7 1521.57   586.7 1526.31     598 1526.99   610.7 1520.36   622.7 1520.43
   686.8 1525.63   734.8 1536.86   750.8 1543.43   762.8 1544.94   806.8 1563.02
   822.8 1565.46   893.2 1596.99   935.9 1620.34   962.9 1625.02   989.3  1633.9
#Mann= 4 ,-1,0
       0      .1       0     310    .025       0  324.47    .045       0
  531.15      .1       0
Bank Sta=324.47,531.15
XS Rating Curve= 0 ,0
Exp/Cntr(USF)=0,0
Exp/Cntr=0.3,0.1

Type RM Length L Ch R = 1 ,44670   ,416,421.5,430.2
XS GIS Cut Line= 2
2196893.86813677690458.9096382042196740.06441563691227.928243902
#Sta/Elev= 30
       0  1651.9    22.7 1642.83    30.9 1637.34    43.1 1634.87    55.3 1628.12
   108.4  1605.7   120.6 1596.17   128.8 1581.96   153.2 1567.59   171.8 1553.89
   206.3 1523.21   222.6 1515.21   238.9 1512.98  265.73 1498.28   283.8 1495.84
   402.1 1495.55  423.41 1498.28   442.9 1502.71   455.5 1507.54   475.5  1510.5
   483.7 1510.99   495.9 1508.85   512.2 1512.75   548.9 1514.61   589.7 1514.12
   667.2 1524.28   687.6 1524.18   736.6 1533.72   771.6  1547.3   784.2 1548.38
#Mann= 4 ,-1,0
       0      .1       0     160    .025       0  265.73    .045       0
  423.41      .1       0
Bank Sta=265.73,423.41
XS Rating Curve= 0 ,0
Exp/Cntr(USF)=0,0
Exp/Cntr=0.3,0.1

Type RM Length L Ch R = 1 ,44249   ,352,360.6,370.7
XS GIS Cut Line= 3
2196576.84414014690276.8562539982196482.67859658690462.048489656
2196288.06980657691140.040403251
#Sta/Elev= 30
       0 1663.02    36.3 1642.01    85.6 1623.62   110.8 1612.36   128.7 1609.73
   143.5 1600.57   179.2 1583.05   223.5 1550.71     236 1545.37   257.6 1528.39
   285.9 1509.51     340 1507.44  376.971496.214   398.3 1494.02   448.2 1493.81
   502.3 1493.94  507.291496.216   539.8 1508.37   568.9 1512.68   618.8 1512.47
   645.6 1515.51   681.3 1516.13   768.5 1526.69   810.3 1535.04   826.9  1540.9
   839.4 1542.29   852.5  1548.4   865.5 1549.46   878.4 1557.46   913.1 1572.07
#Mann= 5 ,-1,0
       0      .1       0  267.76    .025       0  367.76      .1       0
  376.97    .045       0  507.29      .1       0
Bank Sta=376.97,507.29
XS Rating Curve= 0 ,0
Exp/Cntr(USF)=0,0
Exp/Cntr=0.3,0.1

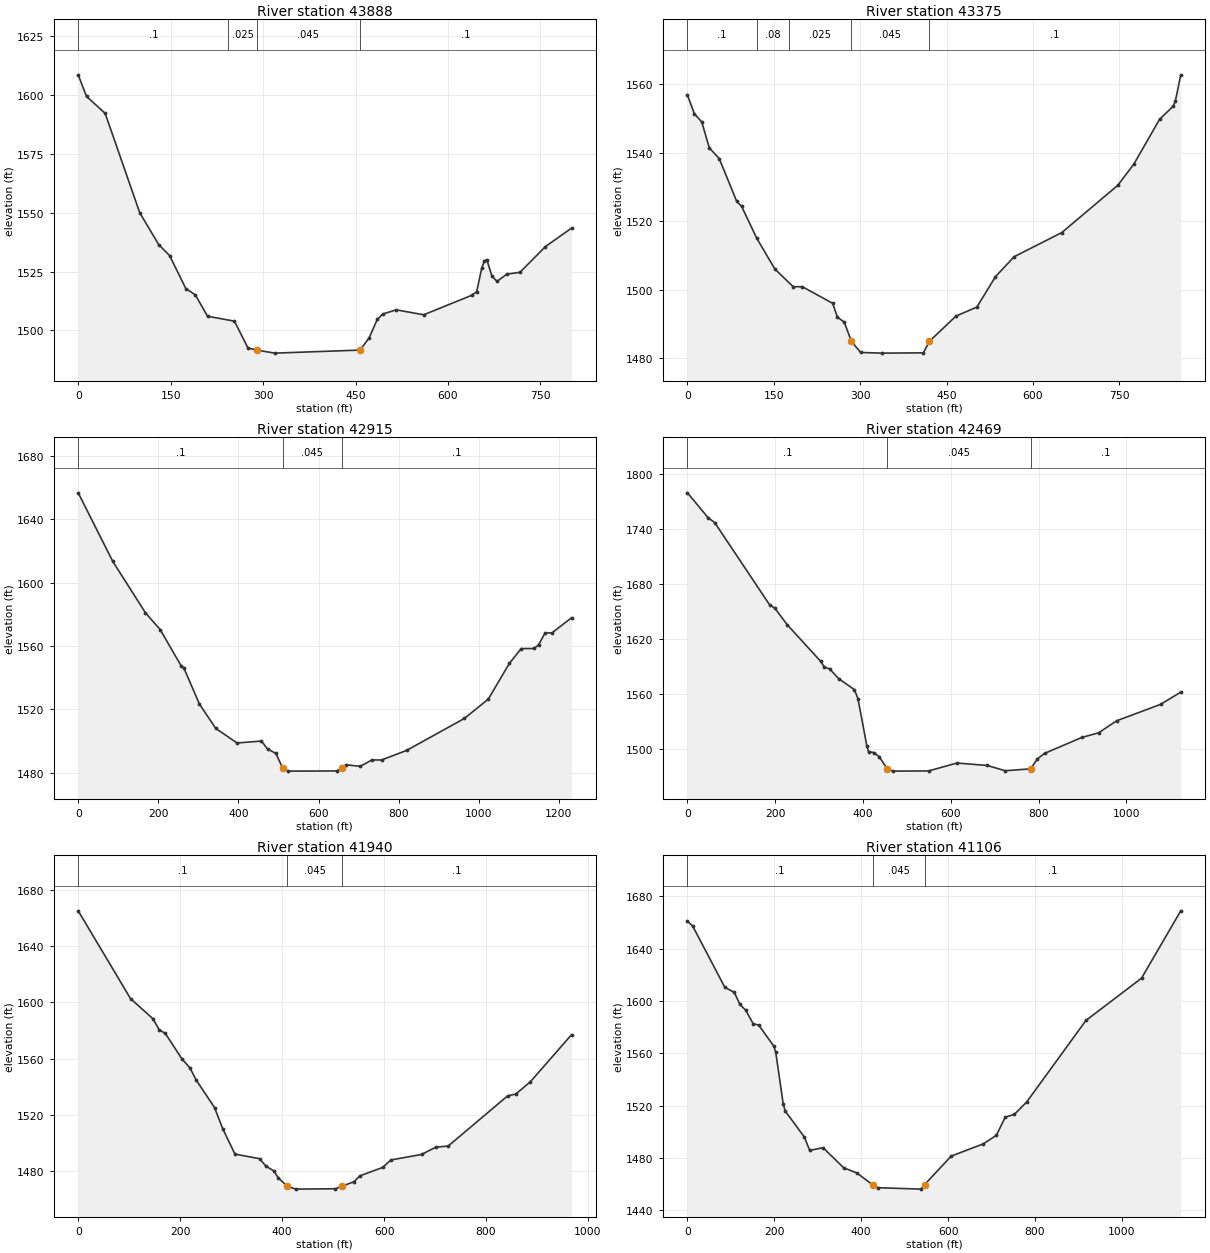
Type RM Length L Ch R = 1 ,43888   ,555.8,512.7,466
XS GIS Cut Line= 4
 2196247.2647377690198.384967702 2196162.5157485 690383.57720336
2196018.12858171 690710.017754352195958.49040413690942.292761785
#Sta/Elev= 30
       0 1608.68    13.5 1599.51    43.7 1592.31    99.8 1550.06   130.6 1536.46
   148.2 1531.83   174.6 1517.79   190.1 1515.08   209.8    1506   253.5 1503.91
   275.4 1492.52  289.641491.605   318.9 1490.31  457.421491.605   472.2 1496.87
   485.3 1504.67   494.1 1506.95     516 1508.72   560.6 1506.62   638.2 1514.87
   646.5  1516.4   654.7 1526.41   658.9 1529.44     663 1530.06   671.2 1523.15
   679.5 1520.81   695.6 1523.93   716.7 1524.66     758 1535.61   800.4 1543.47
#Mann= 4 ,-1,0
       0      .1       0  243.66    .025       0  289.64    .045       0
  457.42      .1       0
Bank Sta=289.64,457.42
XS Rating Curve= 0 ,0
Exp/Cntr(USF)=0,0
Exp/Cntr=0.3,0.1

Type RM Length L Ch R = 1 ,43375   ,498.6,460,410.8
XS GIS Cut Line= 4
2195651.01262966690054.1153954352195588.23560063690207.570355302
2195644.03740421690608.6458185912195640.54979149690894.630061979
#Sta/Elev= 30
       0 1556.92      12 1551.45    24.9 1549.05    37.9 1541.49    55.2 1538.38
    85.4 1525.93    94.1 1524.39     120 1515.22   151.7 1506.13   183.6 1500.96
   199.7 1500.94   252.2  1496.1   260.3 1492.11   272.4 1490.56  284.73 1485.01
   300.7 1481.76   337.3 1481.56   409.7 1481.64  420.18 1485.01   466.3 1492.38
   502.6    1495   534.9 1503.87   567.2  1509.7   650.2 1516.77   747.3 1530.55
   775.3 1536.77   820.1 1549.88   843.3 1553.61   847.3 1555.13   856.7 1562.82
#Mann= 5 ,-1,0
       0      .1       0     120     .08       0   175.8    .025       0
  284.73    .045       0  420.18      .1       0
Bank Sta=284.73,420.18
XS Rating Curve= 0 ,0
Exp/Cntr(USF)=0,0
Exp/Cntr=0.3,0.1

Type RM Length L Ch R = 1 ,42915   ,583.4,446.5,346.7
XS GIS Cut Line= 4
2194651.76015999690266.6750084052195075.39152732 690353.52884704
2195299.69825386690636.6345922212195597.64637112690957.361825075
#Sta/Elev= 30
       0 1656.83    86.2 1613.53   167.8 1581.03   204.6  1570.4   256.6 1547.63
   263.4 1546.32   302.6 1523.34   343.4 1507.94   396.5 1498.73   457.5 1499.95
   472.6 1494.92   493.2 1492.19  510.161483.008   523.8 1480.94   646.3 1481.06
  657.521483.007   669.1 1484.94   704.2 1483.97   733.1    1488   757.4 1487.99
   819.8 1494.03   964.2 1514.26  1023.7 1526.45  1076.4 1549.08  1105.8 1558.37
  1138.3 1558.46  1149.3 1560.85  1165.6 1568.34  1182.2 1568.24  1231.4 1577.86
#Mann= 3 ,-1,0
       0      .1       0  510.16    .045       0  657.52      .1       0
Bank Sta=510.16,657.52
XS Rating Curve= 0 ,0
Exp/Cntr(USF)=0,0
Exp/Cntr=0.3,0.1

Type RM Length L Ch R = 1 ,42469   ,476.9,528.3,526.5
XS GIS Cut Line= 4
2194446.51762256690991.7614999532195063.97371346690918.035399548
2195275.93625212 690876.564468072195543.19336609690977.937856127
#Sta/Elev= 30
       0 1779.75      47  1752.6    62.1 1747.23   187.3 1657.21   199.1 1653.67
   226.9 1635.77   303.8 1595.38   311.9 1589.14   323.9 1587.34   344.1 1576.75
   380.3 1564.62   388.4 1554.87   408.5 1503.38   412.6 1496.66   424.7 1495.87
   436.7  1491.3   455.41478.047     469 1475.54   549.5 1475.78     614  1484.4
   683.2  1481.7   723.9 1475.95  781.851478.042   796.6 1488.66   813.6 1494.95
     898  1512.3   936.5 1517.43   978.1 1530.66  1077.7 1548.49  1123.7 1561.89
#Mann= 3 ,-1,0
       0      .1       0   455.4    .045       0  781.85      .1       0
Bank Sta=455.4,781.85
XS Rating Curve= 0 ,0
Exp/Cntr(USF)=0,0
Exp/Cntr=0.3,0.1

Type RM Length L Ch R = 1 ,41940   ,802.9,834.5,870.7
XS GIS Cut Line= 3
2194606.10798438  691440.57630412195329.19680998691366.707670958
2195568.63812162691341.000310716
#Sta/Elev= 30
       0 1664.99   102.6 1602.67   146.8 1588.29   158.9 1580.52     171 1577.89
   203.1 1560.02   219.2 1553.44   231.3 1544.93   267.5 1525.24   283.5 1510.25
   307.5 1492.21   355.9 1488.97     368 1483.73   384.1 1480.24   392.1 1475.48
  410.431469.296     427 1467.35   504.6 1467.62  516.811469.296   540.9 1472.63
   552.9 1476.83   597.2 1482.73   613.2 1488.04   673.6 1491.97   701.7 1497.17
   725.8 1497.94   842.5 1533.61   858.6 1534.89   887.2 1543.67   967.7    1577
#Mann= 3 ,-1,0
       0      .1       0  410.43    .045       0  516.81      .1       0
Bank Sta=410.43,516.81
XS Rating Curve= 0 ,0
Exp/Cntr(USF)=0,0
Exp/Cntr=0.3,0.1

Type RM Length L Ch R = 1 ,41106   ,1104.3,1154,1191.3
XS GIS Cut Line= 3
2194576.90563922692031.7540994972195149.89121716692273.740710696
2195647.66506103692399.889578571
#Sta/Elev= 30
       0 1661.02    12.2 1657.13      86  1610.4   107.8 1606.55   120.8 1597.27
   133.8 1593.06   151.2 1582.61   164.2  1581.5   198.9 1565.34   203.3  1560.7
   220.3 1521.49     225 1515.87   269.2 1495.91   281.4 1485.74   312.1 1487.83
   359.6 1472.51     390 1468.49  425.991459.547   437.8 1457.27   537.6 1456.16
  545.681459.547   607.1 1481.38   681.2 1490.78     711 1497.27   731.6  1511.2
   752.3 1513.24   780.7 1522.68   917.3  1585.1  1045.2 1617.37  1135.5 1668.86
#Mann= 3 ,-1,0
       0      .1       0  425.99    .045       0  545.68      .1       0
Bank Sta=425.99,545.68
XS Rating Curve= 0 ,0
Exp/Cntr(USF)=0,0
Exp/Cntr=0.3,0.1

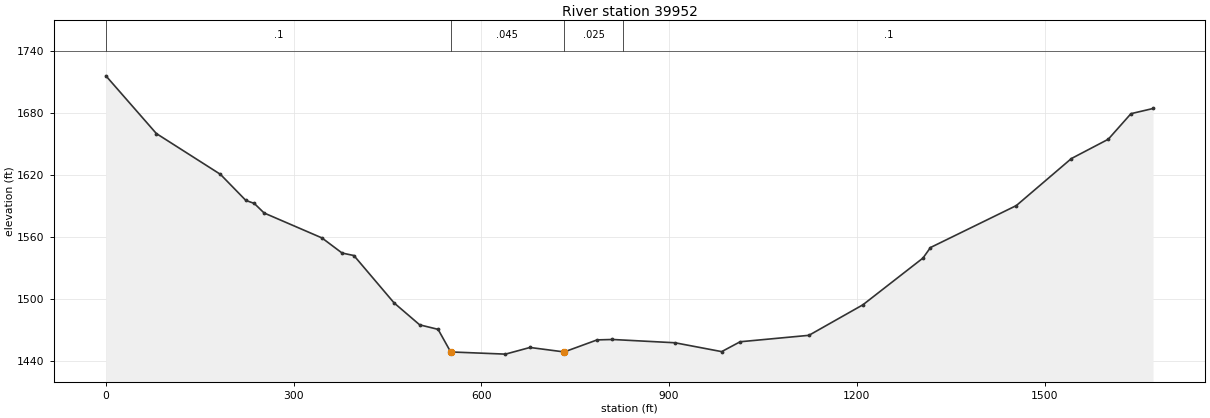
Type RM Length L Ch R = 1 ,39952   ,775.6,790.7,810.6
XS GIS Cut Line= 4
2194094.11936815692582.5993773442194306.52388209692993.304665753
2194493.80068198693258.4986882822195379.73581753693281.756683018
#Sta/Elev= 30
       0 1716.36    80.6 1660.39     183 1620.79   223.6  1595.5   237.1 1592.57
   252.8  1583.3   345.2 1559.11   377.4 1544.45   396.3 1542.01   460.5 1496.07
   501.4 1474.78   530.8 1470.41  550.931448.492   638.5 1446.37   677.7 1452.83
  732.311448.492   784.9 1460.17   809.4 1460.58   909.4 1457.39     984  1448.8
  1013.5 1458.37  1123.4 1464.61  1209.6 1494.21  1305.6 1539.55  1317.6 1549.77
  1454.8 1590.48  1542.8 1636.11  1601.7 1654.82    1638 1679.64  1673.3 1684.67
#Mann= 4 ,-1,0
       0      .1       0  550.93    .045       0  732.31    .025       0
  827.03      .1       0
Bank Sta=550.93,732.31
XS Rating Curve= 0 ,0
Exp/Cntr(USF)=0,0
Exp/Cntr=0.3,0.1