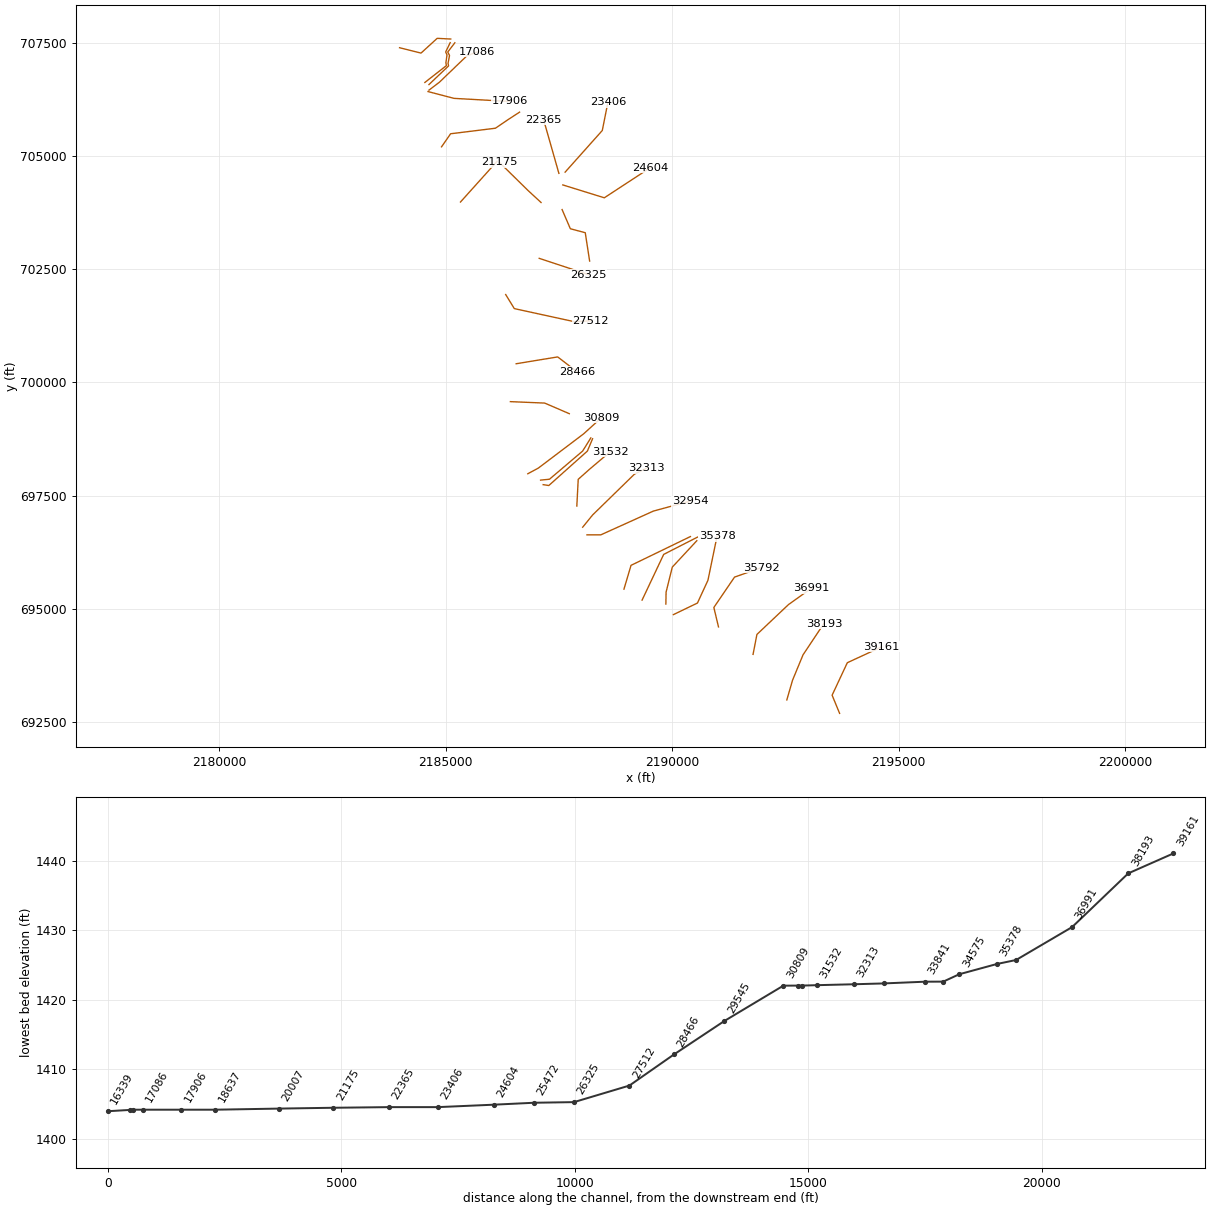
HEC-RAS study BUCKHANR_U.prj: BUCKHANR_U

--- BUCKHANR_U.g01 (geometry) --- (continued)

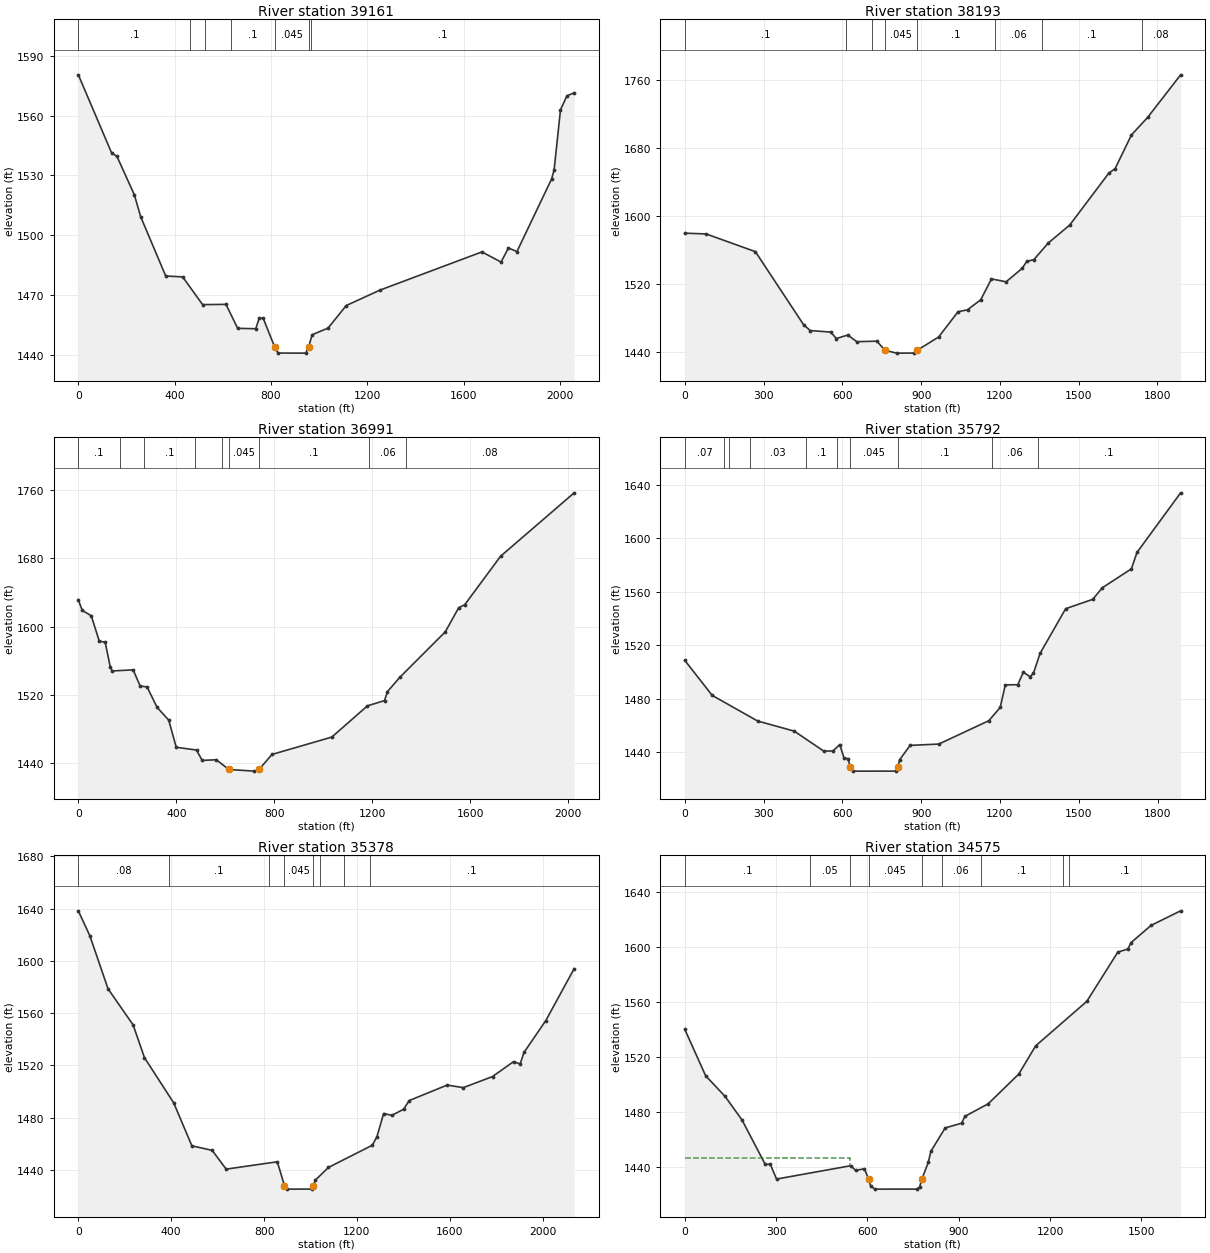
Type RM Length L Ch R = 1 ,39161   ,958.7,968.1,968.6
XS GIS Cut Line= 4
2193694.22594881 692689.724815382193528.84947117693091.353403924
2193864.77429651693808.9406934612194619.73639704694158.123632596
#Sta/Elev= 30
       0 1580.38   137.8  1541.4   160.5 1539.52     233 1520.19   258.5 1509.45
   362.8 1479.67   433.2 1479.23   515.9 1465.34     613 1465.47   661.6 1453.47
   736.7 1453.28   751.1  1458.6   767.6 1458.52  814.631444.246   829.3  1441.1
   944.3 1441.06  956.261444.245   970.8 1450.28  1036.9 1453.61  1112.1 1464.87
  1252.5 1472.62  1675.5 1491.73  1754.9 1486.65  1785.7  1493.7    1821 1491.91
  1964.7 1528.21  1975.2 1532.67  2001.7 1562.84  2028.5 1569.87  2058.5 1571.36
#Mann= 7 ,-1,0
       0      .1       0  464.34     .08       0  524.34     .07       0
  634.34      .1       0  814.63    .045       0  956.26    .025       0
  964.34      .1       0
Bank Sta=814.63,956.26
XS Rating Curve= 0 ,0
Exp/Cntr(USF)=0,0
Exp/Cntr=0.3,0.1

Type RM Length L Ch R = 1 ,38193   ,1216.6,1201.9,1150.5
XS GIS Cut Line= 4
2192528.90120943 692987.333879322192655.74497268693423.737238987
2192887.24045992693983.5895228582193345.71027341694672.965221339
#Sta/Elev= 30
       0 1579.76    81.1 1578.87   268.8 1557.97   452.7 1471.59   477.7 1464.85
   555.6 1463.01   577.2 1455.42   620.5 1459.54   655.1 1451.67   731.5 1452.34
   762.21441.531   806.6 1438.19   871.6 1438.27     8851441.532   966.8 1457.27
  1040.4 1487.02  1076.6 1489.32    1127 1501.18  1167.9  1525.8  1223.7 1522.38
  1284.3 1538.12  1302.4 1546.46  1329.2 1548.51  1384.1 1568.14  1465.7  1589.3
  1614.6 1650.55  1638.7 1655.91  1701.1 1695.78  1762.6 1716.39  1888.2 1766.65
#Mann= 8 ,-1,0
       0      .1       0  614.46    .025       0  714.46      .1       0
   762.2    .045       0     885      .1       0 1180.29     .06       0
 1360.29      .1       0 1740.29     .08       0
Bank Sta=762.2,885
XS Rating Curve= 0 ,0
Exp/Cntr(USF)=0,0
Exp/Cntr=0.3,0.1

Type RM Length L Ch R = 1 ,36991   ,1183.1,1199.5,1207.2
XS GIS Cut Line= 4
2191783.50516577693993.3443205912191868.59284585694433.567103957
2192563.85573864695091.7477068352193067.97546928695451.833228718
#Sta/Elev= 30
       0 1631.39    16.1 1619.07    52.8 1612.79    85.4 1583.15   109.8 1581.56
   130.2 1552.99   138.3    1548   223.9 1549.32   252.4  1530.4   280.9 1529.21
   321.7 1505.26   369.2 1490.36   399.9 1458.47   482.7 1455.22     506 1443.03
   563.5 1443.82  614.911432.398   719.4 1430.47  738.11  1432.4   791.1 1450.06
  1035.5 1470.44  1180.9 1507.08  1250.7 1513.24  1262.7 1523.78  1312.6 1540.41
  1498.8 1593.89  1553.6 1622.17  1578.2 1625.71  1724.8 1682.64  2025.3 1757.04
#Mann= 9 ,-1,0
       0      .1       0     170     .03       0     270      .1       0
  478.37     .03       0  588.37      .1       0  614.91    .045       0
  738.11      .1       0 1188.37     .06       0 1338.37     .08       0
Bank Sta=614.91,738.11
XS Rating Curve= 0 ,0
Exp/Cntr(USF)=0,0
Exp/Cntr=0.3,0.1

Type RM Length L Ch R = 1 ,35792   ,402.9,413.3,434
XS GIS Cut Line= 4
2191020.55739325694599.7462945732190917.76754249695029.045083047
 2191374.2754091695700.2023438992191972.87512824695911.828507231
#Sta/Elev= 30
       0 1508.58   104.3 1482.41     277 1463.25   416.9 1455.64   528.7 1440.77
   564.2  1440.8   590.1 1445.62   606.1 1435.65   621.8 1434.94  629.841428.911
   641.9 1425.74   804.4 1425.75  811.461428.908   817.6 1434.15   857.9    1445
   967.3 1445.99  1157.6 1463.46  1201.1  1473.4  1220.4 1490.27  1267.9 1490.38
  1289.1 1499.79  1314.5 1496.41  1327.3 1498.77  1352.7 1513.79  1450.3 1547.25
  1553.2 1554.24  1590.3 1562.97  1700.5 1577.05  1721.8 1589.31    1888 1633.92
#Mann= 10 ,-1,0
       0     .07       0     150     .03       0     170     .08       0
     250     .03       0  461.43      .1       0  581.43    .025       0
  629.84    .045       0  811.46      .1       0 1171.43     .06       0
 1343.13      .1       0
Bank Sta=629.84,811.46
XS Rating Curve= 0 ,0
Exp/Cntr(USF)=0,0
Exp/Cntr=0.3,0.1

Type RM Length L Ch R = 1 ,35378   ,794.2,803.7,829.6
XS GIS Cut Line= 4
2190023.58253059694870.8603395322190555.72199538695127.429638432
2190787.59910614695630.3674814962190987.72360873696600.858698353
#Sta/Elev= 30
       0 1638.36    49.5 1619.29     128 1578.62   235.9 1550.98   284.9 1525.87
   410.6  1491.3   489.1 1458.33   576.4 1454.87   636.7 1440.47     857 1446.12
  887.781427.839   896.6 1425.16  1006.7  1425.2 1012.841427.834  1020.5 1431.98
  1077.2 1441.78    1266 1458.77  1286.1 1465.32  1314.9 1483.09  1350.6  1481.7
  1400.7 1486.34  1425.3 1493.03  1588.5 1504.87    1658 1502.91    1784 1511.41
  1874.4 1522.82    1903 1521.05  1919.4 1529.87  2013.3 1554.28  2135.5 1594.06
#Mann= 8 ,-1,0
       0     .08       0     390      .1       0  820.76     .08       0
  887.78    .045       0 1012.84    .025       0 1040.76      .1       0
 1144.58     .06       0 1254.58      .1       0
Bank Sta=887.78,1012.84
XS Rating Curve= 0 ,0
Exp/Cntr(USF)=0,0
Exp/Cntr=0.3,0.1

Type RM Length L Ch R = 1 ,34575   ,359.6,342.6,302.3
XS GIS Cut Line= 4
2189858.68891248695105.0084573242189863.05516587695366.983660697
2190000.59214764 695921.497841172190542.00756794696504.392668676
#Sta/Elev= 30
       0 1540.06    68.5 1506.27   132.2 1491.28   188.2 1473.98   264.3 1441.67
   280.8 1441.86   301.4 1431.02   545.4 1440.76     561 1437.31   589.8 1438.54
  603.861431.085   610.5 1425.91   624.7 1423.69   762.9 1423.71   771.2 1425.18
   779.4 1431.28     800 1443.26   808.3 1451.18   855.4 1468.28   909.2 1471.69
   920.2  1476.7   996.7 1485.84  1097.2 1507.51  1152.6 1528.04  1320.6 1560.43
  1422.5  1596.3  1455.3 1598.58  1466.2 1603.28  1532.1 1615.83  1628.9  1626.4
#Mann= 9 ,-1,0
       0      .1       0  412.01     .05       0  542.01     .06       0
  603.86    .045       0   779.4      .1       0  843.33     .06       0
  973.33      .1       0 1243.33     .06       0 1263.33      .1       0
#XS Ineff= 2 , 0
          543.31 1446.18
Permanent Ineff=
       F       F
Bank Sta=603.86,779.4
XS Rating Curve= 0 ,0
Exp/Cntr(USF)=0,0
Exp/Cntr=0.3,0.1

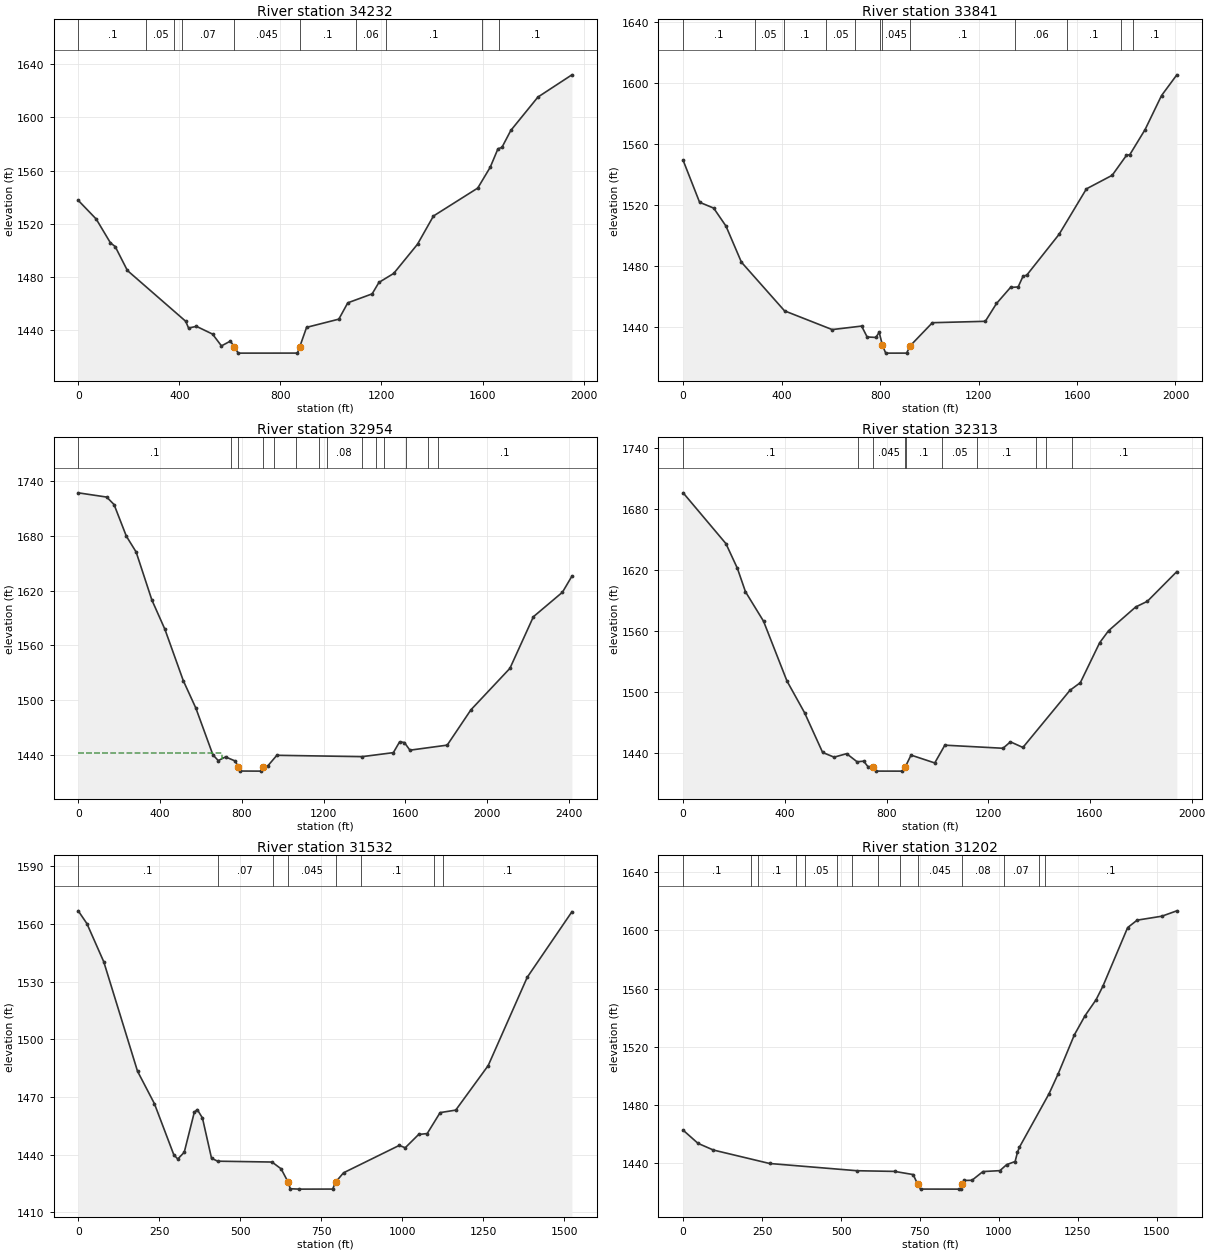
Type RM Length L Ch R = 1 ,34232   ,437.6,390.8,307.8
XS GIS Cut Line= 3
2189333.71135054695192.7080052112189810.26750058696201.741393376
2190555.90793027696583.327304929
#Sta/Elev= 30
       0  1537.6    71.3  1523.5   127.5  1505.6   146.3 1502.83   194.5 1484.82
   425.2 1446.61   436.6 1441.52   467.9 1442.77   531.4 1436.97   566.8 1428.07
   602.1 1431.68  617.15  1427.5   633.1 1422.63   867.6 1422.66  876.751427.503
   903.6 1442.02  1031.2  1448.2  1066.6 1460.48    1163 1467.22  1189.9 1475.84
  1248.4 1482.62  1342.5 1504.58  1405.6 1525.81  1580.9 1546.84  1630.3 1562.54
  1660.8 1576.38  1676.6 1577.46  1711.7 1590.21    1819 1615.33  1953.5 1632.06
#Mann= 10 ,-1,0
       0      .1       0     270     .05       0     380      .1       0
     410     .07       0  617.15    .045       0  876.75      .1       0
    1100     .06       0 1215.91      .1       0 1595.91     .07       0
 1665.91      .1       0
Bank Sta=617.15,876.75
XS Rating Curve= 0 ,0
Exp/Cntr(USF)=0,0
Exp/Cntr=0.3,0.1

Type RM Length L Ch R = 1 ,33841   ,890.4,887.4,886.4
XS GIS Cut Line= 3
2188933.15255953695434.3035385852189089.25420468695960.119606467
2190400.10433278696596.083989856
#Sta/Elev= 30
       0 1549.19    66.8 1521.67     124 1517.86   174.1    1506   236.7 1482.35
   411.9 1450.38   605.4 1438.08     725 1440.38   747.4 1433.24   782.9 1432.92
   796.3 1436.33   809.6 1427.72   822.9 1422.62   907.7 1422.63  923.131427.563
  1012.5  1442.6  1227.5 1443.51  1272.9 1455.21  1329.8 1465.75  1360.9 1466.09
  1380.7 1473.12  1395.7 1473.81  1527.4 1500.69  1638.1 1530.47  1742.9  1539.4
    1801 1552.52  1814.4 1552.93  1876.6 1569.44  1943.3 1591.74  2005.5 1605.36
#Mann= 12 ,-1,0
       0      .1       0     290     .05       0     410      .1       0
   578.5     .05       0   698.5     .06       0   798.5     .07       0
   809.6    .045       0  923.13      .1       0  1348.5     .06       0
  1558.5      .1       0  1778.5     .07       0  1828.5      .1       0
Bank Sta=809.6,923.13
XS Rating Curve= 0 ,0
Exp/Cntr(USF)=0,0
Exp/Cntr=0.3,0.1

Type RM Length L Ch R = 1 ,32954   ,616,641.1,666.6
XS GIS Cut Line= 4
2188117.00406617696634.1985220892188423.07675977696634.198522089
2189584.42012251697159.4808690592190388.83630361697377.204319751
#Sta/Elev= 30
       0 1726.89   139.2 1722.25   175.2 1714.08   235.2 1679.53   283.2 1662.12
     360 1609.68     424 1577.48   513.6 1521.44   575.2 1491.32   658.5 1440.21
   684.8 1433.89   720.3 1437.93   768.2 1433.39  781.591427.058   790.2 1422.48
   895.6 1422.37  904.251427.058   925.8 1427.79   971.2 1439.69  1388.3 1438.21
  1540.9  1442.6  1571.6 1454.46  1594.9 1453.68  1621.9 1445.29  1804.2 1450.82
  1920.2 1489.47  2110.9 1534.85  2225.6 1591.29  2367.8 1618.15    2414  1635.7
#Mann= 14 ,-1,0
       0      .1       0  746.07     .07       0  781.59    .045       0
  904.25    .025       0  956.07      .1       0 1066.07     .06       0
 1176.07      .1       0 1216.07     .08       0 1386.07      .1       0
 1456.07     .08       0 1496.07      .1       0 1600.69     .08       0
 1710.69     .06       0 1760.69      .1       0
#XS Ineff= 2 , 0
          701.84 1442.04
Permanent Ineff=
       F       F
Bank Sta=781.59,904.25
XS Rating Curve= 0 ,0
Exp/Cntr(USF)=0,0
Exp/Cntr=0.3,0.1

Type RM Length L Ch R = 1 ,32313   ,783.9,780.4,776.2
XS GIS Cut Line= 4
2188021.86255188696802.7652846052188240.61450642697072.559361876
2189166.66444733697976.734107327 2189436.4585246698107.985280054
#Sta/Elev= 30
       0 1696.11   168.3 1646.11   213.3 1621.83   245.1 1598.77   316.2 1569.77
   408.2 1510.98   477.6 1479.69   548.6 1440.62   593.6    1436     643 1439.42
   684.1 1431.45   710.1 1432.07   726.5 1426.73   747.21426.633   760.4 1422.28
     861 1422.25   873.91426.539   896.2 1438.03   989.5  1430.3  1029.2 1447.79
    1258 1444.75  1287.2 1451.08  1336.2 1445.54  1521.3 1501.79  1562.1 1509.31
  1638.1 1548.61    1673 1560.39  1779.8 1583.79  1825.6 1589.35  1941.6  1618.6
#Mann= 10 ,-1,0
       0      .1       0  687.33     .07       0   747.2    .045       0
   873.9    .025       0  877.33      .1       0 1017.33     .05       0
 1157.33      .1       0 1387.33     .07       0 1427.33     .06       0
 1527.33      .1       0
Bank Sta=747.2,873.9
XS Rating Curve= 0 ,0
Exp/Cntr(USF)=0,0
Exp/Cntr=0.3,0.1

Type RM Length L Ch R = 1 ,31532   ,330.9,330.9,331.2
XS GIS Cut Line= 4
2187892.53024309697270.502017016 2187923.3397395697860.581416427
2188173.91797904698084.290673246 2188629.4800778698468.880034523
#Sta/Elev= 30
       0 1566.93    26.7 1560.31    78.8 1540.41   182.9 1483.48     235 1466.61
   294.8 1440.03   307.1 1437.77   327.1 1441.32   358.2 1462.19   367.2 1463.54
   383.2 1459.14   411.2 1438.21     430 1436.66   597.8 1436.22   625.9 1432.68
   647.51425.778   654.2 1422.31   681.9 1422.12     785 1422.15  793.941425.777
   818.5 1430.62   990.2 1444.86  1008.8 1443.65  1050.1 1450.55  1076.6 1451.04
  1116.4 1461.93  1164.6 1463.24  1264.8 1486.43  1385.2 1532.36    1523 1566.44
#Mann= 8 ,-1,0
       0      .1       0     430     .07       0  600.88      .1       0
   647.5    .045       0  793.94    .025       0  870.88      .1       0
 1096.79     .07       0 1126.79      .1       0
Bank Sta=647.5,793.94
XS Rating Curve= 0 ,0
Exp/Cntr(USF)=0,0
Exp/Cntr=0.3,0.1

Type RM Length L Ch R = 1 ,31202   ,82,79.6,77.4
XS GIS Cut Line= 4
2187149.50069292697742.7988259072187273.88742931697723.662404923
2188125.45816308698484.3351390212188240.27668898698757.029138037
#Sta/Elev= 30
       0 1462.58    47.2 1453.52    95.8 1448.94   273.7 1439.69   550.6 1434.71
   669.6 1434.25   728.6 1432.07  742.951425.296   751.8 1422.09   873.6 1422.06
   879.8 1422.23  884.721425.303   890.5 1428.02   914.7 1428.13   949.5 1434.14
  1003.2 1434.77  1024.6  1438.9  1051.4 1441.05  1058.8 1447.32  1064.8 1450.79
  1158.7  1487.6  1188.1  1501.5    1239 1528.12  1272.9 1541.32  1307.7 1552.27
  1329.4 1561.59  1407.8  1601.9  1437.9 1607.02    1516 1609.73  1563.6 1613.43
#Mann= 14 ,-1,0
       0      .1       0  215.85     .06       0  235.85      .1       0
  355.85     .07       0  385.85     .05       0  485.85     .08       0
  535.85    .025       0  615.85     .06       0  685.85     .08       0
  742.95    .045       0  884.72     .08       0 1015.85     .07       0
 1125.85     .06       0 1145.85      .1       0
Bank Sta=742.95,884.72
XS Rating Curve= 0 ,0
Exp/Cntr(USF)=0,0
Exp/Cntr=0.3,0.1

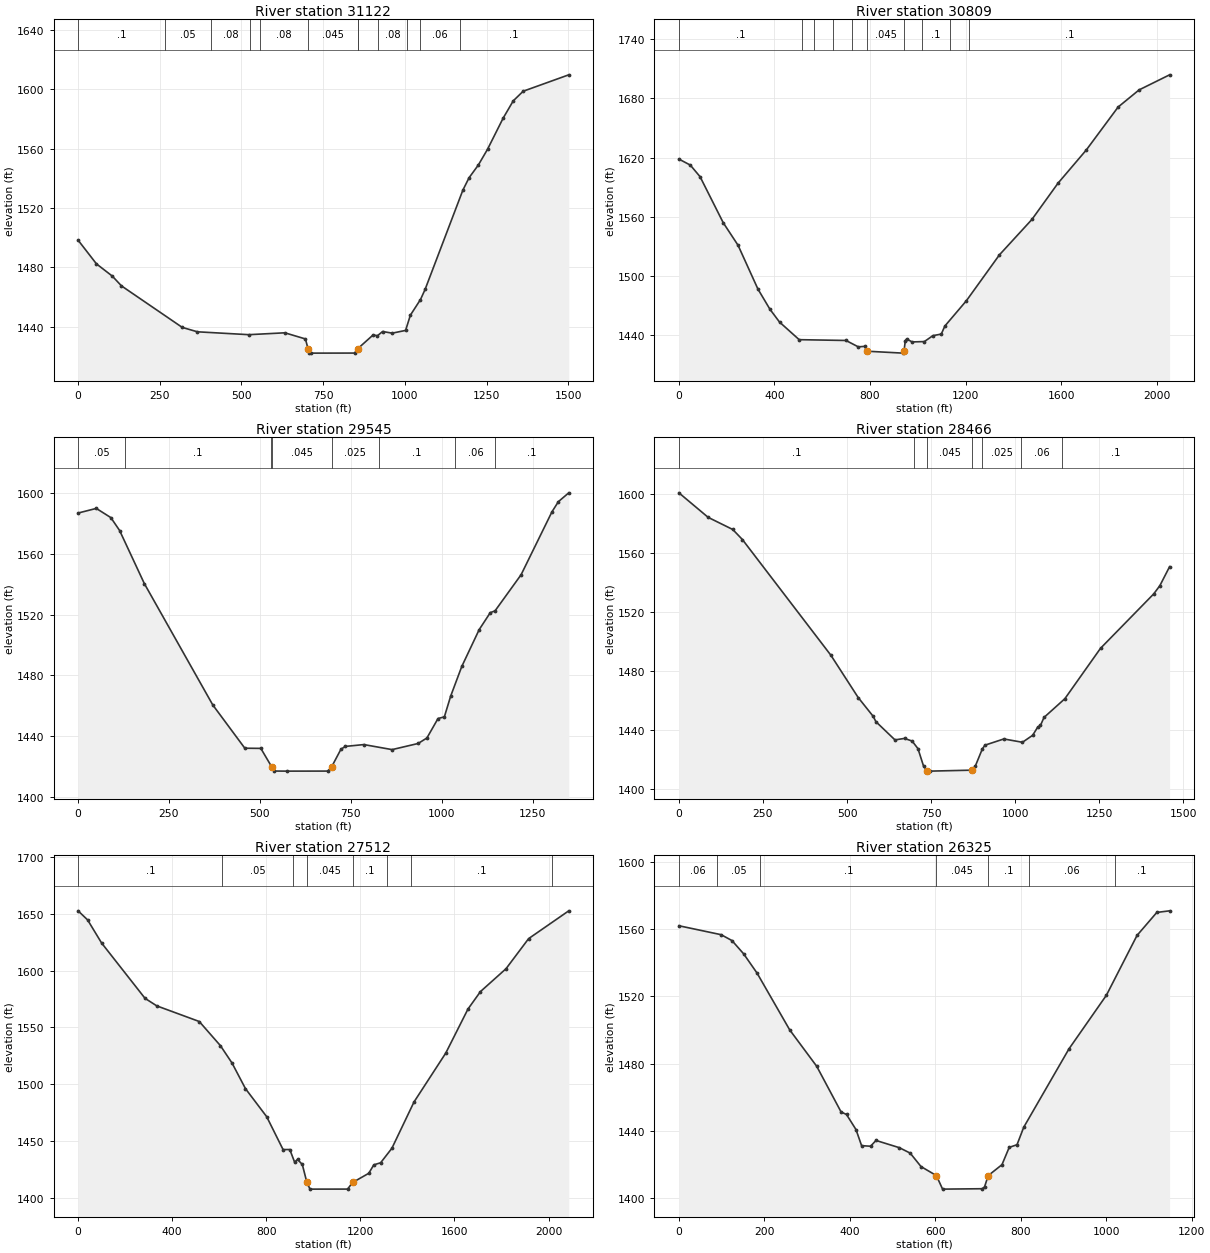
Type RM Length L Ch R = 1 ,31122   ,317.8,313.2,307.9
XS GIS Cut Line= 4
2187092.09142997697843.2650360712187288.23974505697862.401457054
2188020.20784767698484.3351390212188202.00384702 698776.16555902
#Sta/Elev= 30
       0 1498.23    56.3 1482.22   104.6 1474.02   132.7 1467.41   318.7 1439.41
     365 1436.44   522.4  1434.5   632.7 1435.76   695.6 1431.63  703.46 1425.17
   707.9 1422.45   714.1 1422.06     846  1422.1  856.331425.168   902.8 1434.33
   916.1 1433.79   931.8 1436.64   961.2 1435.53  1002.1 1437.37  1016.8 1447.66
  1047.7 1458.19  1061.7 1464.96  1177.4 1531.96  1196.3  1540.3  1224.6 1548.85
  1252.8 1559.49  1300.5 1580.44  1331.5 1592.14  1361.8 1598.62  1501.4 1609.69
#Mann= 12 ,-1,0
       0      .1       0  267.08     .05       0  407.08     .08       0
  527.08    .025       0  557.08     .08       0  703.46    .045       0
  856.33    .025       0  857.08      .1       0  917.08     .08       0
 1007.08     .07       0 1047.08     .06       0 1167.59      .1       0
Bank Sta=703.46,856.33
XS Rating Curve= 0 ,0
Exp/Cntr(USF)=0,0
Exp/Cntr=0.3,0.1

Type RM Length L Ch R = 1 ,30809   ,1319.5,1263.8,1194.2
XS GIS Cut Line= 4
2186810.19477549697983.7479953782187044.25036472698109.777928038
2188043.48768794698865.9575239942188439.58176202699226.043045878
#Sta/Elev= 30
       0 1618.43    47.7 1612.36    88.6 1600.61   185.6 1554.02   247.6 1531.23
   330.9 1486.86   381.1 1466.46   421.2  1453.5   503.5 1435.67   699.4 1434.86
   750.8 1428.42   777.4 1428.86   787.51423.991   937.9 1422.05  942.361424.001
   947.9 1434.76   953.5 1436.39   976.3 1433.38  1027.7 1433.75  1063.3 1439.74
  1098.4 1441.32  1113.4 1449.46  1203.8 1475.15  1341.8 1521.49  1477.9 1557.34
  1586.8 1593.93  1705.8 1627.73  1838.8 1671.11  1926.6 1688.46  2054.2  1703.7
#Mann= 10 ,-1,0
       0      .1       0  515.83     .05       0  565.83     .08       0
  645.83     .07       0  725.83    .025       0   787.5    .045       0
  942.36    .025       0 1015.83      .1       0 1135.83     .06       0
 1215.83      .1       0
Bank Sta=787.5,942.36
XS Rating Curve= 0 ,0
Exp/Cntr(USF)=0,0
Exp/Cntr=0.3,0.1

Type RM Length L Ch R = 1 ,29545   ,1074.9,1079.2,1092.2
XS GIS Cut Line= 3
2186426.10103844699576.974948851 2187182.9322773699545.113852832
2187726.42585152 699311.08629126
#Sta/Elev= 30
       0 1587.06    50.1 1590.12    90.1 1584.06   114.2 1575.56   182.2 1540.57
   370.4 1460.58   458.5 1432.07   502.5 1431.96  532.63 1419.69   538.6 1417.03
   574.2 1416.97   686.7    1417  696.951419.693   722.7 1431.37   734.7 1433.25
   785.8 1434.47   863.4 1431.15     935 1435.19   959.2 1438.83   989.7 1451.65
  1007.1 1452.71  1024.5 1466.41    1055 1485.94  1102.9 1510.25  1133.4 1521.42
  1146.5 1522.61  1218.1  1546.4    1303 1587.88  1320.7 1594.58  1349.2 1600.39
#Mann= 8 ,-1,0
       0     .05       0     130      .1       0     530     .07       0
  532.63    .045       0  696.95    .025       0   827.5      .1       0
  1037.5     .06       0  1147.5      .1       0
Bank Sta=532.63,696.95
XS Rating Curve= 0 ,0
Exp/Cntr(USF)=0,0
Exp/Cntr=0.3,0.1

Type RM Length L Ch R = 1 ,28466   ,998.8,954,917.3
XS GIS Cut Line= 3
2186554.20301727700414.1701981292187470.14085195700565.086624379
2187891.08507722700241.719607783
#Sta/Elev= 30
       0 1600.86    87.1 1584.21   160.1 1576.01   188.8  1569.2     452 1490.71
   533.1 1462.07   577.7 1449.32   585.8 1445.69   642.5 1433.34   670.9 1434.34
   693.5 1432.55   710.9  1427.4   727.7 1415.42   739.21412.333   746.2 1412.16
     8721412.822   881.7 1415.74   902.3 1427.22   910.1 1429.77   966.2 1433.97
  1021.6 1431.72  1051.9 1436.46  1066.6 1441.85  1075.2 1443.19  1085.7 1448.56
  1147.7 1461.27  1253.7 1495.43  1411.8  1532.3  1430.2 1537.93  1459.1 1550.79
#Mann= 7 ,-1,0
       0      .1       0     700     .06       0   739.2    .045       0
     872      .1       0     900    .025       0 1018.29     .06       0
 1138.29      .1       0
Bank Sta=739.2,872
XS Rating Curve= 0 ,0
Exp/Cntr(USF)=0,0
Exp/Cntr=0.3,0.1

Type RM Length L Ch R = 1 ,27512   ,1200.4,1187.1,1173.1
XS GIS Cut Line= 4
2186322.11174802701942.4970358652186512.15688457 701632.42339202
2187842.47284042701342.354499392 2188202.5583623701362.359250608
#Sta/Elev= 30
       0 1652.61    40.3 1644.68   100.1 1624.26   284.6  1575.6   334.6 1568.96
   515.2  1555.2   605.1 1533.95   654.4 1518.68   711.7 1496.08   801.8 1471.43
   871.4  1442.5     900 1442.54   920.5 1431.42   932.8 1433.86   953.2 1429.37
   972.71413.531     986 1407.69  1145.6 1407.72 1166.98 1413.53  1235.7 1421.62
  1257.1 1429.05  1286.2  1430.9    1334 1443.64  1428.1 1484.42    1563 1527.41
  1657.4 1566.17  1710.6 1581.56  1819.1 1601.65  1915.2 1628.14  2085.9 1652.61
#Mann= 8 ,-1,0
       0      .1       0  613.68     .05       0  913.68     .07       0
   972.7    .045       0 1166.98      .1       0 1313.68     .06       0
 1413.68      .1       0 2015.25     .05       0
Bank Sta=972.7,1166.98
XS Rating Curve= 0 ,0
Exp/Cntr(USF)=0,0
Exp/Cntr=0.3,0.1

Type RM Length L Ch R = 1 ,26325   ,846.3,852.4,855.1
XS GIS Cut Line= 2
  2187062.287543702742.6870844962188152.54648426702382.601562612
#Sta/Elev= 30
       0 1561.98    98.9 1556.66   124.2 1553.17   151.5 1545.28     183 1533.78
   259.2 1500.07   322.5 1478.38   379.5 1451.22   392.2 1449.71   414.4 1440.74
   427.5 1431.17   448.5 1430.83   461.2 1434.27   515.9 1429.96   541.2 1426.73
   566.5 1418.74  602.591413.353     617 1405.31   709.7 1405.55   715.2 1406.64
  723.791413.356     756 1419.85   772.9 1430.14   791.2 1431.73     807 1442.17
   912.6 1488.68  1000.4 1520.67    1072 1556.22  1118.3 1569.91  1148.2 1570.86
#Mann= 7 ,-1,0
       0     .06       0      90     .05       0     190      .1       0
  602.59    .045       0  723.79      .1       0     820     .06       0
    1020      .1       0
Bank Sta=602.59,723.79
XS Rating Curve= 0 ,0
Exp/Cntr(USF)=0,0
Exp/Cntr=0.3,0.1

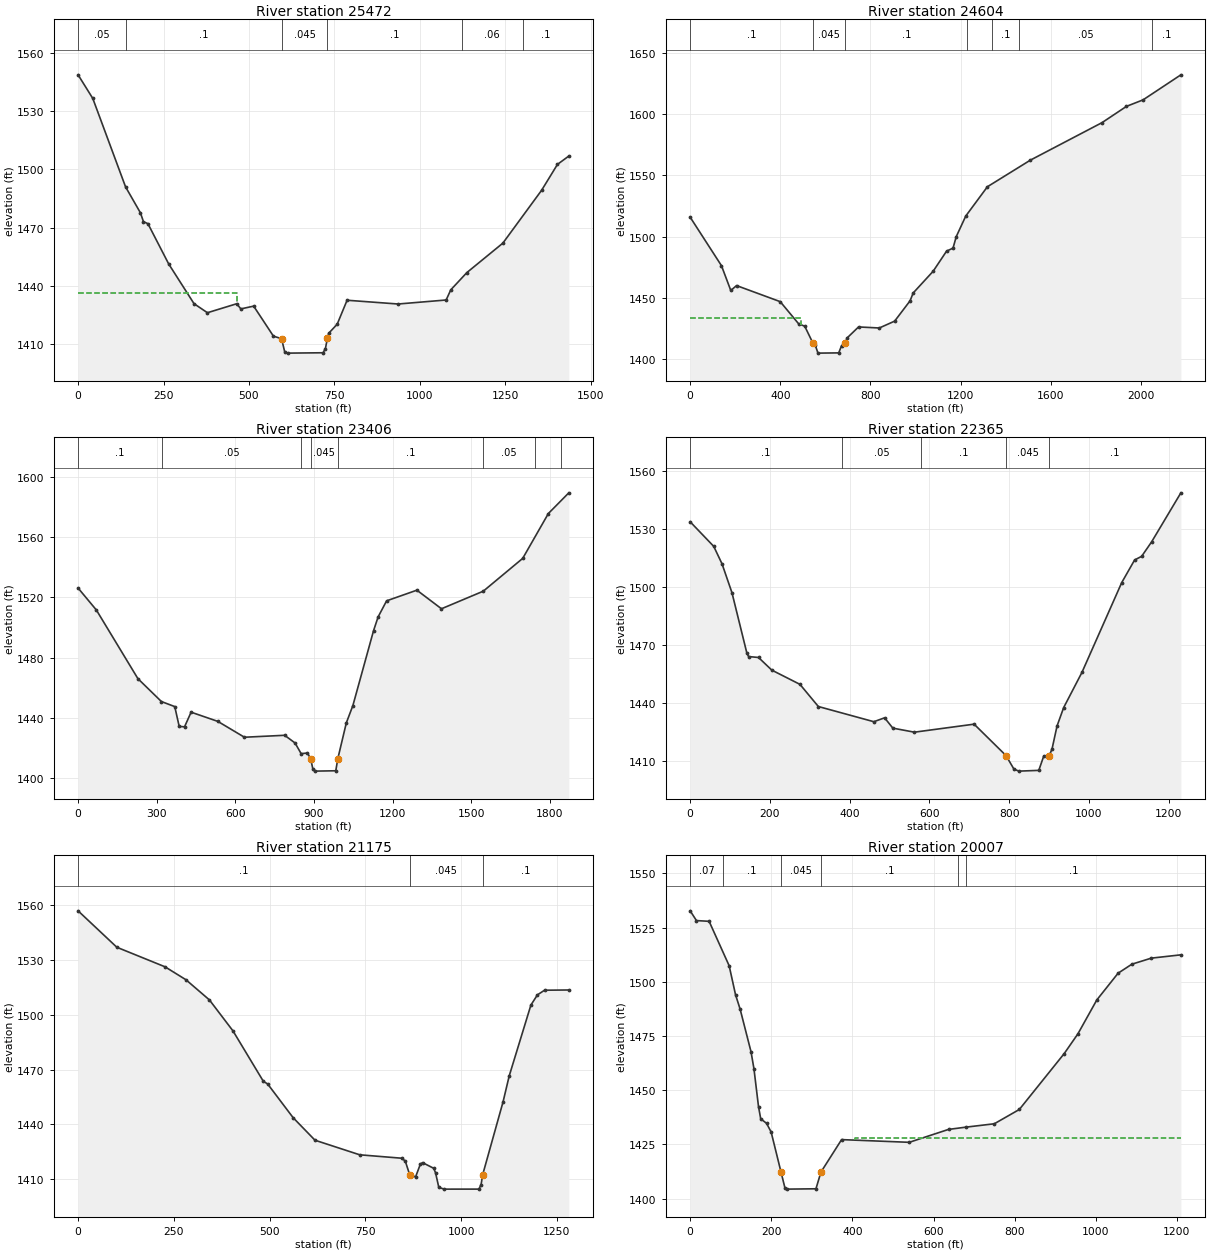
Type RM Length L Ch R = 1 ,25472   ,871.5,868.8,865.2
XS GIS Cut Line= 4
2187567.15641338703820.7286607882187749.81834688703396.867206765
  2188078.554069 703308.921468622188175.33961869702682.452460251
#Sta/Elev= 30
       0 1548.79      43 1536.62   138.9    1491   182.4  1477.6   191.2 1473.07
   204.4 1471.98   265.2 1451.19   339.2 1430.73   378.4 1426.06     464 1430.69
   476.3 1428.04   513.7 1429.47   571.6 1413.96   595.3 1412.68   604.8  1405.7
     613 1405.22   716.6 1405.41   723.5 1407.51   729.61413.015   733.1 1415.45
     758 1420.12     787  1432.5   936.3 1430.56  1076.8 1432.63  1090.5  1437.9
  1137.5 1446.78  1242.8 1461.97  1356.1 1489.23  1402.5 1502.59  1435.7 1506.89
#Mann= 6 ,-1,0
       0     .05       0     140      .1       0   595.3    .045       0
   729.6      .1       0 1121.84     .06       0 1301.84      .1       0
#XS Ineff= 2 , 0
          465.07 1436.37
Permanent Ineff=
       F       F
Bank Sta=595.3,729.6
XS Rating Curve= 0 ,0
Exp/Cntr(USF)=0,0
Exp/Cntr=0.3,0.1

Type RM Length L Ch R = 1 ,24604   ,1129.4,1197.1,1276.1
XS GIS Cut Line= 3
2187582.34095618704365.1216133232188499.65791241704080.534168302
2189518.13452241704747.612128513
#Sta/Elev= 30
       0 1515.92   138.9 1476.35   180.4 1456.07     206 1460.07   399.8 1446.95
   480.9 1429.01   508.7 1426.86  544.851413.127   554.7 1411.79   567.3 1404.94
   659.4 1405.14     672 1410.99  688.111413.126   697.1 1417.42   747.4 1426.31
   839.5 1425.46   907.6 1431.06   976.2 1447.67   989.8 1454.02  1078.4 1471.75
    1138 1488.17  1166.7 1490.65    1181 1500.01  1223.3 1516.85  1319.3 1540.73
  1510.2 1562.47  1828.1 1593.07  1936.5 1606.34  2010.1 1611.63  2177.9 1632.07
#Mann= 7 ,-1,0
       0      .1       0  544.85    .045       0  688.11      .1       0
 1230.45     .06       0 1340.45      .1       0 1460.45     .05       0
 2050.45      .1       0
#XS Ineff= 2 , 0
          491.54 1433.56
Permanent Ineff=
       F       F
Bank Sta=544.85,688.11
XS Rating Curve= 0 ,0
Exp/Cntr(USF)=0,0
Exp/Cntr=0.3,0.1

Type RM Length L Ch R = 1 ,23406   ,979.7,1041.7,1105.1
XS GIS Cut Line= 3
2187633.80054988704646.7932167352188454.92499314705567.447895545
2188579.33778758706193.658960862
#Sta/Elev= 30
       0 1526.22    69.7 1511.64   228.3 1466.01   317.8 1450.83   368.8 1447.46
   385.8 1434.26   406.2 1434.05   431.2 1443.75   533.2 1437.63   634.6  1427.1
   788.1  1428.4   827.8 1423.27   850.9 1416.21   874.9 1416.61  887.121412.937
   895.8  1405.9   903.6 1404.59   983.1 1404.83  990.991412.938  1023.3 1436.63
  1048.4 1448.18  1127.3 1497.96  1144.8 1507.11    1177 1517.72  1292.5  1524.8
  1386.3 1512.45  1545.8 1524.13  1696.2 1545.92  1794.1 1575.73  1872.1 1589.47
#Mann= 8 ,-1,0
       0      .1       0     320     .05       0     850      .1       0
  887.12    .045       0  990.99      .1       0 1543.63     .05       0
 1743.63     .06       0 1843.63     .05       0
Bank Sta=887.12,990.99
XS Rating Curve= 0 ,0
Exp/Cntr(USF)=0,0
Exp/Cntr=0.3,0.1

Type RM Length L Ch R = 1 ,22365   ,1151.8,1189.5,1220.3
XS GIS Cut Line= 2
2187496.53168549704620.2765275152187159.44264458705803.808721027
#Sta/Elev= 30
       0 1533.67    59.2 1520.92      80 1511.86   104.9 1496.93   142.3 1465.64
   146.5  1463.9   171.5 1463.41   204.7 1456.88   275.4  1449.5   321.5 1438.03
   460.7 1430.17   487.6 1432.19   508.3 1426.84   562.4 1424.75   712.1  1428.9
  791.991412.667     812 1405.62   824.4 1404.59   874.3 1404.98   886.8 1412.44
   900.81412.667   907.6 1416.14   920.1 1427.97   936.7 1437.49   982.5 1455.69
  1082.3 1502.19  1114.6 1513.89  1132.2 1515.77  1157.2 1523.25  1230.6 1548.64
#Mann= 5 ,-1,0
       0      .1       0     380     .05       0     580      .1       0
  791.99    .045       0   900.8      .1       0
Bank Sta=791.99,900.8
XS Rating Curve= 0 ,0
Exp/Cntr(USF)=0,0
Exp/Cntr=0.3,0.1

Type RM Length L Ch R = 1 ,21175   ,1278.4,1168.1,1075
XS GIS Cut Line= 3
2187103.07430502703976.5129965762186814.11678746704243.243012786
2186180.63299896704865.613050611
#Sta/Elev= 30
       0 1556.95   101.2 1536.99   227.1 1526.28   281.6  1519.2     343 1508.13
   404.5 1491.16   483.7 1463.57     495  1462.1   561.5 1443.63   618.6 1431.29
   735.4  1423.3   844.6 1421.44   854.2 1419.94  865.681412.456   881.2 1411.18
   893.8 1418.25   899.5 1419.01   928.7 1415.89   933.4 1413.41   941.9 1405.42
     956  1404.5  1046.6 1404.51  1052.2 1406.95 1056.481412.453  1109.5 1452.22
  1125.7 1466.54  1182.3 1505.32  1199.3 1510.91  1217.9 1513.46  1281.3 1513.59
#Mann= 3 ,-1,0
       0      .1       0  865.68    .045       0 1056.48      .1       0
Bank Sta=865.68,1056.48
XS Rating Curve= 0 ,0
Exp/Cntr(USF)=0,0
Exp/Cntr=0.3,0.1

Type RM Length L Ch R = 1 ,20007   ,1412.2,1369.8,1330.6
XS GIS Cut Line= 2
2185323.86966656703987.4054062362186132.55283038704887.324619307
#Sta/Elev= 30
       0 1532.74    15.6 1528.24    46.8  1527.9    96.2 1507.41   111.9 1494.06
   123.3 1487.35   150.1 1467.75   157.3 1459.94   168.6  1442.4     174 1436.82
   188.4 1434.73   199.7 1430.73  224.071412.235   233.6 1405.03     239 1404.38
   310.2 1404.54  322.471412.233   373.4 1427.22   540.2 1425.97     637 1431.92
     680 1432.97   749.9 1434.52   811.6 1441.12   922.1 1466.86     956 1475.99
  1002.6 1491.62  1055.1 1503.97  1089.1 1508.13  1137.1 1510.92  1209.9 1512.44
#Mann= 6 ,-1,0
       0     .07       0      80      .1       0  224.07    .045       0
  322.47      .1       0     660     .05       0     680      .1       0
#XS Ineff= 2 , 0
                          406.33         1428.05
Permanent Ineff=
       F       F
Bank Sta=224.07,322.47
XS Rating Curve= 0 ,0
Exp/Cntr(USF)=0,0
Exp/Cntr=0.3,0.1

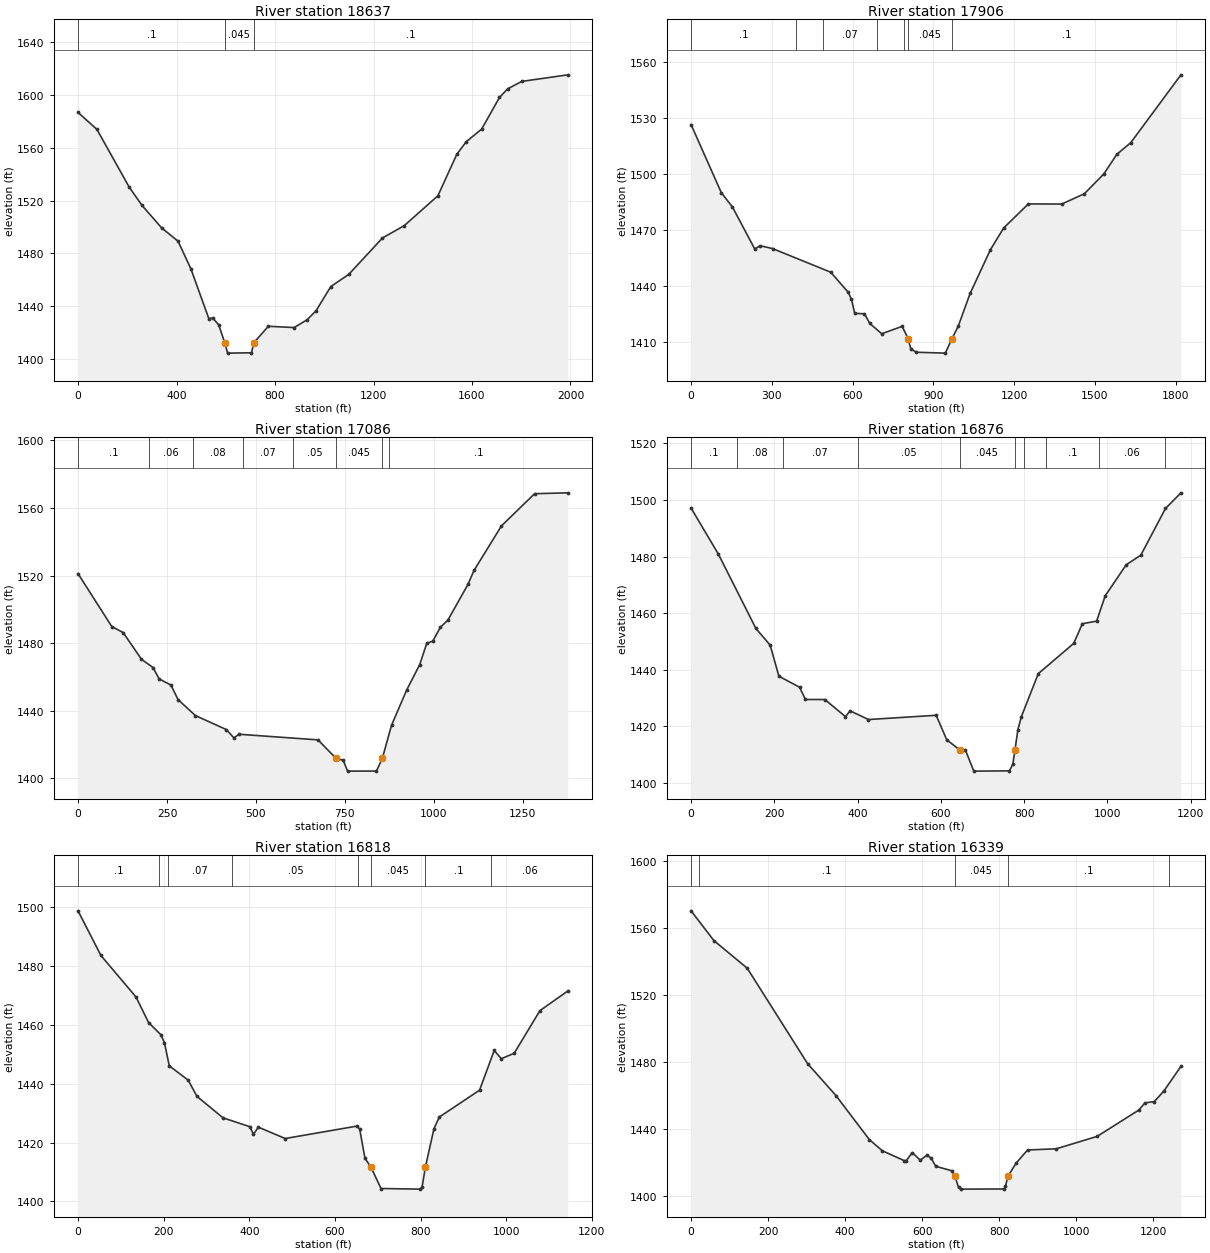
Type RM Length L Ch R = 1 ,18637   ,743.8,731.1,720.9
XS GIS Cut Line= 5
2184905.87173702 705206.233162572185105.91924918705495.190680132
2186095.04305929705617.4419375612186372.88682618705806.375699044
2186628.50309172705973.081959175
#Sta/Elev= 30
       0 1586.86    76.6 1573.99   207.8 1530.18   259.6 1516.38   339.3  1499.3
   406.1 1489.18   458.5 1468.12   531.1 1430.46   547.2 1430.86   571.4 1425.64
  596.041411.981   607.6 1404.22   704.4 1404.48  713.451411.984   772.9 1424.61
   877.7 1423.61   930.1 1429.52   966.3 1436.28  1026.8 1454.77  1099.4 1463.93
  1236.4 1491.58  1325.1 1500.98  1461.4 1523.59  1538.1 1554.99  1576.8 1564.65
  1639.3 1574.21  1711.6 1598.21  1745.3 1604.81  1802.6  1610.4  1989.3 1615.37
#Mann= 3 ,-1,0
       0      .1       0  596.04    .045       0  713.45      .1       0
Bank Sta=596.04,713.45
XS Rating Curve= 0 ,0
Exp/Cntr(USF)=0,0
Exp/Cntr=0.3,0.1

Type RM Length L Ch R = 1 ,17906   ,742.1,820.5,878.9
XS GIS Cut Line= 3
2184607.66006302706427.1534638072185180.68324871706277.285861397
2186406.07129194706208.963866181
#Sta/Elev= 30
       0 1526.68   112.2 1490.21   153.5 1482.57   236.2 1460.08   256.9 1461.78
   302.4 1460.27   518.7 1447.59   583.5 1436.85   595.8 1433.03   607.8 1425.51
   643.9 1425.33   663.9 1420.11     708 1414.61   784.1 1418.57  806.48 1411.89
   816.1 1406.55   836.2 1404.69   944.3 1404.22  968.911411.892   992.4 1418.69
  1036.5  1436.2  1111.8 1459.62  1161.1  1471.3  1252.8 1484.18    1377 1484.13
  1460.9 1489.65    1533 1500.23  1581.3 1510.74  1633.4 1517.04  1819.6 1553.38
#Mann= 7 ,-1,0
       0      .1       0     390     .05       0     490     .07       0
   692.3      .1       0   792.3     .06       0  806.48    .045       0
  968.91      .1       0
Bank Sta=806.48,968.91
XS Rating Curve= 0 ,0
Exp/Cntr(USF)=0,0
Exp/Cntr=0.3,0.1

Type RM Length L Ch R = 1 ,17086   ,145.6,209.7,248.4
XS GIS Cut Line= 4
2184628.60892188706458.9288981752184861.99768606706636.748908982
2185462.14022253707214.6639441042185695.52898672707303.573949508
#Sta/Elev= 30
       0 1521.14      95 1489.78   126.9 1486.25   178.3 1470.43   210.7 1465.57
   228.1 1458.78   261.1 1455.17     281 1446.57   329.8 1437.12   416.9 1428.81
   438.2 1423.85   451.9 1426.06   674.3 1422.72  725.081411.737   745.1 1410.69
   757.3 1404.22   838.4 1404.27  854.981411.735   880.8 1431.33   923.9 1452.45
   960.1 1467.29   979.9 1479.95   996.8 1481.19  1018.3 1489.42  1039.3 1493.65
  1095.6 1514.76  1112.7 1523.07  1189.8 1549.42  1282.8 1568.47  1376.3 1568.99
#Mann= 8 ,-1,0
       0      .1       0     200     .06       0  323.41     .08       0
  463.41     .07       0  603.41     .05       0  725.08    .045       0
  854.98     .08       0  873.41      .1       0
Bank Sta=725.08,854.98
XS Rating Curve= 0 ,0
Exp/Cntr(USF)=0,0
Exp/Cntr=0.3,0.1

Type RM Length L Ch R = 1 ,16876   ,68.6,58.5,61.7
XS GIS Cut Line= 6
   2184627.31782706581.633192361  2185061.042262706993.894045248
2185049.36624751707053.5944869612185082.32162324707223.852457414
2185043.14824423707301.0630741252185199.66522593707505.604483038
#Sta/Elev= 30
       0 1497.14    65.4 1480.92   155.7 1454.61   189.9 1448.75   210.9 1437.75
   260.6 1433.87   274.7 1429.53   321.3 1429.52   370.9 1423.47     382 1425.53
   426.1 1422.45   588.8 1423.95     614 1415.34  645.161411.699   658.8 1411.76
   679.2 1404.22   764.7 1404.31   772.9 1406.65   778.11411.702   785.1 1418.86
   793.3 1423.39   834.1 1438.65   919.2 1449.34     940 1456.29   974.3 1457.22
   994.9 1466.15  1045.3 1477.12  1080.5 1480.53  1139.7 1497.01  1176.8 1502.54
#Mann= 10 ,-1,0
       0      .1       0     110     .08       0     220     .07       0
     400     .05       0  645.16    .045       0   778.1      .1       0
  799.23     .06       0  852.64      .1       0  979.22     .06       0
 1139.22      .1       0
Bank Sta=645.16,778.1
XS Rating Curve= 0 ,0
Exp/Cntr(USF)=0,0
Exp/Cntr=0.3,0.1

Type RM Length L Ch R = 1 ,16818   ,531.7,478.3,432.1
XS GIS Cut Line= 6
2184537.47927534706628.7210931432185013.95436123 707001.42472423
 2185001.1498989707061.1251659432185026.57459566707237.977288947
2184997.19648478707302.1992154522185097.00683194707507.845991667
#Sta/Elev= 30
       0 1498.82    53.5 1483.63   135.5  1469.5   164.7 1460.84   193.2 1456.73
   201.7 1454.04   213.1 1446.11   257.3 1441.25   277.7 1435.74   338.6 1428.43
   401.2 1425.42   409.7 1422.82   421.1 1425.26   483.8  1421.4   651.6 1425.63
   657.9 1424.52   670.1 1414.66     684 1411.69   707.6  1404.4   799.4 1404.19
   803.4 1404.82   811.21411.689   831.2 1424.72   843.8 1428.71   937.7 1437.83
   971.9 1451.33   988.6 1448.55  1018.5 1450.37  1078.7 1464.88  1143.9 1471.58
#Mann= 8 ,-1,0
       0      .1       0     190     .08       0     210     .07       0
     360     .05       0  654.93      .1       0     684    .045       0
   811.2      .1       0  965.28     .06       0
Bank Sta=684,811.2
XS Rating Curve= 0 ,0
Exp/Cntr(USF)=0,0
Exp/Cntr=0.3,0.1

Type RM Length L Ch R = 1 ,16339   ,835.3,766.4,686.4
XS GIS Cut Line= 4
 2183978.8725463707396.2884785582184452.71864215707277.275970762
2184809.75616554707603.4583995362185109.49137036707588.030852229
#Sta/Elev= 30
       0 1570.37    59.1 1552.59   145.7 1536.09   302.4 1479.08   376.1 1459.97
   463.3 1433.53   496.6 1426.94   553.7 1421.02   558.9    1421   574.5 1425.86
   595.2 1421.27     613 1424.37     624 1422.31   635.3 1417.68   677.8 1414.94
  685.221411.626   694.8 1405.07   701.9    1404   812.9 1404.09   816.5 1405.61
  822.781411.625   844.2 1419.53   873.9  1427.4   948.4 1428.11  1054.7 1435.53
  1163.3 1451.32  1178.9 1455.58  1202.9  1456.3    1228 1462.64  1272.3  1477.4
#Mann= 5 ,-1,0
       0     .05       0      20      .1       0  685.22    .045       0
  822.78      .1       0 1242.17     .06       0
Bank Sta=685.22,822.78
XS Rating Curve= 0 ,0
Exp/Cntr(USF)=0,0
Exp/Cntr=0.3,0.1