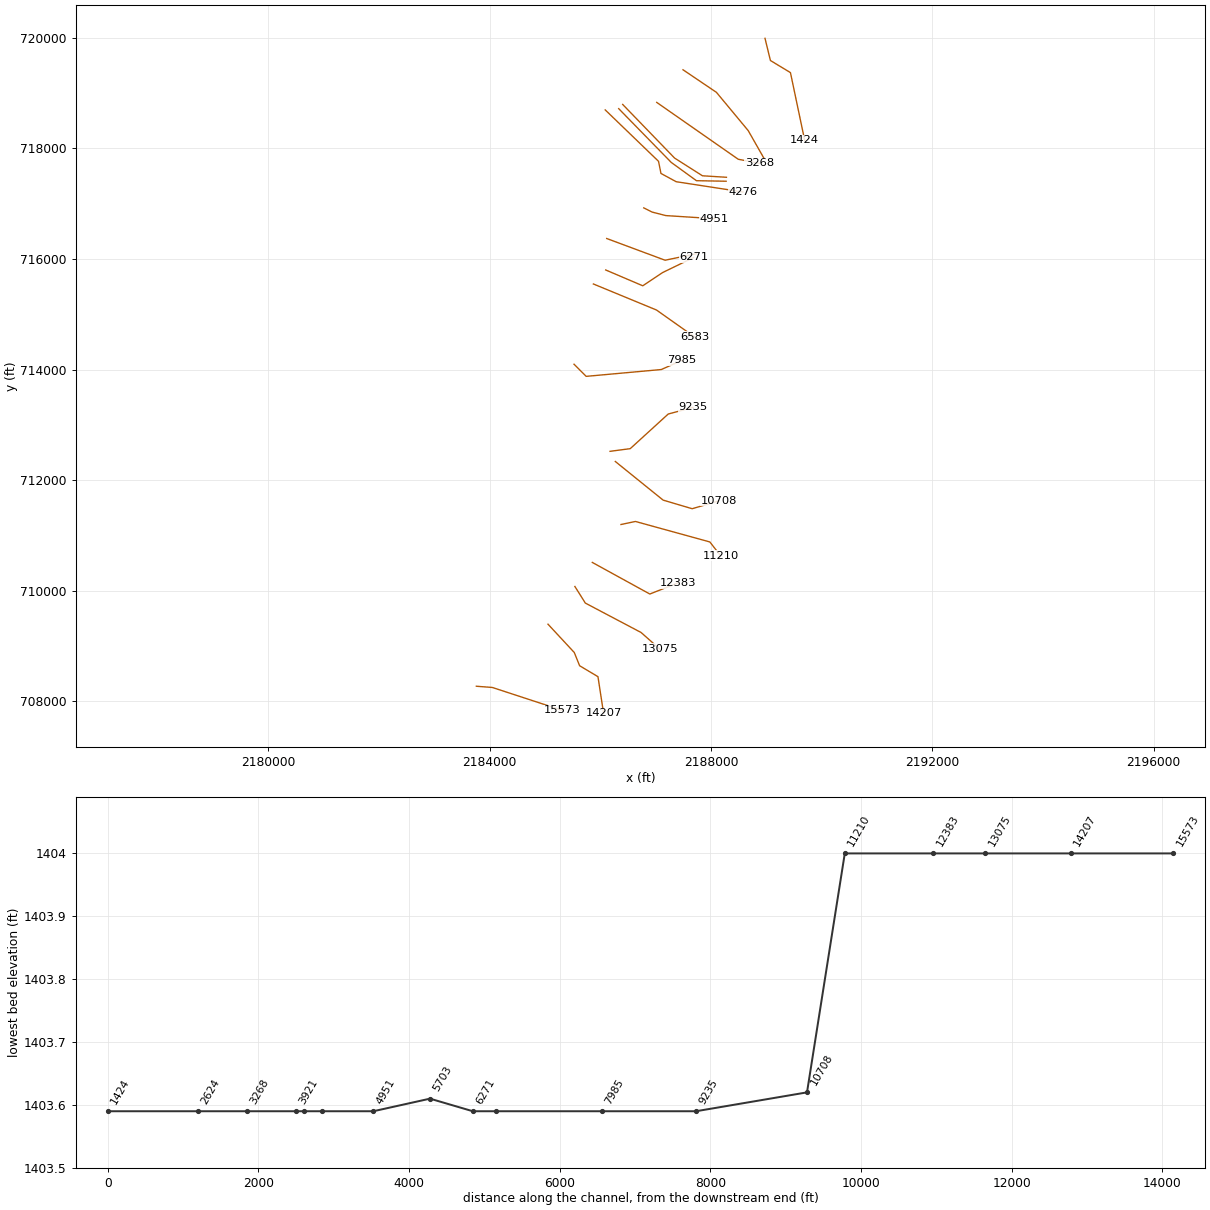
HEC-RAS study BUCKHANR_U.prj: BUCKHANR_U

--- BUCKHANR_U.g01 (geometry) --- (continued)

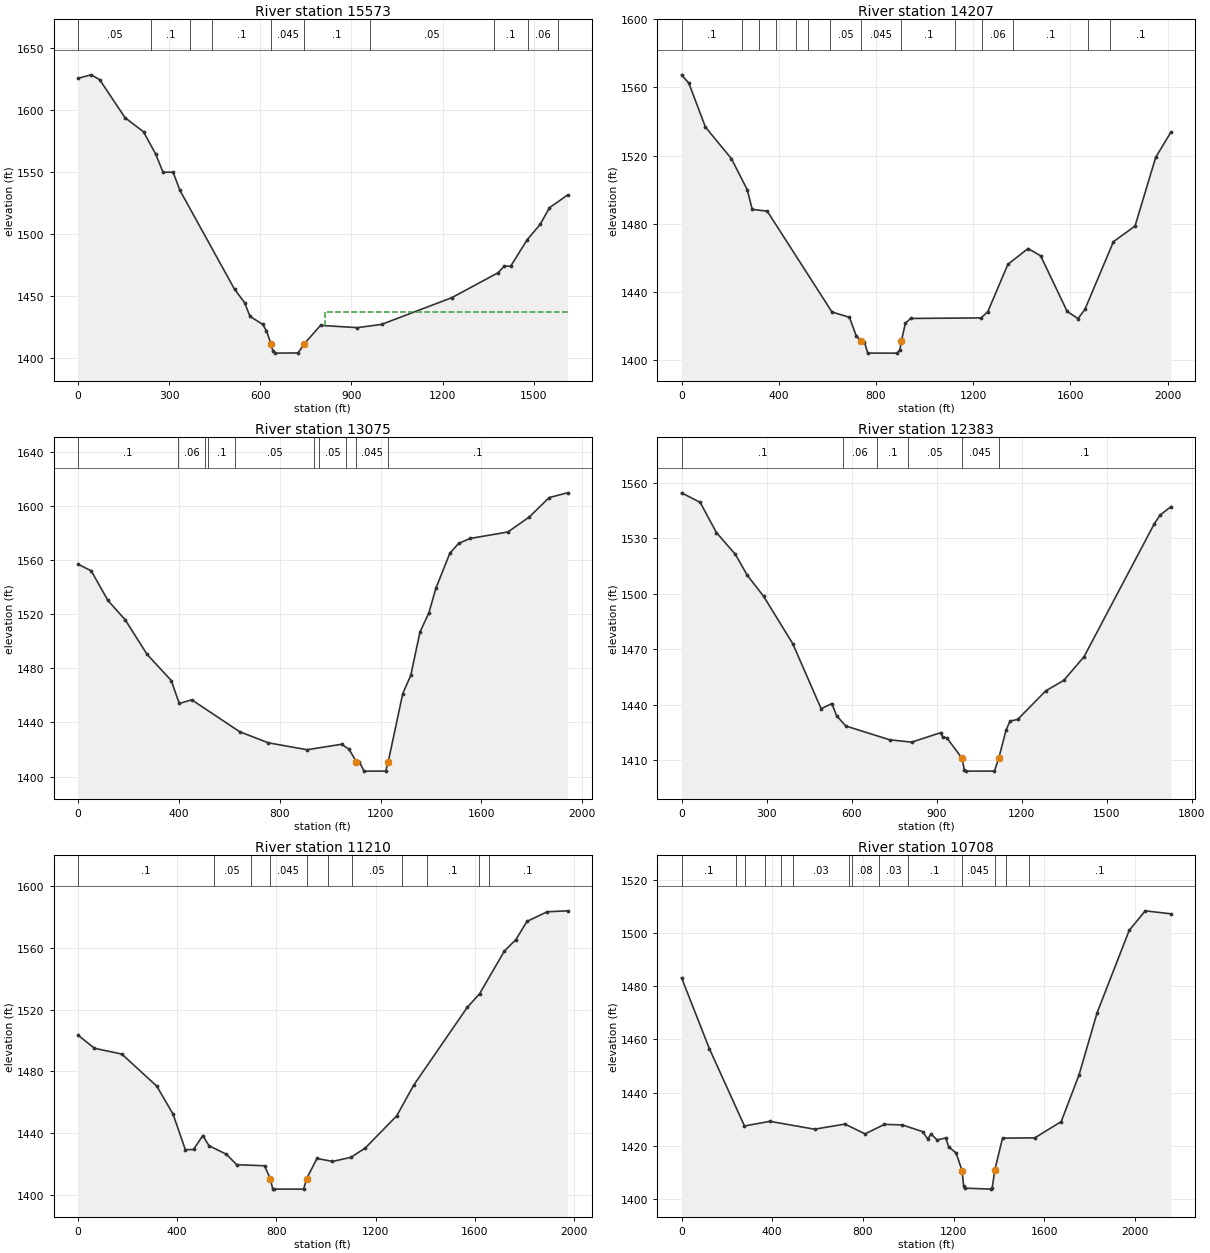
Type RM Length L Ch R = 1 ,15573   ,1421.8,1366.1,1305.5
XS GIS Cut Line= 3
2183761.15541745708273.6283489892184050.11293502708251.400847638
2185305.96676134707840.192072647
#Sta/Elev= 30
       0  1625.5    43.1 1628.32    71.2 1624.44   154.9 1593.76   215.7 1582.38
   255.8 1564.42   279.8  1549.8     313 1549.84   335.5 1535.21   515.2  1455.5
   548.7 1444.56   565.9 1433.68   607.7 1427.21   620.3 1421.99  635.271411.468
   641.3 1405.78   649.7    1404   724.4 1404.16  744.561411.468   798.3 1426.38
   919.1 1424.54   999.1 1427.15  1230.6 1448.72  1382.1  1468.7  1403.1 1474.12
  1424.2 1474.09  1478.9 1495.54    1521 1507.69    1552 1521.23  1611.3 1531.38
#Mann= 10 ,-1,0
       0     .05       0     240      .1       0  369.81     .06       0
  439.81      .1       0  635.27    .045       0  744.56      .1       0
  959.81     .05       0 1369.81      .1       0 1479.81     .06       0
 1579.81      .1       0
#XS Ineff= 2 , 0
                          813.78         1437.11
Permanent Ineff=
       F       F
Bank Sta=635.27,744.56
XS Rating Curve= 0 ,0
Exp/Cntr(USF)=0,0
Exp/Cntr=0.3,0.1

Type RM Length L Ch R = 1 ,14207   ,1067.7,1131.6,1179.6
XS GIS Cut Line= 5
2185055.66513375  709395.64591852185530.27690511708884.171096939
2185627.04241189708644.5612706222185958.80986371708446.422375783
2186060.18325177707782.887472136
#Sta/Elev= 30
       0  1567.4    30.2 1562.47    98.3 1536.74   205.3 1518.15   270.7 1499.84
   290.8 1488.41   352.6 1487.36   619.1 1428.12   690.9 1425.05   718.2  1414.3
  738.131411.246   752.7 1410.61   765.7 1404.01   886.5    1404   898.2 1405.93
  904.731411.249     921  1421.6   942.6 1424.36  1232.4 1424.69  1260.3 1428.42
  1342.6 1456.13  1425.6  1465.4  1477.4 1461.14  1586.6 1428.48  1631.2 1424.28
  1659.5 1429.67  1776.8 1469.42  1865.8 1478.64  1950.8 1518.96  2013.8 1533.91
#Mann= 14 ,-1,0
       0      .1       0     250     .06       0     320     .07       0
     390      .1       0     470     .07       0     520      .1       0
     610     .05       0  738.13    .045       0  904.73      .1       0
 1126.17     .05       0 1236.17     .06       0  1362.6      .1       0
  1672.6     .06       0  1762.6      .1       0
Bank Sta=738.13,904.73
XS Rating Curve= 0 ,0
Exp/Cntr(USF)=0,0
Exp/Cntr=0.3,0.1

Type RM Length L Ch R = 1 ,13075   ,693.3,692,690.9
XS GIS Cut Line= 4
2185541.80578871710077.4672244782185730.73955019709777.395956241
2186737.37992949709245.9259481742187073.51335757708949.076351795
#Sta/Elev= 30
       0 1557.04    52.3  1552.1   118.5 1530.25   187.6 1515.76   274.1  1490.3
   369.8 1470.99   401.5 1454.01   451.2 1456.73   641.2 1433.13   754.3 1424.96
   908.1 1419.83  1045.6 1423.86  1075.2 1420.18 1103.461411.036  1116.1 1410.87
  1134.2    1404  1220.2    1404 1230.461411.032    1288 1461.35  1319.7 1474.81
  1356.4 1506.91  1391.7 1521.08  1419.2 1539.11  1474.8 1565.14  1509.6  1572.4
  1555.4 1576.05  1705.1 1580.83  1790.2    1592  1868.7 1606.28  1941.4 1609.78
#Mann= 10 ,-1,0
       0      .1       0   394.6     .06       0   504.6     .07       0
   514.6      .1       0   624.6     .05       0   934.6      .1       0
   954.6     .05       0  1064.6      .1       0 1103.46    .045       0
 1230.46      .1       0
Bank Sta=1103.46,1230.46
XS Rating Curve= 0 ,0
Exp/Cntr(USF)=0,0
Exp/Cntr=0.3,0.1

Type RM Length L Ch R = 1 ,12383   ,1155.3,1173.3,1191.8
XS GIS Cut Line= 3
2185856.50420912 710512.814384582186895.89099417709941.423743584
2187399.25893981710140.050014026
#Sta/Elev= 30
       0 1554.45    65.7 1549.31   123.2 1532.95   190.2 1521.15   231.7 1509.96
   289.9 1498.45   392.2 1472.97   492.6 1437.74   530.6 1440.52   547.3 1433.91
   579.7 1428.41   734.5 1420.93   812.1 1419.66   915.5 1424.85   921.7 1422.31
   936.1 1421.99  990.151410.899     998 1404.51  1003.7    1404    1104 1404.03
 1119.141410.901  1145.2 1426.19    1159 1431.05  1186.1 1431.95  1285.3 1447.42
  1348.9 1453.08  1420.5 1465.92    1668 1537.67  1688.7 1542.42  1727.2 1547.01
#Mann= 6 ,-1,0
       0      .1       0     570     .06       0     690      .1       0
     800     .05       0  990.15    .045       0 1119.14      .1       0
Bank Sta=990.15,1119.14
XS Rating Curve= 0 ,0
Exp/Cntr(USF)=0,0
Exp/Cntr=0.3,0.1

Type RM Length L Ch R = 1 ,11210   ,502.7,501.6,499.6
XS GIS Cut Line= 4
2186375.19981358711198.7798228692186635.89273066711253.662542254
2187980.51935558710883.2041864062188172.60887343710636.231949174
#Sta/Elev= 30
       0 1503.47    66.4 1494.99   176.8 1491.23   317.7 1470.53   382.9 1452.55
   432.9 1429.46   465.9  1429.6   503.2 1438.63   528.1 1432.04   598.3 1426.54
   640.1 1419.78   752.1 1419.09  775.441410.713   785.3 1404.12   790.7    1404
   909.8    1404   921.71410.713   963.7 1423.82    1026  1421.9  1099.8 1424.49
  1158.7 1430.59  1285.2 1451.33  1353.7 1471.16  1569.5 1521.38  1619.3 1530.18
  1719.3 1557.74  1765.9 1565.22  1810.4 1576.92  1891.7 1583.17    1974 1583.77
#Mann= 11 ,-1,0
       0      .1       0  546.41     .05       0  696.41      .1       0
  775.44    .045       0   921.7      .1       0 1006.41    .025       0
 1106.41     .05       0 1306.41     .08       0 1406.41      .1       0
 1616.41     .06       0 1656.41      .1       0
Bank Sta=775.44,921.7
XS Rating Curve= 0 ,0
Exp/Cntr(USF)=0,0
Exp/Cntr=0.3,0.1

Type RM Length L Ch R = 1 ,10708   ,1397.9,1473.4,1567.4
XS GIS Cut Line= 4
 2186272.2879501712338.1112372232187136.37974587711639.531872334
2187660.95748593711484.1262328422188141.17295488711625.156054581
#Sta/Elev= 30
       0 1483.26   122.9 1456.51   277.6  1427.4   389.6 1429.16   586.8 1426.19
   720.4 1428.12   809.5 1424.43   894.9 1428.01   973.3 1427.81  1064.3 1425.25
  1085.2 1422.54  1100.6 1424.34  1127.6 1422.13  1165.2  1422.9  1177.7 1419.61
  1211.1 1417.22 1237.031410.636  1244.4  1404.7  1248.6 1403.99  1365.4 1403.62
  1370.4 1404.22 1381.171410.638  1415.6 1422.82  1557.9 1422.93  1674.6 1429.06
  1753.3  1446.7  1832.5 1469.97  1974.3 1501.06  2045.1 1508.44  2158.8 1507.31
#Mann= 14 ,-1,0
       0      .1       0     240     .06       0     280      .1       0
     370     .08       0     440      .1       0     490     .03       0
     740    .025       0     750     .08       0     870     .03       0
    1000      .1       0 1237.03    .045       0 1381.17      .1       0
 1431.16    .025       0 1531.16      .1       0
Bank Sta=1237.03,1381.17
XS Rating Curve= 0 ,0
Exp/Cntr(USF)=0,0
Exp/Cntr=0.3,0.1

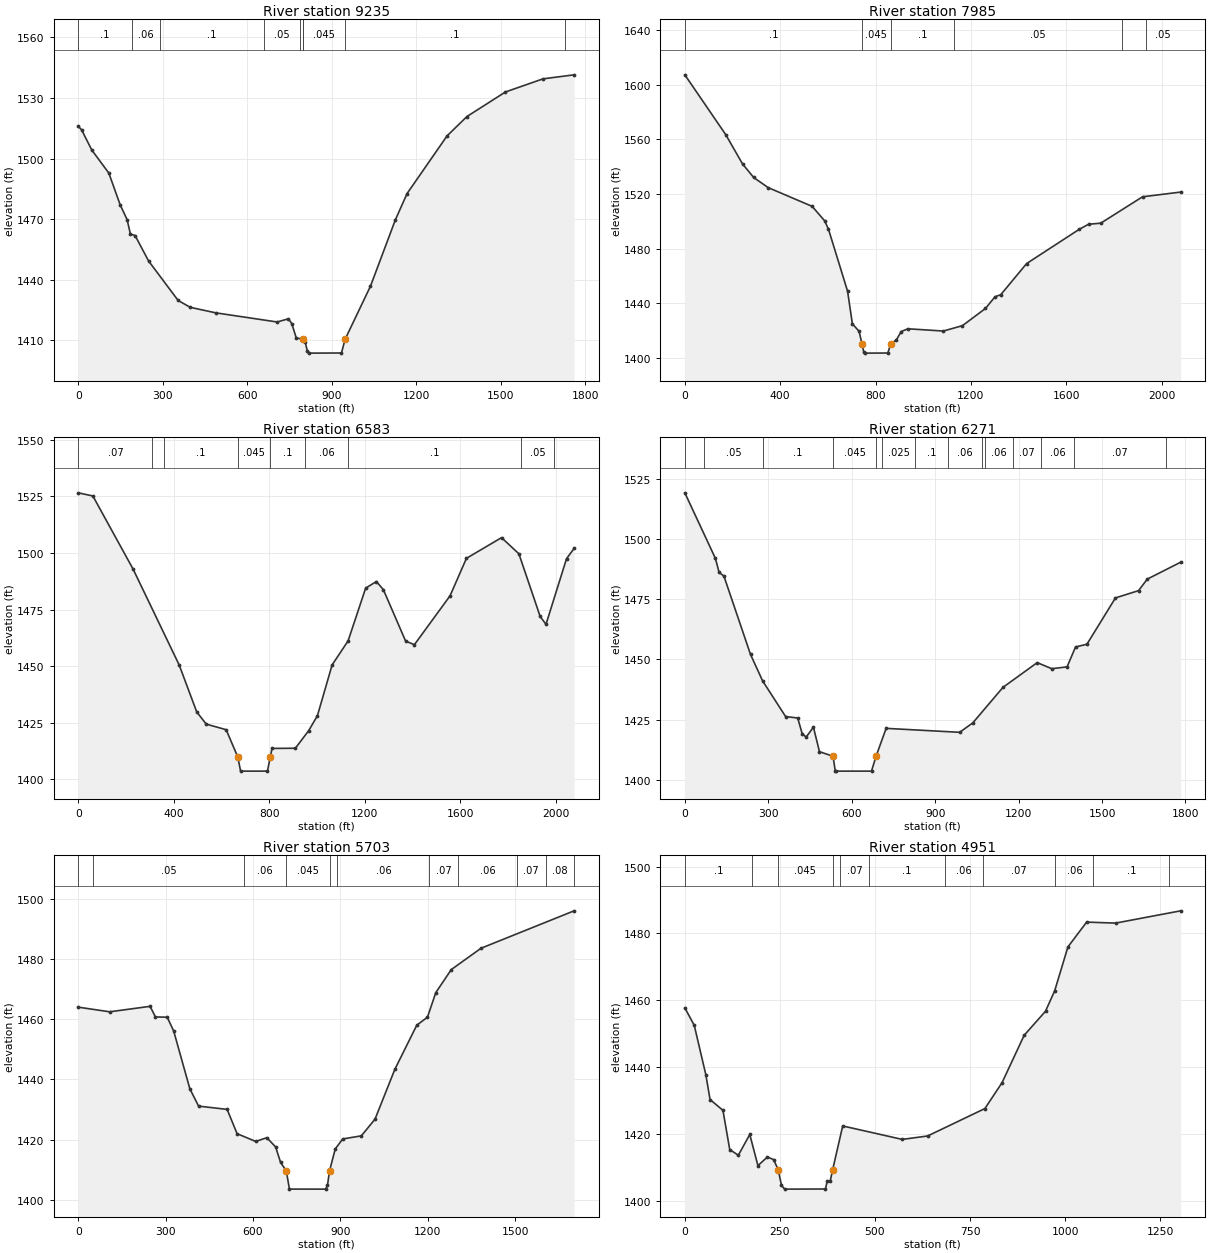
Type RM Length L Ch R = 1 ,9235    ,1293.1,1249.6,1198.9
XS GIS Cut Line= 4
2186176.85438356712522.1671324082186541.84900471  712570.3484535
2187227.96407081  713196.42146182187675.62890412713316.996055025
#Sta/Elev= 30
       0 1515.88    11.4 1514.27    47.7 1504.21   108.3 1492.79   148.6 1477.05
   173.2 1469.73   184.9 1462.61   201.7 1461.82   249.5 1449.24   354.4 1429.69
   397.3 1426.28   487.9 1423.55   705.9 1419.02   746.2  1420.6   758.1 1418.17
   773.9 1411.12  799.441410.408   805.6 1409.06   813.5 1404.48   820.8 1403.59
   934.5 1403.66  947.231410.408  1037.4 1436.74    1126 1469.67  1167.4 1482.63
  1309.6 1511.24  1380.1  1520.8  1516.8 1532.96  1650.2 1539.46  1760.6 1541.45
#Mann= 9 ,-1,0
       0      .1       0     190     .06       0     290      .1       0
  658.16     .05       0  788.16    .025       0  798.16      .1       0
  799.44    .045       0  947.23      .1       0 1726.99     .05       0
Bank Sta=799.44,947.23
XS Rating Curve= 0 ,0
Exp/Cntr(USF)=0,0
Exp/Cntr=0.3,0.1

Type RM Length L Ch R = 1 ,7985    ,1434.1,1401.7,1364.3
XS GIS Cut Line= 4
2185525.93815335714097.4865139162185745.46903089713877.955636377
2187103.81633567714001.4417549932187474.27469152714166.089913147
#Sta/Elev= 30
       0  1607.1   171.5 1563.37   242.2  1541.9   288.9 1532.02   349.3 1524.65
   534.1 1510.91   586.3 1500.38   602.4 1494.29   682.7 1448.84   702.8 1424.99
   730.9 1419.58  743.371410.141     751 1404.08     755 1403.59   851.4 1403.67
  863.571410.142   887.5 1413.32   907.6 1419.36   935.7  1421.4  1084.3 1419.74
  1164.7 1423.69  1261.1 1436.26  1301.2  1444.8  1325.3 1446.32  1433.8  1469.1
  1654.7 1494.15  1693.5 1497.82  1744.8 1498.62  1919.9 1517.91  2079.8 1521.35
#Mann= 6 ,-1,0
       0      .1       0  743.37    .045       0  863.57      .1       0
 1130.46     .05       0 1834.41     .07       0 1934.41     .05       0
Bank Sta=743.37,863.57
XS Rating Curve= 0 ,0
Exp/Cntr(USF)=0,0
Exp/Cntr=0.3,0.1

Type RM Length L Ch R = 1 ,6583    ,313.9,312.1,310.8
XS GIS Cut Line= 3
2185875.87398422715548.597766495 2187015.9343584715077.880714627
2187704.32403541714590.838215874
#Sta/Elev= 30
       0 1526.55    60.9 1525.15   229.5 1492.83   422.5 1450.48     496 1429.73
   535.8 1424.36   619.2 1421.89  668.021409.814   679.7 1403.59   792.3 1403.59
  803.911409.811   811.5 1413.62   909.1  1413.7   964.6 1421.43  1001.4 1428.05
    1063 1450.51    1130 1461.14  1203.5 1484.43  1248.5 1487.37  1277.8 1483.75
  1370.9 1461.04  1407.8 1459.47  1557.1 1481.06  1625.7 1497.62  1772.7 1506.75
  1845.3 1499.63  1934.4 1471.95  1958.9 1468.44  2044.9 1497.44  2076.7    1502
#Mann= 9 ,-1,0
       0     .07       0     310     .06       0     360      .1       0
  668.02    .045       0  803.91      .1       0     950     .06       0
    1130      .1       0 1853.41     .05       0 1993.41      .1       0
Bank Sta=668.02,803.91
XS Rating Curve= 0 ,0
Exp/Cntr(USF)=0,0
Exp/Cntr=0.3,0.1

Type RM Length L Ch R = 1 ,6271    ,564.2,568.2,572.5
XS GIS Cut Line= 4
2186098.98842499715801.642193222 2186768.3317473715515.946872724
2187127.49157878715755.3867603792187687.99858852716027.477541805
#Sta/Elev= 30
       0 1519.09     110 1491.85   123.1 1486.07   140.5 1484.53   236.1 1452.02
   279.6 1441.04   362.3 1426.24   405.8 1425.63   421.9  1419.1   436.2 1417.73
   462.3 1421.83     484 1411.66  532.821409.754   540.6  1403.8   544.9 1403.59
   671.1 1403.59  687.471409.755   723.7 1421.34   988.1  1419.7  1035.3 1423.61
  1143.9 1438.37  1266.9 1448.62  1319.2  1446.1  1374.2 1446.85  1404.7 1455.12
  1445.6 1456.25  1548.2 1475.48  1631.2  1478.5  1662.6 1483.28  1782.5 1490.29
#Mann= 14 ,-1,0
       0     .06       0      70     .05       0     280      .1       0
  532.82    .045       0  687.47      .1       0     710    .025       0
  827.77      .1       0  947.77     .06       0 1067.77      .1       0
 1077.77     .06       0 1179.42     .07       0 1279.42     .06       0
 1399.42     .07       0 1729.42     .08       0
Bank Sta=532.82,687.47
XS Rating Curve= 0 ,0
Exp/Cntr(USF)=0,0
Exp/Cntr=0.3,0.1

Type RM Length L Ch R = 1 ,5703    ,743.9,751.8,761.3
XS GIS Cut Line= 3
 2186117.1629545716370.7429128852187171.59602306715978.171826479
2187737.23281615716096.045921835
#Sta/Elev= 30
       0 1463.99   107.7 1462.45   246.5 1464.27   264.8 1460.75   305.3 1460.66
   327.6 1456.06     383 1436.92     413 1431.16   511.1 1430.07   545.3 1422.01
   609.3 1419.43   647.4 1420.68   677.6 1417.62   694.7 1412.49  714.371409.642
   725.1 1403.62   849.5 1403.61   855.8 1404.89  862.811409.641   882.5 1416.95
   908.1 1420.26   972.1 1421.29  1019.1 1426.83  1087.3 1443.39  1162.5    1458
  1199.2 1460.67  1227.9 1468.83    1281 1476.46  1383.1 1483.54  1702.9 1495.96
#Mann= 11 ,-1,0
       0     .06       0      50     .05       0     570     .06       0
  714.37    .045       0  862.81     .07       0     890     .06       0
 1205.14     .07       0 1305.14     .06       0 1505.14     .07       0
 1605.14     .08       0 1702.93     .07       0
Bank Sta=714.37,862.81
XS Rating Curve= 0 ,0
Exp/Cntr(USF)=0,0
Exp/Cntr=0.3,0.1

Type RM Length L Ch R = 1 ,4951    ,691.4,675.3,655.1
XS GIS Cut Line= 4
2186786.81581717716924.9810350372186936.46574695716849.137808488
2187185.17808574716785.5137218212188062.90128136716729.119645001
#Sta/Elev= 30
       0 1457.74    24.7 1452.57    55.3 1437.74    66.3 1430.36   100.2 1427.14
   118.1 1415.41   140.7 1413.72   170.8 1419.92   192.2 1410.62     217 1413.17
   233.3 1412.43  245.481409.436   254.2 1404.72   262.4 1403.59   369.8 1403.63
   374.6    1406   382.2 1405.88  388.861409.433   415.2 1422.47   571.8 1418.45
   638.5 1419.47   789.2 1427.67   834.3  1435.4   892.5 1449.57   948.6 1456.75
   972.6 1462.82  1007.6 1475.98  1056.8 1483.39  1132.9 1483.09    1304 1486.76
#Mann= 11 ,-1,0
       0      .1       0  177.77     .06       0  245.48    .045       0
  388.86     .06       0  407.77     .07       0  484.49      .1       0
  684.49     .06       0  784.49     .07       0  974.49     .06       0
 1074.49      .1       0 1274.49     .06       0
Bank Sta=245.48,388.86
XS Rating Curve= 0 ,0
Exp/Cntr(USF)=0,0
Exp/Cntr=0.3,0.1

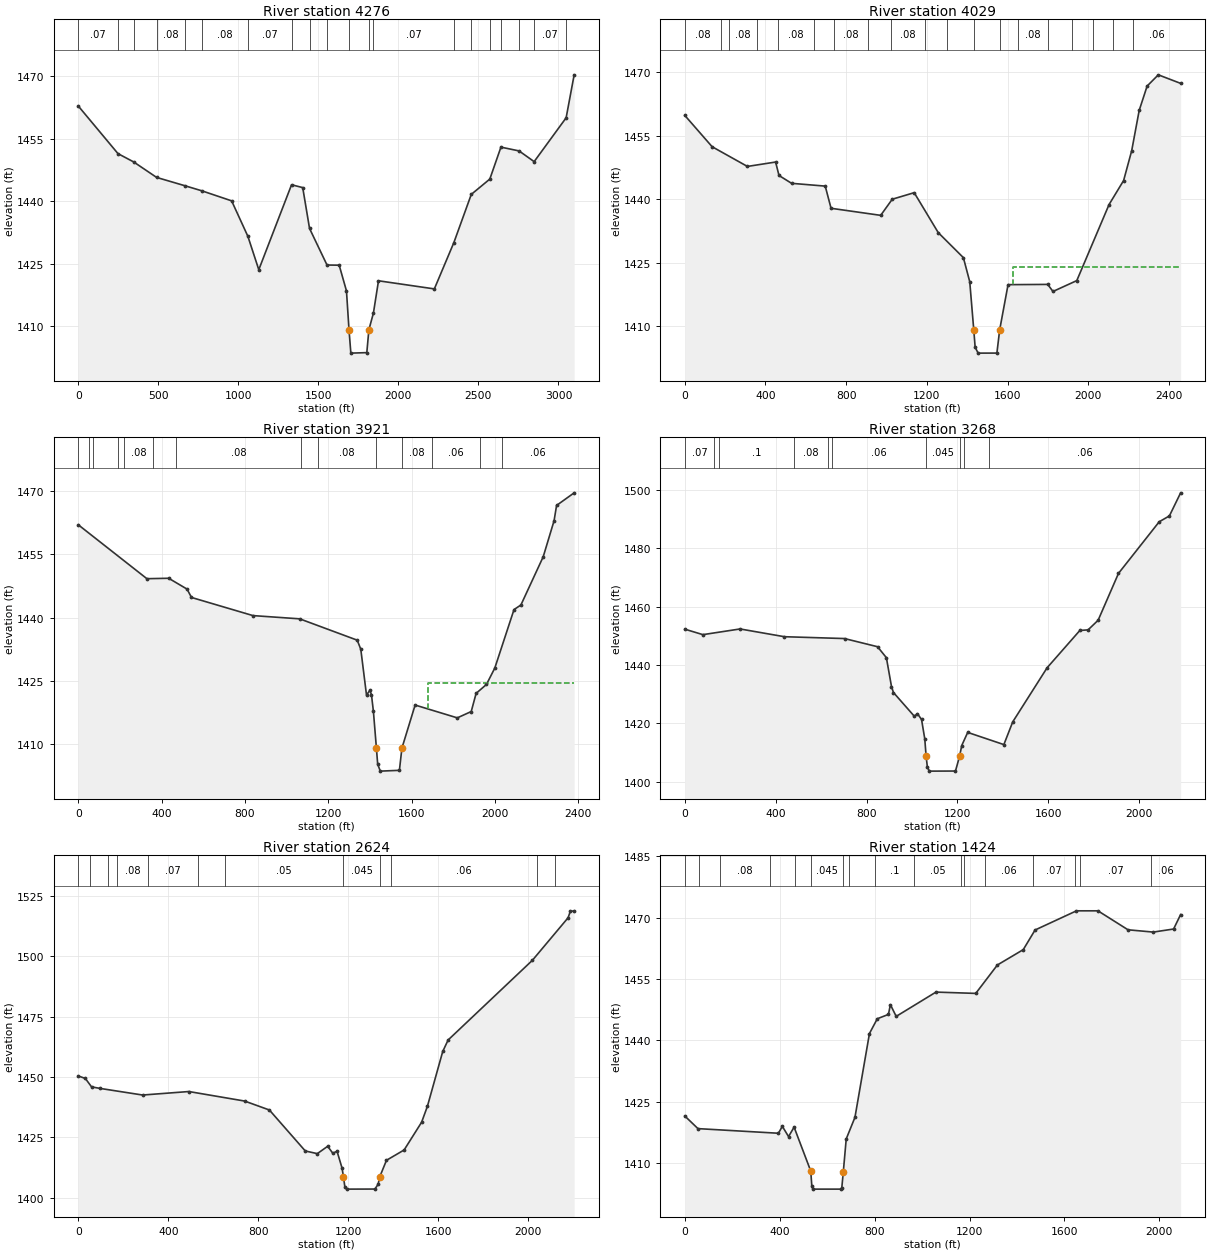
Type RM Length L Ch R = 1 ,4276    ,256.2,246.8,237.2
XS GIS Cut Line= 5
2186089.55190388718696.9672852282187052.99450642717767.083682751
2187097.20065869717547.6435877342187371.97413658717398.315014235
2188580.39869359717212.180618765
#Sta/Elev= 30
       0 1462.87   247.8 1451.46   345.3 1449.48   489.3 1445.75   666.5 1443.75
   770.8 1442.55   957.9 1440.13  1059.5 1431.61  1127.6 1423.61  1332.3 1443.99
  1402.1 1443.31  1444.7 1433.51  1553.9 1424.73    1630 1424.69  1675.5 1418.52
 1691.351409.178  1702.8 1403.59  1802.6 1403.71 1815.421409.174  1843.9 1413.21
  1875.6 1420.95  2224.6    1419  2346.7 1430.13  2455.4 1441.68  2571.1 1445.35
  2640.7 1453.02    2754 1452.11  2848.2 1449.54  3048.1 1460.06  3098.2 1470.37
#Mann= 20 ,-1,0
       0     .07       0   247.8     .06       0   345.3     .07       0
   489.3     .08       0   666.5      .1       0   770.8     .08       0
  1059.5     .07       0  1332.3     .08       0  1444.7     .07       0
  1553.9     .06       0 1691.35    .045       0 1815.42     .08       0
  1843.9     .07       0  2346.7     .08       0  2455.4     .07       0
  2571.1     .06       0  2640.7     .07       0    2754     .06       0
  2848.2     .07       0  3048.1     .06       0
Bank Sta=1691.35,1815.42
XS Rating Curve= 0 ,0
Exp/Cntr(USF)=0,0
Exp/Cntr=0.3,0.1

Type RM Length L Ch R = 1 ,4029    ,104,108.2,112.3
XS GIS Cut Line= 4
2186333.55382972718719.2279460352187283.90486873717746.367543636
2187738.41338548717416.5796882912188274.80345971717406.691789262
#Sta/Elev= 30
       0 1459.77   135.4 1452.37   310.4 1447.71   450.2 1448.75     467 1445.57
   529.4 1443.72   696.2 1443.06     725 1437.82   971.1 1436.15  1028.4 1439.96
  1137.2 1441.51  1256.4 1432.07  1381.1 1426.15  1412.6 1420.46 1432.551409.073
  1439.4 1404.97  1454.2 1403.59  1547.2  1403.6 1560.911409.075  1602.5 1419.77
  1799.2 1419.83  1825.2 1418.16  1943.3 1420.73  2103.3 1438.71  2175.4 1444.38
  2215.4 1451.42  2252.7 1460.97    2292 1466.71  2347.4 1469.36    2458 1467.34
#Mann= 19 ,-1,0
       0     .08       0     180      .1       0     220     .08       0
     360      .1       0     460     .08       0     640     .07       0
     740     .08       0     910     .07       0    1020     .08       0
    1190     .07       0    1300     .08       0 1432.55    .045       0
 1560.91      .1       0 1650.01     .08       0 1800.01     .06       0
 1920.01     .07       0 2021.56     .08       0 2121.56     .07       0
 2221.56     .06       0
#XS Ineff= 2 , 0
                          1625.3            1424
Permanent Ineff=
       F       F
Bank Sta=1432.55,1560.91
XS Rating Curve= 0 ,0
Exp/Cntr(USF)=0,0
Exp/Cntr=0.3,0.1

Type RM Length L Ch R = 1 ,3921    ,653.3,653.2,653.4
XS GIS Cut Line= 4
2186405.31540841718795.7736299692187343.19530462717825.816159883
2187846.96192306717505.3183550682188280.40684975717478.174123279
#Sta/Elev= 30
       0 1461.99   329.2 1449.22   433.8 1449.32     522 1446.75   543.3 1444.77
   838.4 1440.47  1062.9  1439.7  1339.1 1434.64  1356.2 1432.48  1383.6 1421.63
  1399.7 1422.74  1407.3 1421.75  1416.8 1417.73 1431.211409.016  1437.3 1405.21
    1450 1403.59  1541.6 1403.78 1553.521409.018    1617 1419.26  1819.5 1416.22
  1886.4 1417.72  1909.8 1422.02  1959.6 1424.15  1999.6 1428.03  2091.8  1441.9
  2124.9 1442.98  2232.1 1454.43  2284.2 1462.97  2296.2 1466.59  2380.6 1469.58
#Mann= 14 ,-1,0
       0     .07       0      50     .08       0      70     .07       0
     190      .1       0     220     .08       0     360      .1       0
     470     .08       0    1070      .1       0    1150     .08       0
 1431.21    .045       0 1553.52     .08       0 1699.24     .06       0
 1929.24     .07       0 2036.31     .06       0
#XS Ineff= 2 , 0
                         1679.09         1424.47
Permanent Ineff=
       F       F
Bank Sta=1431.21,1553.52
XS Rating Curve= 0 ,0
Exp/Cntr(USF)=0,0
Exp/Cntr=0.3,0.1

Type RM Length L Ch R = 1 ,3268    ,667.7,644.1,622.6
XS GIS Cut Line= 3
2187020.59496991718832.4155191892188493.52479718717804.281332828
2188872.69485173717731.364014646
#Sta/Elev= 30
       0 1452.28    79.6  1450.4   243.3 1452.35   438.5 1449.69     703 1449.06
   848.3 1446.26   887.3  1442.5   909.8 1432.59   918.4 1430.55  1010.4  1422.4
  1023.9 1423.31    1042 1421.31  1056.3 1414.64 1062.041408.763  1067.8 1404.91
  1076.5 1403.59  1191.4 1403.62 1209.71 1408.76    1219 1412.37  1245.2 1416.87
  1404.4 1412.69  1443.4 1420.48  1594.6 1439.03  1738.8 1451.83  1775.1 1452.04
  1819.3 1455.34  1908.9 1471.41  2088.2 1489.12    2133 1491.12  2182.4 1499.04
#Mann= 10 ,-1,0
       0     .07       0     130     .08       0     150      .1       0
     480     .08       0     630     .07       0     650     .06       0
 1062.04    .045       0 1209.71     .06       0    1230    .025       0
    1340     .06       0
Bank Sta=1062.04,1209.71
XS Rating Curve= 0 ,0
Exp/Cntr(USF)=0,0
Exp/Cntr=0.3,0.1

Type RM Length L Ch R = 1 ,2624    ,1172.1,1199.9,1228.8
XS GIS Cut Line= 4
2187495.46049959719422.5451140082188099.48144208719014.372900251
2188673.50405861718322.640788573 2188958.2306115717822.232429003
#Sta/Elev= 30
       0 1450.44      31 1449.44    58.8 1445.94    97.4 1445.29   285.7 1442.56
   491.2 1444.01   738.9 1440.07   849.1 1436.36  1008.7 1419.39  1062.1 1418.29
  1108.1 1421.33    1131 1418.46  1149.8 1419.28  1172.4 1412.19 1178.451408.521
  1184.8 1404.36  1193.2 1403.59  1317.9 1403.62  1332.6 1405.61 1338.851408.521
  1369.5 1415.53  1447.9 1419.81  1525.6 1431.29  1551.3 1437.86  1619.5 1460.59
  1643.4 1465.35  2018.1 1498.37  2176.5 1515.96  2186.4 1518.59  2203.6 1518.85
#Mann= 12 ,-1,0
       0     .07       0      50     .06       0     130     .07       0
     170     .08       0     310     .07       0     530     .06       0
     650     .05       0 1178.45    .045       0 1338.85     .08       0
    1389     .06       0 2037.89     .07       0 2117.89     .06       0
Bank Sta=1178.45,1338.85
XS Rating Curve= 0 ,0
Exp/Cntr(USF)=0,0
Exp/Cntr=0.3,0.1

Type RM Length L Ch R = 1 ,1424    ,861.8,865,867.6
XS GIS Cut Line= 4
2188977.57663444719991.0650770092189074.93980645719590.340280104
2189437.09949746719371.248037563 2189694.9898748718144.232768536
#Sta/Elev= 30
       0 1421.48    55.5 1418.39   394.5 1417.26   411.1 1418.95   437.2 1416.44
   460.6 1418.75   530.81408.005   535.4 1404.25   540.1 1403.59   656.9 1403.59
   661.6 1403.89     6681407.825   680.3 1415.87   717.1 1421.16   778.2 1441.66
   811.2 1445.27   858.2 1446.33   866.4 1448.71   890.9 1445.85  1058.5 1451.79
  1226.1 1451.47  1317.3 1458.42  1426.4 1462.18  1476.1 1466.98  1650.6 1471.67
  1741.1 1471.67  1867.8 1467.03  1974.1 1466.47  2059.9 1467.22  2089.5 1470.76
#Mann= 17 ,-1,0
       0     .06       0      60     .07       0     150     .08       0
     360      .1       0  462.38     .08       0   530.8    .045       0
     668     .07       0  692.38     .06       0  802.38      .1       0
  965.66     .05       0 1165.66     .06       0 1175.66     .05       0
 1265.66     .06       0 1465.66     .07       0 1645.66     .05       0
 1665.66     .07       0 1965.66     .06       0
Bank Sta=530.8,668
XS Rating Curve= 0 ,0
Exp/Cntr(USF)=0,0
Exp/Cntr=0.3,0.1