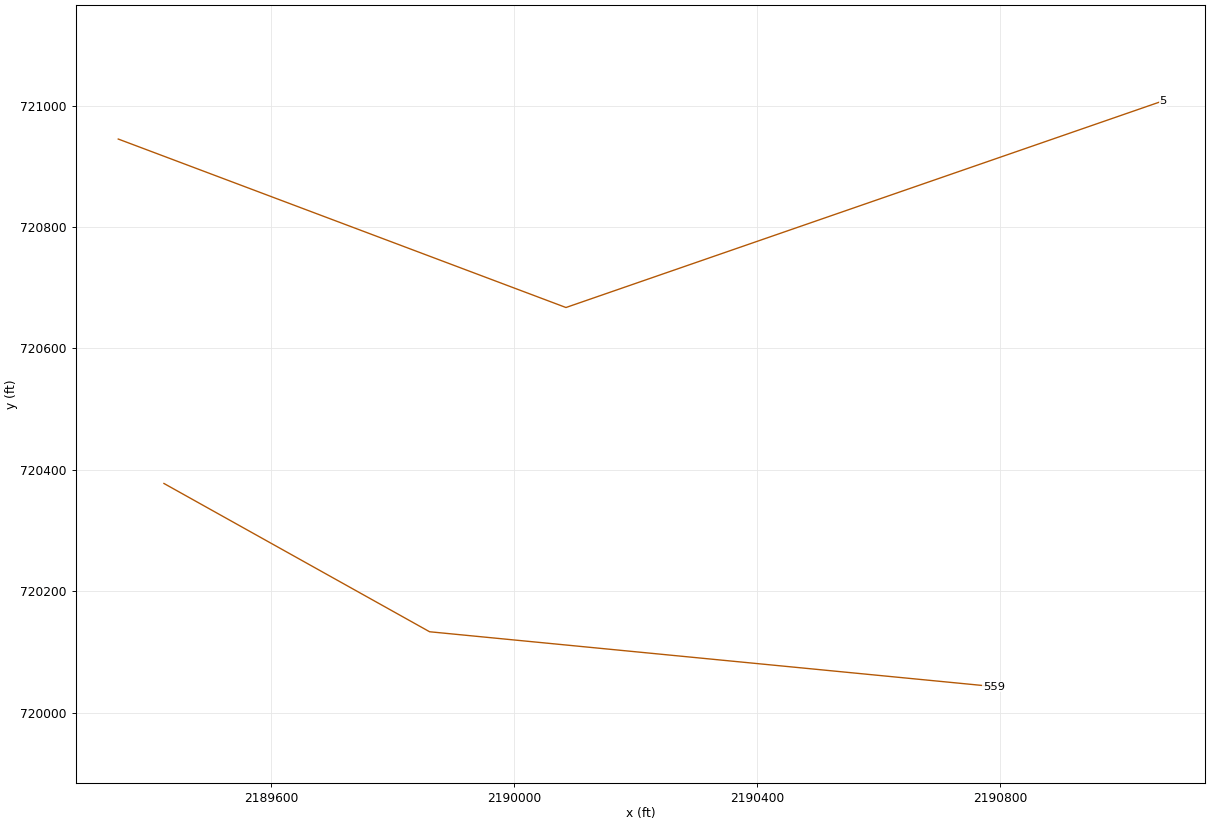
HEC-RAS study BUCKHANR_U.prj: BUCKHANR_U

--- BUCKHANR_U.g01 (geometry) --- (continued)

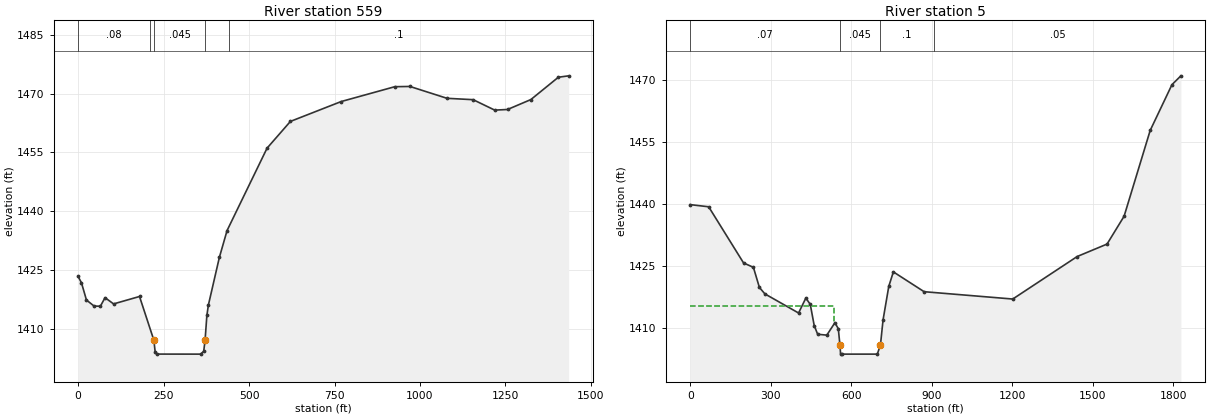
Type RM Length L Ch R = 1 ,559     ,542.3,553.9,564.8
XS GIS Cut Line= 3
2189423.27537887720377.5977563092189860.74828021720133.405222399
 2190790.2660774720043.086613799
#Sta/Elev= 30
       0 1423.38     9.8 1421.81    24.5 1417.38    46.8 1415.84    65.2  1415.8
    78.9 1417.98   103.9 1416.39   179.7 1418.28  221.681407.134   225.5 1404.12
   230.1  1403.6   358.3 1403.59   367.5 1404.32  371.461407.134   376.7 1413.44
   381.2 1416.12   413.3 1428.26   435.8 1435.09   552.7 1456.08     621  1462.9
   769.7 1467.97   926.4 1471.75   970.6 1471.81  1079.1 1468.79  1155.5 1468.44
  1218.6 1465.78    1256 1465.94  1324.3 1468.47  1404.7 1474.16  1434.9 1474.52
#Mann= 5 ,-1,0
       0     .08       0     210     .07       0  221.68    .045       0
  371.46     .06       0     440      .1       0
Bank Sta=221.68,371.46
XS Rating Curve= 0 ,0
Exp/Cntr(USF)=0,0
Exp/Cntr=0.3,0.1

Type RM Length L Ch R = 1 ,5       ,,,
XS GIS Cut Line= 3
2189348.02532983720944.7793453412190085.28398795720667.360127813
2191068.17844689721007.530047805
#Sta/Elev= 30
       0 1439.87    68.5 1439.35   198.5 1425.72   235.2 1424.65   257.5 1419.78
     278 1418.21   403.5 1413.57   430.5 1417.19     447 1415.68   461.7 1410.53
   474.6 1408.41   508.7  1408.2   538.7  1411.2   551.5 1409.77  557.491405.829
     560 1403.63   564.3 1403.59   696.8 1403.59  708.561405.827   718.2 1411.88
   739.5 1420.02   756.6 1423.55   871.2 1418.74  1201.4 1416.96  1441.5 1427.28
  1552.7  1430.3  1616.2 1437.05  1713.5 1457.89  1794.5 1468.98  1827.8 1471.13
#Mann= 4 ,-1,0
       0     .07       0  557.49    .045       0  708.56      .1       0
  907.73     .05       0
#XS Ineff= 2 , 0
          534.85 1415.34
Permanent Ineff=
       F       F
Bank Sta=557.49,708.56
XS Rating Curve= 0 ,0
Exp/Cntr(USF)=0,0
Exp/Cntr=0.3,0.1
LCMann Table=0

Chan Stop Cuts=-1
Use User Specified Reach Order=0
Composite Channel Slope=5